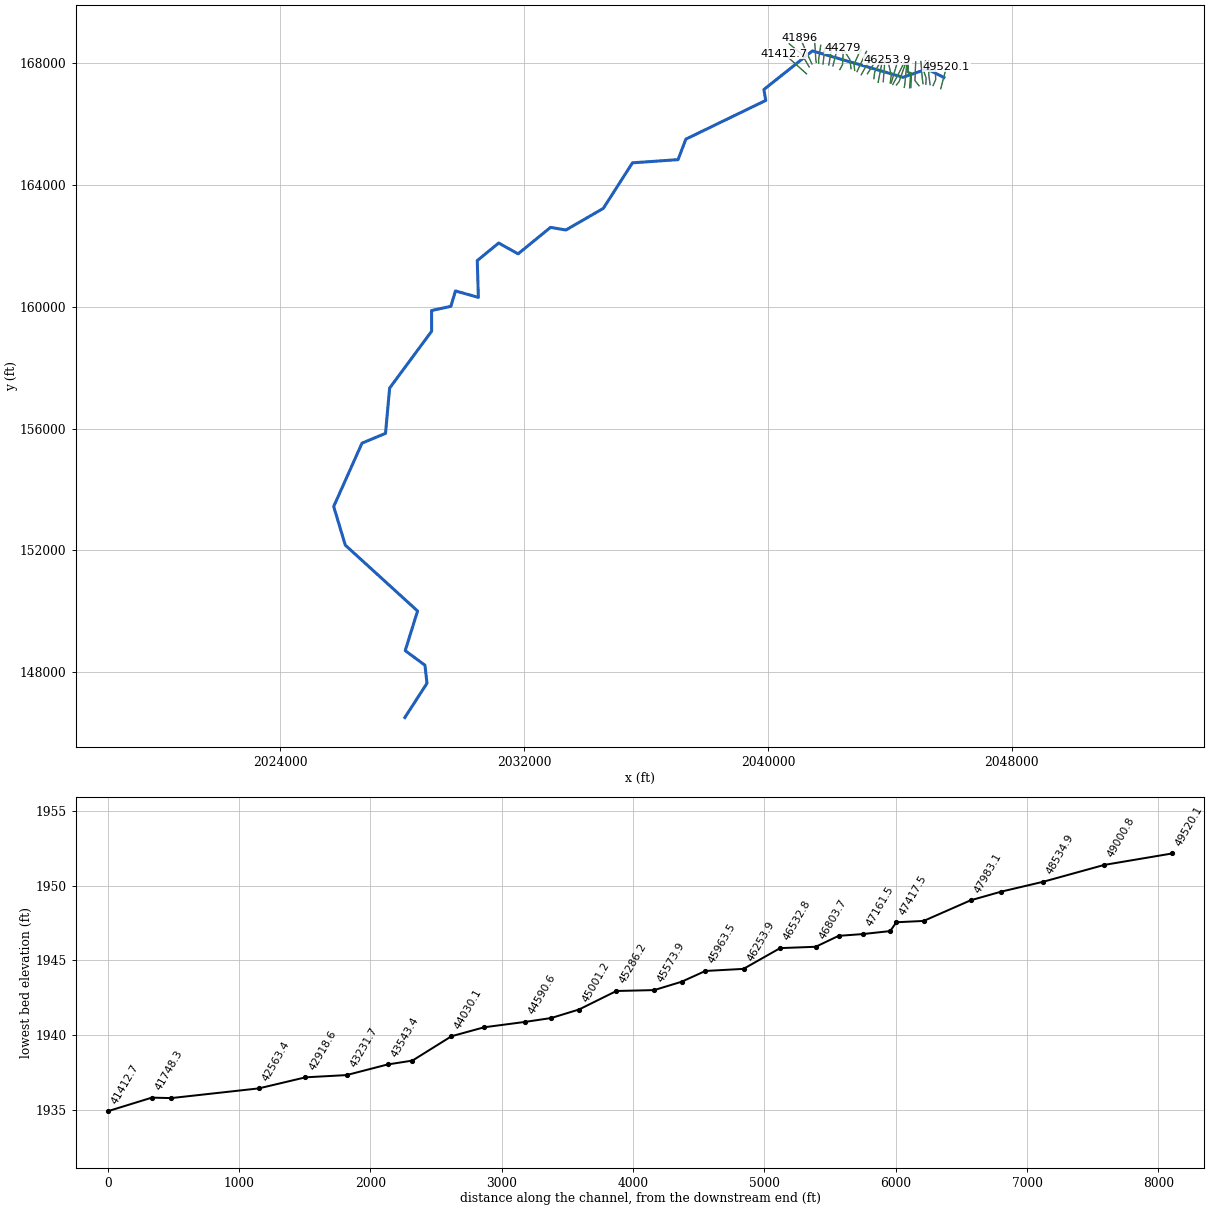
--- BRUSHCK.prj (project) ---

Proj Title=BRUSHCK
Current Plan=p01
Default Exp/Contr=0,0
English Units
Geom File=g01
Flow File=f01
Plan File=p01
BEGIN DESCRIPTION:
END DESCRIPTION:
DSS Export Rating Curves= 0
DSS Export Rating Curve Sorted= 0
DSS Export Volume Flow Curves= 0
DXF OffsetX= 0
DXF OffsetY= 0
DXF ScaleX= 0
DXF ScaleY= 0

--- BRUSHCK.p01 (plan) ---

Plan Title=Floodplain
Program Version=4.00
Geom File=g01
Flow File=f01
K Sum by GR=0
Std Step Tol=0.01
Critical Tol=0.01
Num of Std Step Trials=20
Max Error Tol=0.3
Flow Tol Ratio=0.001
Split Flow NTrial=30
Split Flow Tol=0.02
Split Flow Ratio=0.02
Log Output Level=0
Friction Slope Method=1
Unsteady Friction Slope Method=2
Unsteady Bridges Friction Slope Method=1
Global Log Level=0
CheckData=False
Run HTab=0
Run UNet=0
Run PostProcess=0
UNET Theta=0
UNET Theta Warmup=0
UNET ZTol=0
UNET ZSATol=0
UNET MxIter=0
UNET MaxInSteps=0
UNET DtIC=0
UNET DtMin=0
UNET MaxCRTS=0
UNET WFStab=0
UNET SFStab=0
UNET WFX=0
UNET SFX=0
UNET DSS MLevel=0
UNET DZMax Abort=0
UNET Convert EG Bridges=0
UNET Use Existing IB Tables=0
UNET Froude Limit=0
UNET Froude Power=0
Write IC File=0
Echo Input=False
Echo Output=False
Write Detailed=0

--- BRUSHCK.f01 (steady flow) ---

Flow Title=NFF Regression Equation
Program Version=4.10
Number of Profiles= 1
Profile Names=P100yr
River Rch & RM=BRUSHCK,Main            ,49520.1
497.9734
River Rch & RM=BRUSHCK,Main            ,48534.9
520.8372
River Rch & RM=BRUSHCK,Main            ,45963.5
577.1959
River Rch & RM=BRUSHCK,Main            ,41412.7
624.5061
River Rch & RM=BRUSHCK,Main            ,41065.1
916.1026
River Rch & RM=BRUSHCK,Main            ,37803.5
 991.171
River Rch & RM=BRUSHCK,Main            ,32197.9
1082.952
River Rch & RM=BRUSHCK,Main            ,30711
1200.855
River Rch & RM=BRUSHCK,Main            ,28841.8
1218.373
River Rch & RM=BRUSHCK,Main            ,28201.6
1433.366
River Rch & RM=BRUSHCK,Main            ,27321.5
1438.079
River Rch & RM=BRUSHCK,Main            ,26775
1622.848
River Rch & RM=BRUSHCK,Main            ,21230.9
1713.752
River Rch & RM=BRUSHCK,Main            ,16996.6
1903.172
River Rch & RM=BRUSHCK,Main            ,11258.7
2102.417
River Rch & RM=BRUSHCK,Main            ,11098.3
2332.798
River Rch & RM=BRUSHCK,Main            ,8299.2
 2523.03
River Rch & RM=BRUSHCK,Main            ,243.3
2725.124
Boundary for River Rch & Prof#=BRUSHCK,Main            , 1
Up Type= 0
Dn Type= 1
Dn Known WS=1676.8
DSS Import GetInterval= 0
DSS Import GetPeak= 0
DSS Import FillOption= 0

--- BRUSHCK.g01 (geometry) ---

Geom Title=USGS 10m DEM
Program Version=4.10

River Reach=BRUSHCK         ,Main
Reach XY= 30
      2045769.13       167516.93     2045217.004       167796.89
     2044429.244      167524.537     2041455.372       168388.99
     2039863.814      167122.324     2039924.231      166764.511
     2037303.875      165494.564     2037047.648      164822.336
     2035552.635      164717.617     2034595.496      163222.805
     2033368.739      162513.943     2032864.052      162599.881
      2031799.99      161732.173      2031163.01      162085.819
     2030460.927      161510.818     2030496.865      160302.659
     2029745.345      160515.333     2029594.521       160009.69
      2028961.99      159872.038     2028963.412      159192.394
     2027586.449       157328.29     2027450.411       155842.03
     2026680.012      155521.935     2025750.666      153443.343
     2026131.435      152175.711     2028502.191      150015.341
      2028096.89      148714.925     2028744.286        148236.8
     2028811.473      147644.439     2028084.272      146518.945

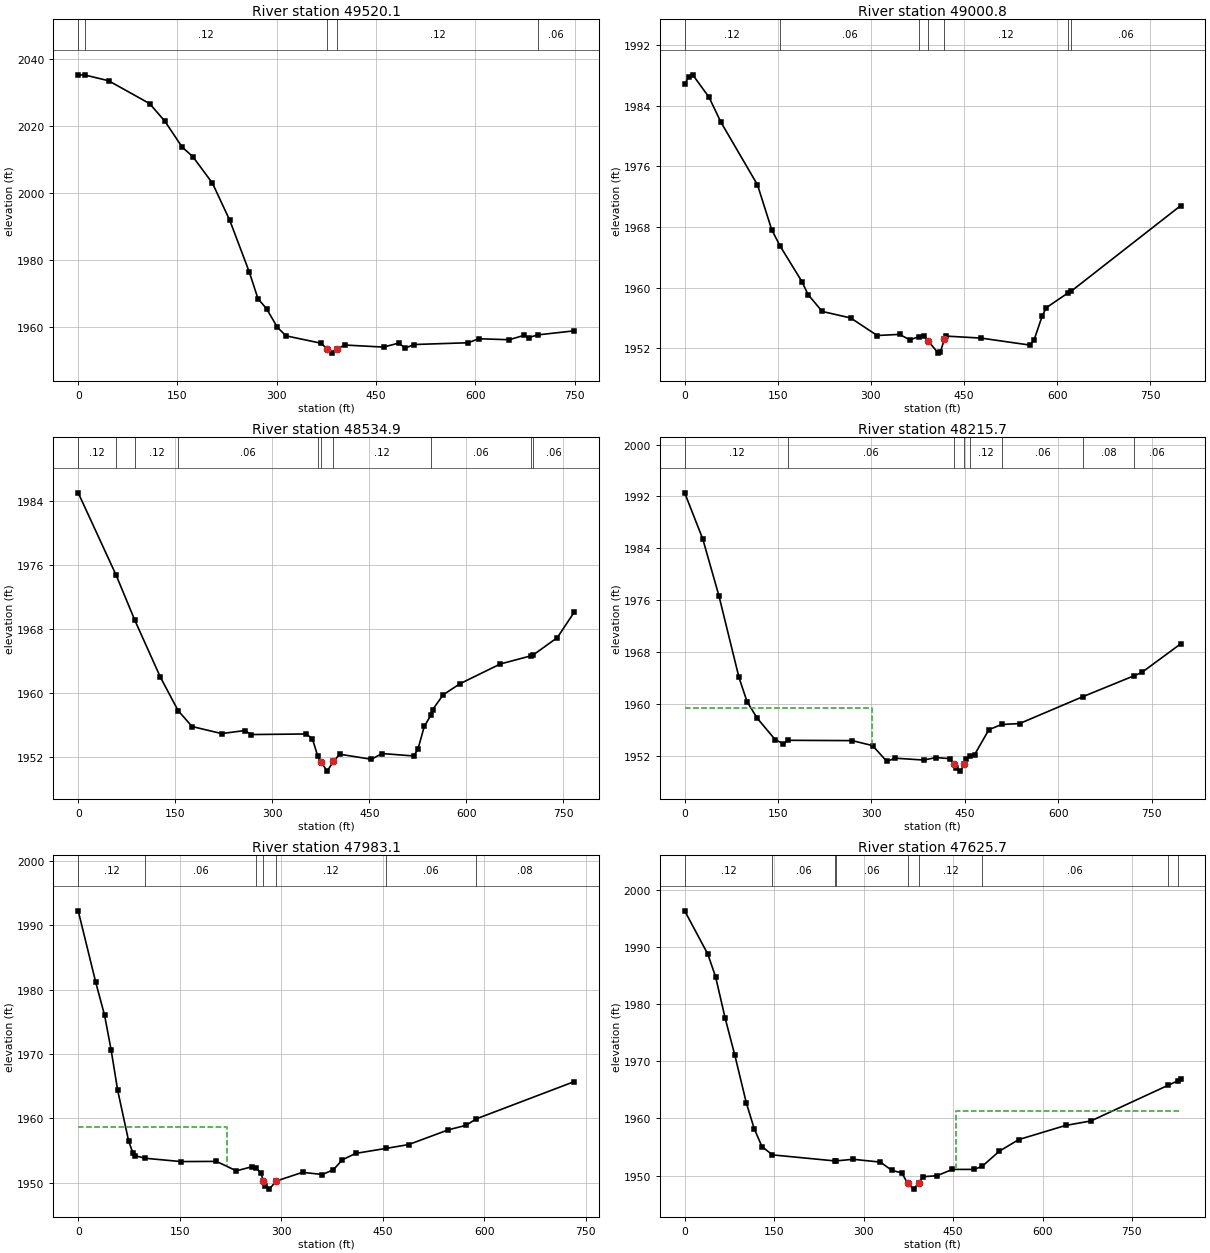
Type RM Length L Ch R = 1 ,49520.1 ,478.7,519.4,507.8
XS GIS Cut Line= 2
      2045665.69      167149.602      2045855.18      167874.609
#Sta/Elev= 30
       0 2035.33   10.472035.254    45.8 2033.57     108 2026.72   130.9 2021.47
   157.1 2013.73   173.4 2010.83   202.9 2002.93   229.1  1991.8   258.5  1976.4
   271.6 1968.44   284.7  1965.4     301 1959.85   314.1 1957.32   366.5 1955.14
   376.5  1953.4   382.9 1952.16   391.5 1953.41   402.5 1954.58   461.4 1953.97
   484.3 1955.16   494.1 1953.64   507.2 1954.73     589 1955.26   605.4 1956.46
   651.2 1956.16   674.1  1957.5   680.6 1956.82  695.071957.622   749.4 1958.82
#Mann= 5 ,-1 , 0
       0     .06       0   10.47     .12       0   376.5    .045       0
   391.5     .12       0  695.07     .06       0
Bank Sta=376.5,391.5
XS Rating Curve= 0 ,0
Exp/Cntr=0.3,0.1

Type RM Length L Ch R = 1 ,49000.8 ,442.4,465.9,483
XS GIS Cut Line= 3
     2045415.049      167253.417     2045499.783      167447.471
     2045477.058      168034.263
#Sta/Elev= 30
       0 1986.79     6.5 1987.78      13 1988.05    39.1 1985.11    58.6 1981.78
   117.3 1973.56   140.1 1967.67  153.481965.531   188.9 1960.81   198.7 1959.11
   221.6 1956.88   267.5 1956.02   310.2 1953.71   346.2 1953.86   362.7 1953.14
  377.591953.566   385.6  1953.7   392.2 1952.99   408.6 1951.39   411.9 1951.52
   418.4 1953.22   421.7 1953.63   477.5 1953.37   556.2 1952.45   562.8  1953.1
   575.9 1956.26   582.5 1957.37  616.981959.286   622.91959.563     799 1970.81
#Mann= 7 ,-1 , 0
       0     .12       0  153.48     .06       0  377.59     .12       0
   392.2    .045       0   418.4     .12       0  616.98     .08       0
   622.9     .06       0
Bank Sta=392.2,418.4
XS Rating Curve= 0 ,0
Exp/Cntr=0.3,0.1

Type RM Length L Ch R = 1 ,48534.9 ,310.7,319.2,326.2
XS GIS Cut Line= 3
      2045315.25      167282.595     2045275.319      167586.415
     2045266.639      168046.484
#Sta/Elev= 30
       0 1985.02   58.461974.764   87.641969.078   127.1 1961.98  154.41 1957.82
     176 1955.83   221.7 1954.95   257.5 1955.33   267.3 1954.83   352.1  1954.9
   361.9 1954.32  370.45 1952.09     375 1951.45   384.8 1950.26   394.6 1951.49
   404.3 1952.37   453.3 1951.74   469.6 1952.46   518.6 1952.15   525.1 1952.99
   534.9 1955.84  544.891957.216   547.9 1957.95   564.2  1959.8   590.4 1961.19
   652.4 1963.64  700.321964.671  702.231964.708   740.5 1966.93   766.6  1970.1
#Mann= 10 ,-1 , 0
       0     .12       0   58.46     .06       0   87.64     .12       0
  154.41     .06       0  370.45     .12       0     375    .045       0
   394.6     .12       0  544.89     .06       0  700.32     .08       0
  702.23     .06       0
Bank Sta=375,394.6
XS Rating Curve= 0 ,0
Exp/Cntr=0.3,0.1

Type RM Length L Ch R = 1 ,48215.7 ,240.1,232.6,219.8
XS GIS Cut Line= 4
     2045178.097      167296.484     2045185.041      167503.081
     2045075.666      167815.581     2045164.208      168058.637
#Sta/Elev= 30
       0 1992.56    29.1 1985.42    54.9  1976.7    87.2 1964.06   100.1 1960.34
   116.3 1957.79   145.4 1954.46   158.3 1953.84  166.681954.358     269 1954.31
   301.8 1953.54   324.7 1951.09   337.8  1951.6   383.7 1951.31   403.4 1951.69
   426.4 1951.53   432.4 1950.69   436.2 1950.03   442.7  1949.6   449.3 1950.73
   452.6 1951.46  458.961951.868   465.7 1952.16   488.6    1956  509.03  1956.8
   537.8 1956.94  639.931961.111  721.251964.302   734.3 1964.84   796.5 1969.24
#Mann= 8 ,-1 , 0
       0     .12       0  166.68     .06       0   432.4    .045       0
   449.3     .06       0  458.96     .12       0  509.03     .06       0
  639.93     .08       0  721.25     .06       0
#XS Ineff= 2 , 0
          301.19 1959.36
Permanent Ineff=
       F       F
Bank Sta=432.4,449.3
XS Rating Curve= 0 ,0
Exp/Cntr=0.3,0.1

Type RM Length L Ch R = 1 ,47983.1 ,357.8,357.4,358.5
XS GIS Cut Line= 3
     2045084.347      167313.845     2045060.041      167480.512
     2045013.166      168043.012
#Sta/Elev= 30
       0 1992.26    25.9 1981.15    38.9 1976.06    48.6 1970.67    58.3 1964.38
    74.5 1956.49      81 1954.57    84.2 1954.21    99.21953.814   152.2  1953.3
   204.3 1953.33   233.7 1951.86   256.5 1952.49  262.041952.374   269.6 1951.56
   273.7 1950.35   276.1 1949.56   282.6 1949.02   292.4 1950.27   331.6 1951.63
   360.9 1951.29   377.2 1952.04   390.3 1953.57   409.9 1954.57  454.49 1955.34
   488.2 1955.94   546.9 1958.23     573 1958.93  588.311959.937   732.9 1965.72
#Mann= 7 ,-1 , 0
       0     .12       0    99.2     .06       0  262.04     .12       0
   273.7    .045       0   292.4     .12       0  454.49     .06       0
  588.31     .08       0
#XS Ineff= 2 , 0
          219.79 1958.71
Permanent Ineff=
       F       F
Bank Sta=273.7,292.4
XS Rating Curve= 0 ,0
Exp/Cntr=0.3,0.1

Type RM Length L Ch R = 1 ,47625.7 ,169.9,208.2,226
XS GIS Cut Line= 3
     2044953.227      167246.097     2044818.722      167416.276
     2044843.156      168030.462
#Sta/Elev= 30
       0 1996.33    38.8 1988.75    51.8  1984.8      68  1977.5    84.2 1971.02
   103.6 1962.63   116.6 1958.22   129.5 1955.09  147.16 1953.63   252.31952.572
  253.621952.574   282.3 1952.86   328.1 1952.37   347.7  1950.9     364 1950.49
   373.8 1948.66   383.7 1947.64   392.4 1948.72     400 1949.82   422.9 1949.98
     449 1951.09     485 1951.09  498.771951.619   527.5 1954.27   560.2 1956.31
   638.7 1958.78   681.2 1959.57  810.341965.795   827.61966.618   831.6 1966.83
#Mann= 9 ,-1 , 0
       0     .12       0  147.16     .06       0   252.3     .12       0
  253.62     .06       0   373.8    .045       0   392.4     .12       0
  498.77     .06       0  810.34     .08       0   827.6     .06       0
#XS Ineff= 2 , 0
                          455.06         1961.36
Permanent Ineff=
       F       F
Bank Sta=373.8,392.4
XS Rating Curve= 0 ,0
Exp/Cntr=0.3,0.1

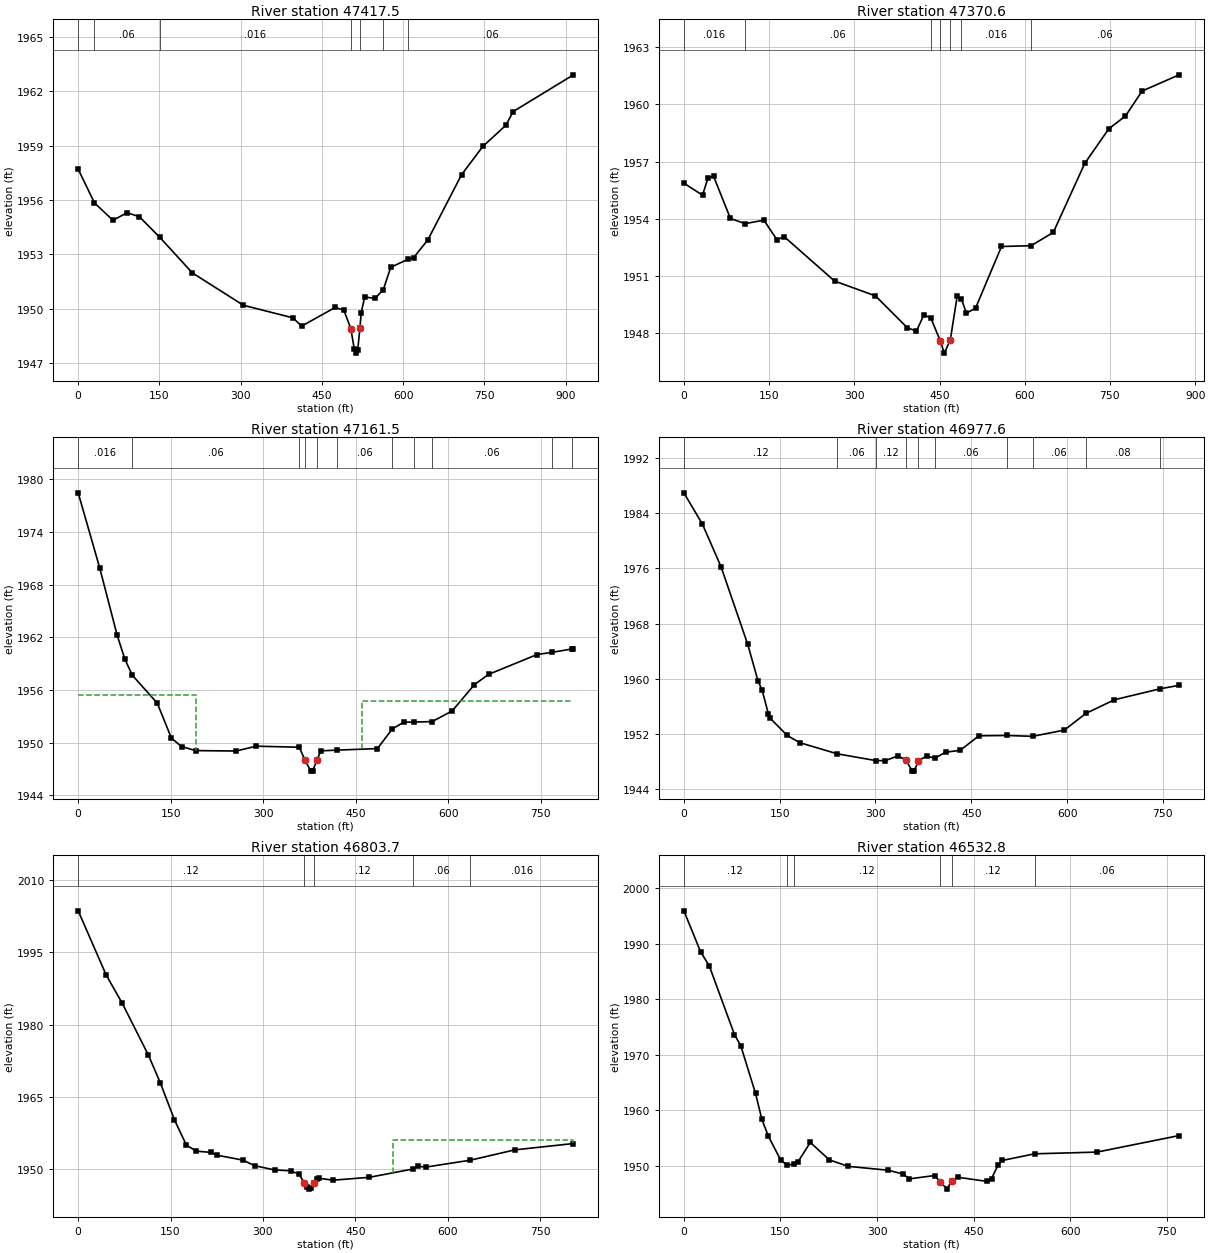
Type RM Length L Ch R = 1 ,47417.5 ,125.6,46.9,40.7
XS GIS Cut Line= 5
     2044686.414      167187.629     2044686.777      167232.248
     2044702.876      167665.021     2044592.159      167707.943
      2044605.18      168025.651
#Sta/Elev= 30
       0  1957.7   30.091955.842    64.2 1954.88    90.2  1955.3     113 1955.08
  150.871953.936   210.7 1951.98   305.1 1950.19   396.3  1949.5   412.6 1949.04
   474.4 1950.07   490.5 1949.92   503.4  1948.9   509.8 1947.77     513 1947.55
   516.2 1947.74   520.2 1948.94   522.6 1949.79     529 1950.65   548.3 1950.57
  563.361951.057   577.2 1952.29  608.261952.718   619.4 1952.82   645.6  1953.8
   707.9  1957.4   747.2 1958.96   789.8 1960.13     803 1960.88   914.4 1962.91
#Mann= 7 ,-1 , 0
       0     .12       0   30.09     .06       0  150.87    .016       0
   503.4    .045       0   520.2     .12       0  563.36    .016       0
  608.26     .06       0
Bank Sta=503.4,520.2
XS Rating Curve= 0 ,0
Exp/Cntr=0.3,0.1

Type RM Length L Ch R = 1 ,47370.6 ,168.4,209.1,188.6
XS GIS Cut Line= 4
     2044644.747      167178.948     2044677.269      167626.392
     2044571.831      167684.156     2044579.573      167987.022
#Sta/Elev= 30
       0 1955.87    32.8 1955.24    42.6 1956.16    52.4 1956.22    81.9 1954.02
  107.631953.749   140.8 1953.93   163.7 1952.91   176.8 1953.06   265.2 1950.74
   337.3 1949.96     393  1948.3   409.3 1948.11   422.4 1948.96  434.661948.806
   451.1 1947.62   458.4 1946.96     469 1947.65   481.1 1949.95  488.581949.798
   497.4 1949.05   513.6 1949.33   559.1 1952.55  611.131952.591   650.3 1953.29
   705.7 1956.91     748 1958.72   777.3 1959.39   806.7  1960.7   871.8 1961.55
#Mann= 7 ,-1 , 0
       0    .016       0  107.63     .06       0  434.66     .12       0
   451.1    .045       0     469     .12       0  488.58    .016       0
  611.13     .06       0
Bank Sta=451.1,469
XS Rating Curve= 0 ,0
Exp/Cntr=0.3,0.1

Type RM Length L Ch R = 1 ,47161.5 ,188,184,185.4
XS GIS Cut Line= 3
     2044468.462       167193.62     2044484.087      167267.838
     2044554.399      167991.797
#Sta/Elev= 30
       0 1978.46    34.8 1969.94    63.2 1962.24    75.8  1959.5   87.691957.693
   128.3  1954.5   151.2 1950.52   167.6 1949.56   190.5  1949.1     256 1949.05
   288.8  1949.6  358.651949.483   367.4 1948.07   377.3 1946.76   380.6 1946.82
   387.1 1948.02   393.7 1949.07  420.331949.153   485.4 1949.33  509.281951.551
     528 1952.34   544.4 1952.35  574.081952.402   606.6 1953.62   642.7 1956.62
   665.6 1957.78   744.2 1960.04  769.091960.298  801.34 1960.68   803.2 1960.68
#Mann= 11 ,-1 , 0
       0    .016       0   87.69     .06       0  358.65     .12       0
   367.4    .045       0   387.1     .12       0  420.33     .06       0
  509.28    .016       0   544.4     .08       0  574.08     .06       0
  769.09     .08       0  801.34     .06       0
#XS Ineff= 2 , 0
           190.5 1955.38  460.15         1954.75
Permanent Ineff=
       F       F
Bank Sta=367.4,387.1
XS Rating Curve= 0 ,0
Exp/Cntr=0.3,0.1

Type RM Length L Ch R = 1 ,46977.6 ,148.8,173.9,160.8
XS GIS Cut Line= 3
     2044210.649      167273.047     2044299.191      167379.818
      2044511.43      167980.078
#Sta/Elev= 30
       0 1986.95      29 1982.42    58.1 1976.26     100 1964.99   116.1  1959.7
   122.6 1958.34   132.3 1954.93   135.5 1954.27   161.6 1951.82   181.2 1950.77
  240.131949.145  300.451948.169     315 1948.15   334.6 1948.83   347.7 1948.27
   357.5 1946.64   360.7 1946.69   367.3 1948.15   380.3 1948.83  392.731948.506
   409.7 1949.38   432.6 1949.65   461.9 1951.76  505.911951.804  545.921951.676
   595.8 1952.59  629.351954.998   674.2 1956.98  745.291958.558   775.4 1959.07
#Mann= 10 ,-1 , 0
       0     .12       0  240.13     .06       0  300.45     .12       0
   347.7    .045       0   367.3     .12       0  392.73     .06       0
  505.91    .016       0  545.92     .06       0  629.35     .08       0
  745.29     .06       0
Bank Sta=347.7,367.3
XS Rating Curve= 0 ,0
Exp/Cntr=0.3,0.1

Type RM Length L Ch R = 1 ,46803.7 ,249.8,270.9,317.7
XS GIS Cut Line= 3
     2044093.519      167286.278     2044271.555      167623.131
     2044462.591      168000.778
#Sta/Elev= 30
       0  2003.6    45.6 1990.26    71.6 1984.43     114  1973.7   133.5  1967.9
   156.3 1960.28   175.8 1955.01   192.1 1953.77   214.9 1953.54   224.7 1952.96
     267 1951.94   286.6 1950.77   319.1 1949.88   345.2 1949.71   358.2 1949.03
   367.4 1947.26   371.2 1946.28   374.5 1945.91   377.8 1946.07   382.4 1947.15
   387.6 1948.04   390.8 1948.17   413.8 1947.76   472.9 1948.36  543.561950.081
   551.6 1950.65   564.7 1950.48  636.541951.902   709.1 1954.05   804.2 1955.36
#Mann= 5 ,-1 , 0
       0     .12       0   367.4    .045       0   382.4     .12       0
  543.56     .06       0  636.54    .016       0
#XS Ineff= 2 , 0
                          510.46         1956.17
Permanent Ineff=
       F       F
Bank Sta=367.4,382.4
XS Rating Curve= 0 ,0
Exp/Cntr=0.3,0.1

Type RM Length L Ch R = 1 ,46532.8 ,260.7,279,239.7
XS GIS Cut Line= 2
     2044040.742      167336.465     2044258.826      168073.828
#Sta/Elev= 30
       0 1995.95    26.2 1988.51    39.3 1986.07    78.5 1973.67    88.4 1971.62
   111.2 1963.07   121.1 1958.38   130.9 1955.43   150.5    1951  159.751950.194
  171.611950.269   176.7 1950.66   196.3 1954.23   225.8 1951.09   255.2 1949.92
   317.4 1949.22   340.3 1948.54   350.1 1947.67   389.4 1948.27     398  1947.1
     409 1945.82   415.6 1947.36   425.4 1947.96   471.2  1947.2   477.7 1947.73
   487.5 1950.09   494.1 1950.98  544.44 1952.18   641.3 1952.49   768.9 1955.47
#Mann= 6 ,-1 , 0
       0     .12       0  159.75     .06       0  171.61     .12       0
     398    .045       0   415.6     .12       0  544.44     .06       0
Bank Sta=398,415.6
XS Rating Curve= 0 ,0
Exp/Cntr=0.3,0.1

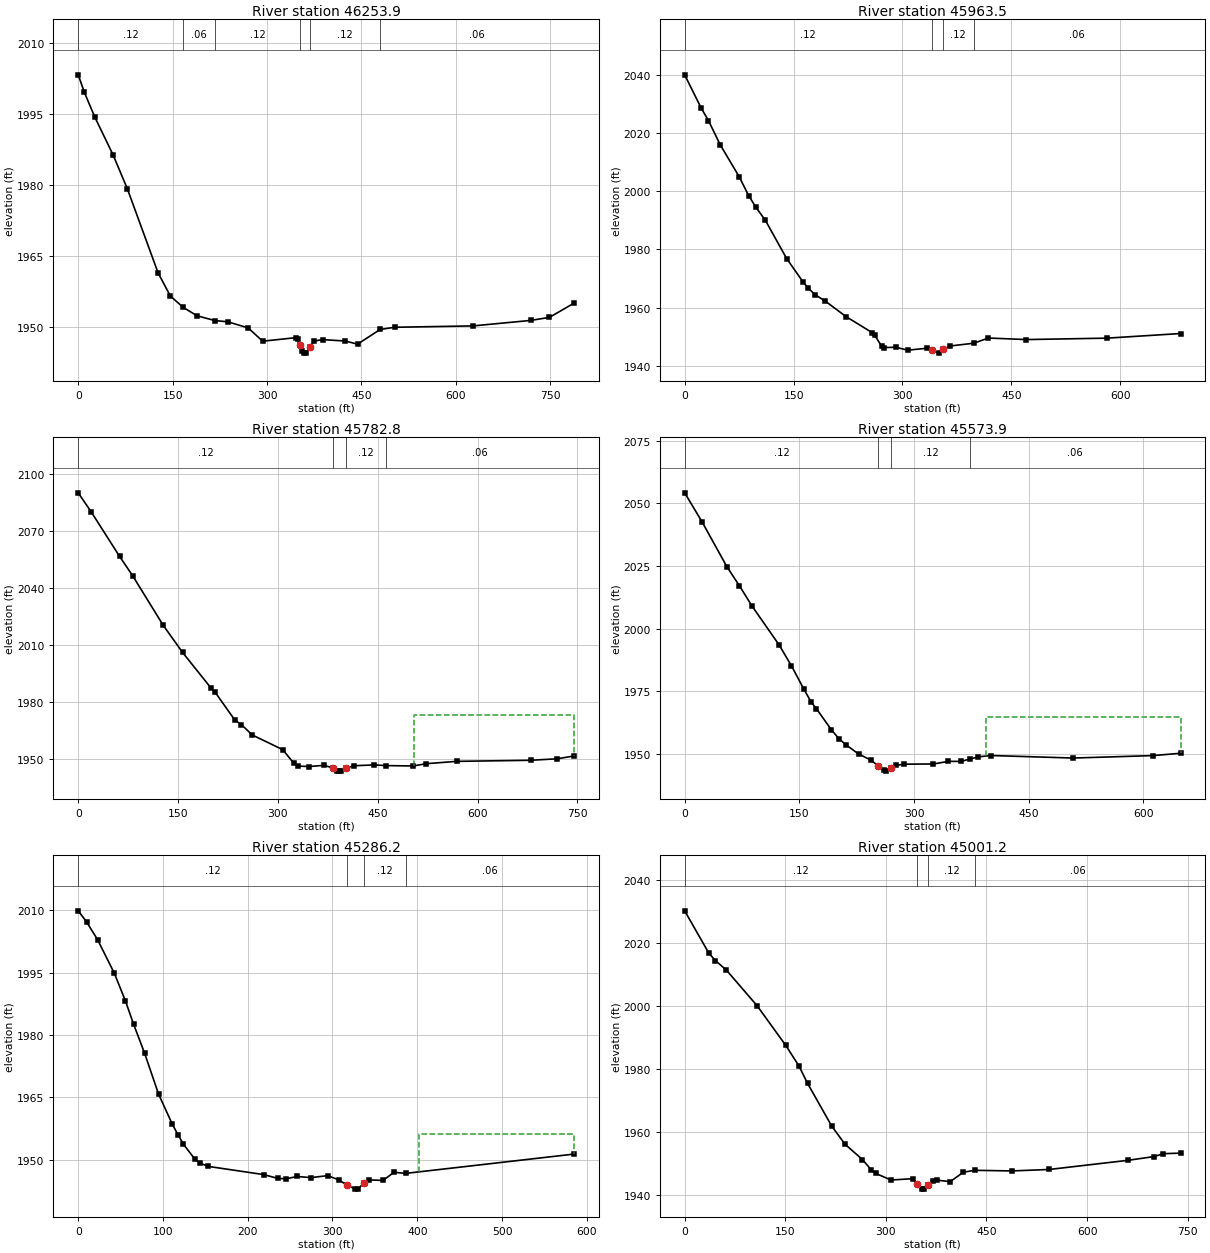
Type RM Length L Ch R = 1 ,46253.9 ,318.6,290.3,271.5
XS GIS Cut Line= 3
     2044007.508      167334.572     2044041.378      167595.963
     2043920.675       168106.43
#Sta/Elev= 30
       0  2003.2     9.8  1999.5      26 1994.38    55.3 1986.32    78.1 1979.13
   126.9 1961.39   146.4 1956.49  166.531954.124   188.7 1952.32  217.551951.294
   237.5 1951.05   270.1 1949.76   293.1 1946.95   345.5 1947.69   348.8 1947.32
   352.1 1946.07   355.4 1944.84   358.6 1944.43   361.9 1944.53   368.5 1945.78
     375 1946.99   388.2 1947.28   424.2 1946.99   443.9 1946.33  479.851949.428
   502.9 1949.89   627.5 1950.18   719.3 1951.34   748.8 1951.98   788.1    1955
#Mann= 6 ,-1 , 0
       0     .12       0  166.53     .06       0  217.55     .12       0
   352.1    .045       0   368.5     .12       0  479.85     .06       0
Bank Sta=352.1,368.5
XS Rating Curve= 0 ,0
Exp/Cntr=0.3,0.1

Type RM Length L Ch R = 1 ,45963.5 ,149.5,180.7,173.7
XS GIS Cut Line= 2
     2043778.357      167378.515     2043831.743      168059.505
#Sta/Elev= 30
       0 2040.12    22.9  2028.6    32.7 2024.39      49 2016.01    75.2 2004.98
    88.2 1998.49      98 1994.56   111.1 1990.04   140.5 1976.83   163.4 1968.68
     170 1966.74   179.8 1964.36   192.8 1962.36   222.2 1956.88   258.2 1951.35
   261.5 1950.54   271.3 1946.67   274.5 1946.19   290.9 1946.32   307.2 1945.31
   333.4 1945.96   340.3 1945.47   349.7 1944.29   355.3 1945.56     366 1946.76
  398.181947.701   418.3 1949.49   470.6 1948.96   581.8 1949.45   683.1 1951.04
#Mann= 4 ,-1 , 0
       0     .12       0   340.3    .045       0   355.3     .12       0
  398.18     .06       0
Bank Sta=340.3,355.3
XS Rating Curve= 0 ,0
Exp/Cntr=0.3,0.1

Type RM Length L Ch R = 1 ,45782.8 ,219.8,208.9,195.2
XS GIS Cut Line= 2
     2043610.825      167356.942     2043753.618      168088.151
#Sta/Elev= 30
       0 2089.98    19.6 2079.91    62.1 2056.55    81.7  2046.4   127.4 2020.44
   156.8 2005.99   199.3 1987.38   205.9 1984.96   235.3 1970.42   245.1 1968.06
   261.4  1962.6   307.2 1954.87   323.5 1947.87     330 1946.24   346.4 1945.99
   369.2 1946.61   382.3 1945.31   388.8 1943.81   392.1 1943.57   395.4 1943.75
   402.1 1945.21     415 1946.41   444.4 1946.84  462.871946.484   503.2 1946.28
   522.8 1947.49   568.6 1948.71   679.7 1949.28   718.9 1950.05     745 1951.54
#Mann= 4 ,-1 , 0
       0     .12       0   382.3    .045       0   402.1     .12       0
  462.87     .06       0
#XS Ineff= 2 , 0
                          503.79         1973.14
Permanent Ineff=
       F       F
Bank Sta=382.3,402.1
XS Rating Curve= 0 ,0
Exp/Cntr=0.3,0.1

Type RM Length L Ch R = 1 ,45573.9 ,270.6,287.8,280.8
XS GIS Cut Line= 3
     2043472.368      167480.078     2043498.409      167696.224
     2043710.649      168071.224
#Sta/Elev= 30
       0 2054.22    22.8 2042.59    55.2 2024.69    71.5 2017.13    87.7 2009.14
   123.5 1993.44   139.7 1985.06     156 1975.69   165.7 1970.45   172.2    1968
   191.7  1959.6   201.5 1956.03   211.2 1953.47   227.5 1949.84   243.8 1947.39
   253.2 1945.04   260.2 1943.36   263.4 1943.01   269.9 1944.45   276.5  1945.3
   286.3 1945.79   325.4 1945.87     345 1946.92   361.3 1946.89  372.861947.815
   384.2 1948.72   400.5 1949.25   508.2 1948.24   612.7 1949.22   648.6 1950.15
#Mann= 4 ,-1 , 0
       0     .12       0   253.2    .045       0   269.9     .12       0
  372.86     .06       0
#XS Ineff= 2 , 0
                          394.52         1964.57
Permanent Ineff=
       F       F
Bank Sta=253.2,269.9
XS Rating Curve= 0 ,0
Exp/Cntr=0.3,0.1

Type RM Length L Ch R = 1 ,45286.2 ,283.9,284.9,287.8
XS GIS Cut Line= 2
     2043260.128      167640.234     2043576.534      168132.422
#Sta/Elev= 30
       0 2009.87     9.8 2007.23    22.9 2002.91    42.5 1994.91    55.6 1988.27
    65.4 1982.58    78.4 1975.59    94.8  1965.8   111.1 1958.53   117.7 1956.03
   124.2 1953.73   137.3 1950.25   143.8 1949.19   153.6 1948.41     219 1946.44
   235.4 1945.53   245.2 1945.43   258.2 1945.99   274.6 1945.72   294.2 1946.19
   307.3 1945.19   317.1 1943.92   326.9 1942.95   330.2 1942.95   336.7 1944.41
   343.2 1945.16   359.6 1945.05   372.6    1947  386.331946.736   585.1 1951.38
#Mann= 4 ,-1 , 0
       0     .12       0   317.1    .045       0   336.7     .12       0
  386.33     .06       0
#XS Ineff= 2 , 0
                           402.6         1956.25
Permanent Ineff=
       F       F
Bank Sta=317.1,336.7
XS Rating Curve= 0 ,0
Exp/Cntr=0.3,0.1

Type RM Length L Ch R = 1 ,45001.2 ,209,211.6,207.8
XS GIS Cut Line= 2
     2043057.877      167606.607     2043413.774      168254.818
#Sta/Elev= 30
       0 2030.29      36 2016.83    45.8 2014.47    62.2 2011.42     108 2000.08
   150.5 1987.52   170.2 1980.99   183.2 1975.38   219.2 1961.79   238.9 1956.04
     265 1951.13   278.1 1947.87   284.7 1946.72   307.6 1944.61   340.3 1945.04
     347 1943.41   353.4 1941.74   356.6 1941.71   363.2 1943.08   369.7 1944.21
   376.3 1944.56   395.9 1944.09   415.6 1947.09  432.23  1947.7   487.5  1947.5
   543.2 1947.96     661 1950.88   700.2 1952.08   713.3 1952.99   739.5 1953.17
#Mann= 4 ,-1 , 0
       0     .12       0     347    .045       0   363.2     .12       0
  432.23     .06       0
Bank Sta=347,363.2
XS Rating Curve= 0 ,0
Exp/Cntr=0.3,0.1

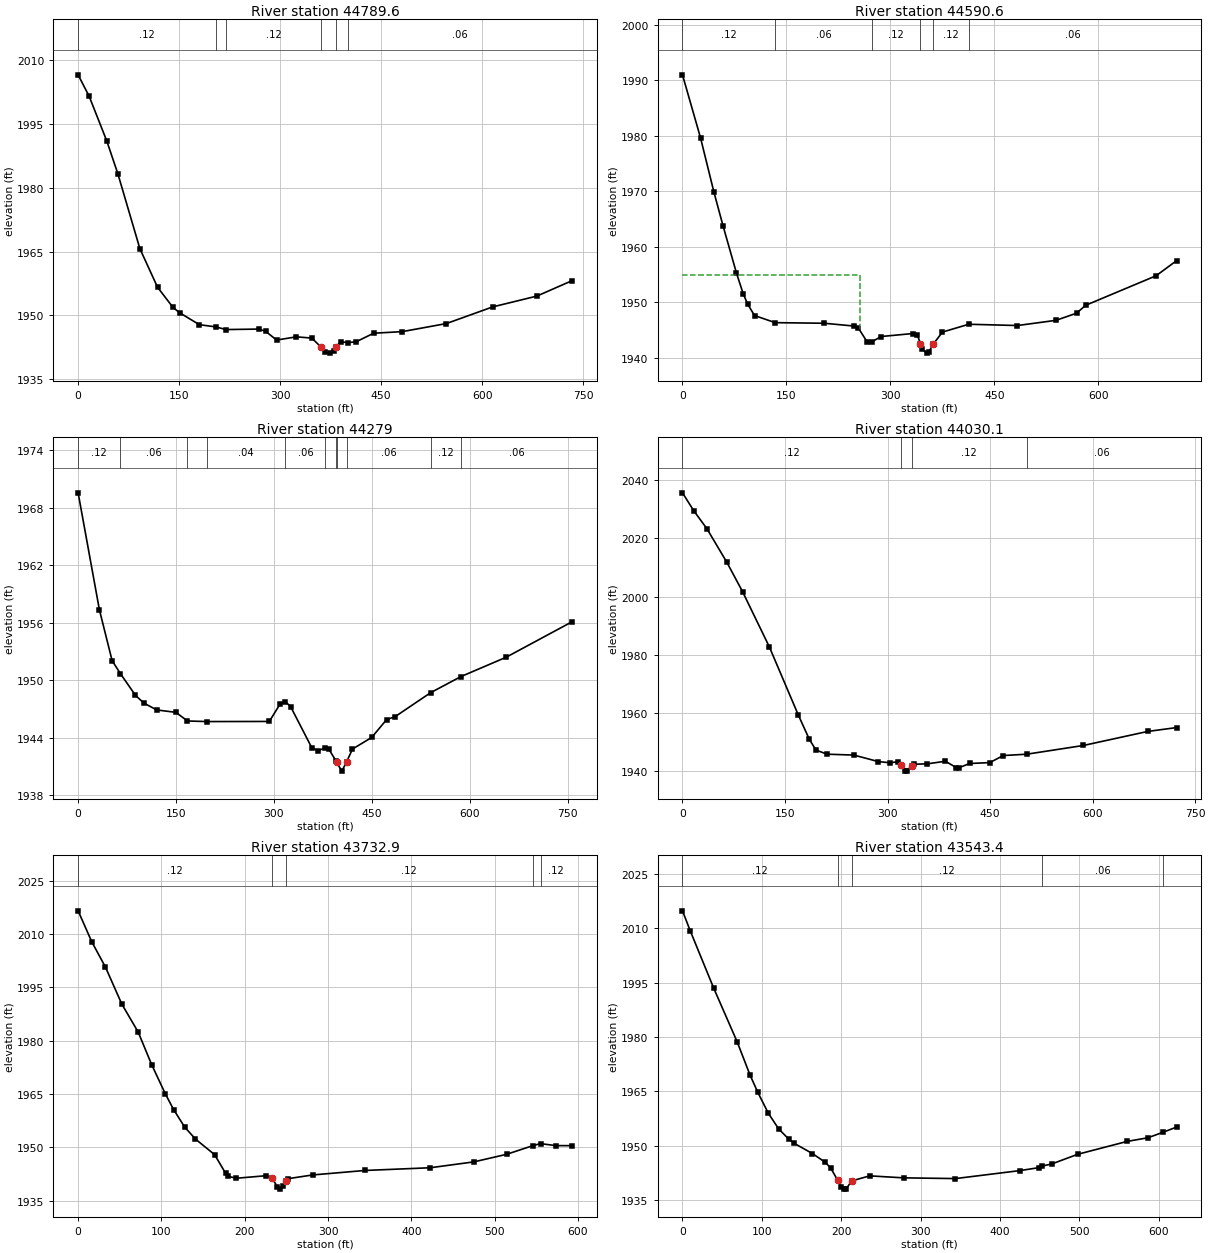
Type RM Length L Ch R = 1 ,44789.6 ,198.2,199.1,199.3
XS GIS Cut Line= 2
     2042918.883      167709.892     2043230.334      168374.072
#Sta/Elev= 30
       0 2006.62    16.4 2001.57    42.6 1991.04      59 1983.35    91.7 1965.72
   117.9 1956.66   140.8 1951.91   150.6 1950.65   180.1 1947.83  204.021947.326
  219.831946.684   268.5  1946.8   278.4 1946.28   294.7 1944.22   324.2 1944.97
   347.1 1944.68   360.2 1942.64   366.8 1941.34   373.3 1941.14   379.9 1941.61
   383.2 1942.63   389.7 1943.81  400.63 1943.63   412.6 1943.79   438.8 1945.82
   481.4  1946.2   546.9  1948.1   615.7 1952.02   681.2 1954.56   733.6  1958.2
#Mann= 6 ,-1 , 0
       0     .12       0  204.02     .06       0  219.83     .12       0
   360.2    .045       0   383.2     .12       0  400.63     .06       0
Bank Sta=360.2,383.2
XS Rating Curve= 0 ,0
Exp/Cntr=0.3,0.1

Type RM Length L Ch R = 1 ,44590.6 ,289.3,311.6,333.8
XS GIS Cut Line= 3
     2042842.159      167749.609     2042818.722      167946.224
     2043030.962      168414.974
#Sta/Elev= 30
       0    1991      26 1979.67    45.4 1969.86    58.4 1963.85    77.9 1955.29
    87.6 1951.57    94.1 1949.69   103.9 1947.65   133.81946.367   204.6 1946.26
   247.2 1945.76   253.7 1945.39   266.8 1942.82  273.39 1942.93   286.5 1943.87
   332.4 1944.41   338.9 1944.11  343.24 1942.57   345.5 1941.64     352 1940.88
   355.3  1941.1   361.9 1942.53     375 1944.67   412.91946.079   483.2 1945.85
   538.9 1946.79   568.4 1948.07   581.5 1949.49   683.1 1954.81   712.6 1957.52
#Mann= 6 ,-1 , 0
       0     .12       0   133.8     .06       0  273.39     .12       0
  343.24    .045       0   361.9     .12       0   412.9     .06       0
#XS Ineff= 2 , 0
          255.96 1954.93
Permanent Ineff=
       F       F
Bank Sta=343.24,361.9
XS Rating Curve= 0 ,0
Exp/Cntr=0.3,0.1

Type RM Length L Ch R = 1 ,44279   ,262.7,248.9,232.9
XS GIS Cut Line= 3
      2042723.67      167804.297     2042683.305      168107.682
     2042438.785      168486.651
#Sta/Elev= 30
       0 1969.54    32.6 1957.35    52.1 1952.04   64.841950.684    87.9 1948.42
   100.9 1947.61   120.5  1946.9   149.8 1946.65   167.6 1945.75   197.41945.688
     293  1945.7   309.3 1947.49  317.611947.768   325.7 1947.24   358.4 1942.92
   368.2 1942.66  378.84 1942.96   384.5 1942.79  395.511941.541   396.3 1941.43
   404.1 1940.52   411.3 1941.46   420.4 1942.82   449.9 1944.03   472.7 1945.89
   485.8  1946.2  540.291948.703  586.39 1950.37   655.8 1952.39   757.1  1956.1
#Mann= 11 ,-1 , 0
       0     .12       0   64.84     .06       0   167.6     .12       0
   197.4     .04       0  317.61     .06       0  378.84     .12       0
  395.51     .06       0   396.3    .045       0   411.3     .06       0
  540.29     .12       0  586.39     .06       0
Bank Sta=396.3,411.3
XS Rating Curve= 0 ,0
Exp/Cntr=0.3,0.1

Type RM Length L Ch R = 1 ,44030.1 ,301,297.2,293.3
XS GIS Cut Line= 4
     2042356.482      167776.953     2042443.266      167940.969
     2042461.951      168279.557     2042421.587      168473.568
#Sta/Elev= 30
       0 2035.67    16.3 2029.58    35.8  2023.3    65.1  2011.7    87.9 2001.67
     127 1982.71   169.3 1959.32   185.6 1950.86   195.3 1947.17   211.6 1945.75
   250.8 1945.44   286.6  1943.2   302.9 1942.81     316 1943.15   320.1 1942.14
   325.8 1939.92     329  1940.1   335.1 1941.83   338.8 1942.29   358.4 1942.43
   384.5 1943.32   400.8 1941.13     404 1941.04   420.3 1942.55   449.7 1942.85
   469.2 1945.28  503.741945.746   586.4 1948.74   680.6 1953.57   722.8  1954.9
#Mann= 4 ,-1 , 0
       0     .12       0   320.1    .045       0   335.1     .12       0
  503.74     .06       0
Bank Sta=320.1,335.1
XS Rating Curve= 0 ,0
Exp/Cntr=0.3,0.1

Type RM Length L Ch R = 1 ,43732.9 ,186.6,189.5,190
XS GIS Cut Line= 2
     2042128.618      167898.047     2042275.073      168472.552
#Sta/Elev= 30
       0 2016.52    16.4 2007.81    32.8  2000.7    52.4 1990.33    72.1 1982.42
    88.4 1973.21   104.8 1965.02   114.6 1960.66   127.8 1955.76   140.8 1952.37
   163.8 1947.98   176.9 1942.79   180.2 1941.88     190 1941.35     226 1942.07
   232.6 1941.46   239.1 1938.95   242.4 1938.29   245.7 1939.06   248.9 1940.51
   252.2 1941.24   281.7 1942.28   343.9 1943.53   422.6  1944.3     475 1945.95
   514.3 1948.08  545.651950.504  554.931951.086   573.2 1950.52   592.9 1950.51
#Mann= 5 ,-1 , 0
       0     .12       0   232.6    .045       0   248.9     .12       0
  545.65     .06       0  554.93     .12       0
Bank Sta=232.6,248.9
XS Rating Curve= 0 ,0
Exp/Cntr=0.3,0.1

Type RM Length L Ch R = 1 ,43543.4 ,299.3,311.7,313.9
XS GIS Cut Line= 2
     2041993.201      167926.693     2042099.972      168539.974
#Sta/Elev= 30
       0 2014.79     9.8 2009.26    39.3 1993.49    68.8 1978.71    85.2 1969.46
      95 1964.69   108.1 1958.99   121.2 1954.64   134.3 1951.75   140.9 1950.64
   163.8 1947.84   180.2 1945.38   186.8 1943.82   195.5 1940.52   199.9 1938.55
   203.1 1938.03   206.4  1938.1     213 1940.28   235.9 1941.69   278.5 1941.14
     344 1940.94   425.9 1943.16   448.9 1943.95  452.611944.373   465.2 1944.96
     498 1947.64   560.3 1951.19   586.5  1952.2  605.871953.736   622.5 1955.14
#Mann= 5 ,-1 , 0
       0     .12       0   195.5    .045       0     213     .12       0
  452.61     .06       0  605.87     .12       0
Bank Sta=195.5,213
XS Rating Curve= 0 ,0
Exp/Cntr=0.3,0.1

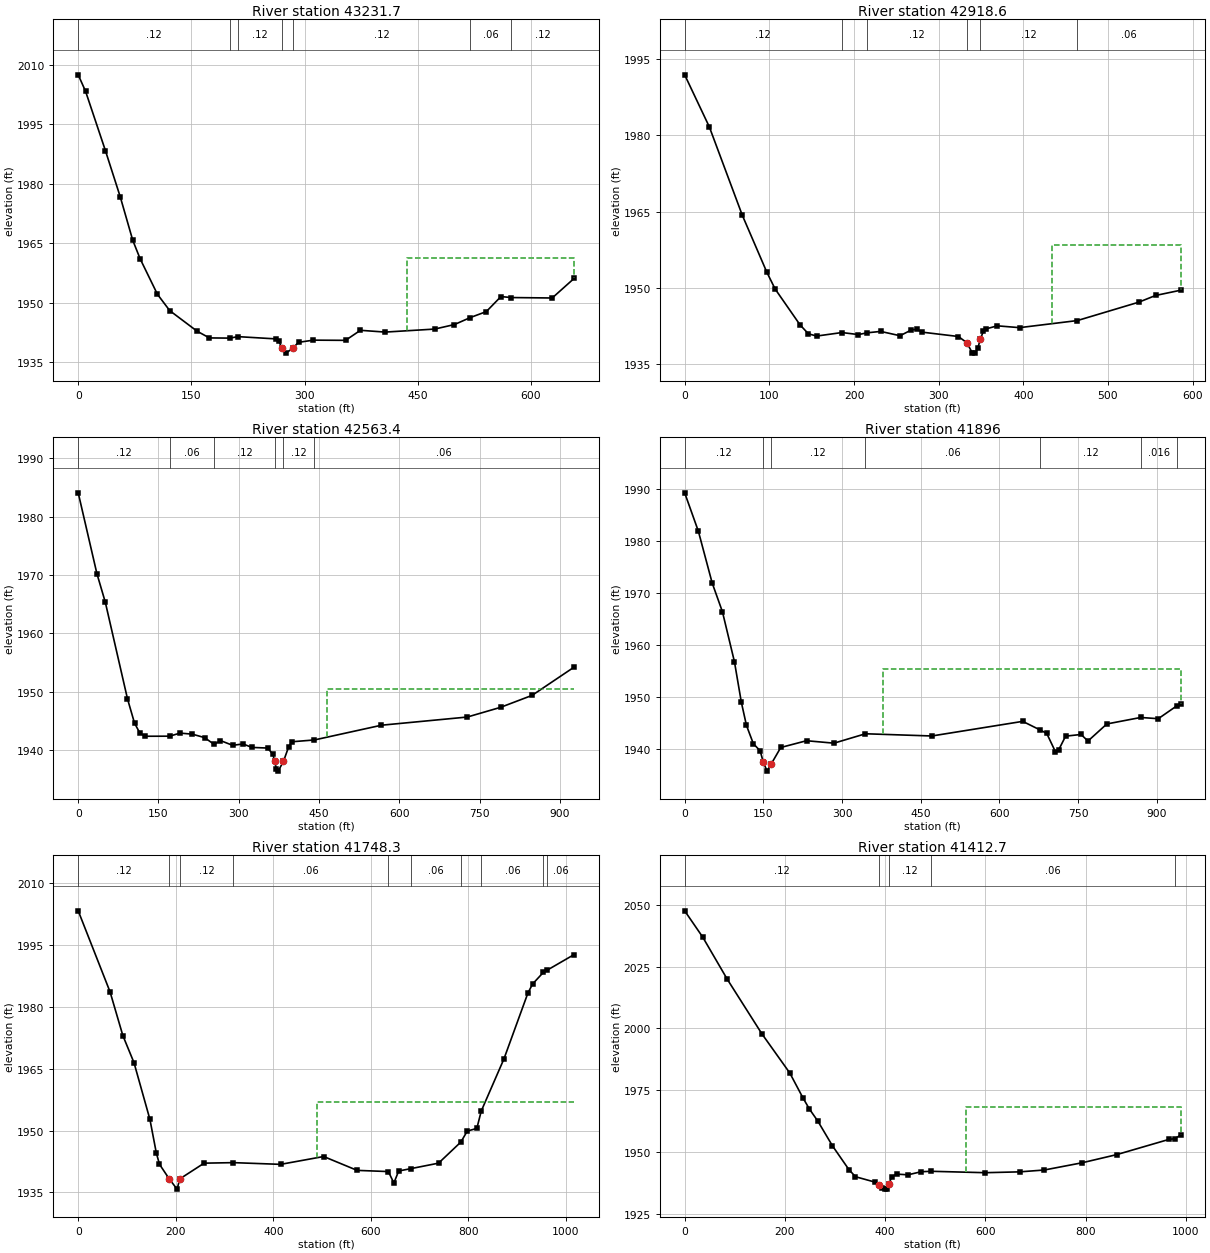
Type RM Length L Ch R = 1 ,43231.7 ,313.6,313.1,308.1
XS GIS Cut Line= 3
     2041803.097      167957.943     2041861.712      168466.189
     2041971.066      168562.109
#Sta/Elev= 30
       0 2007.43     9.8 2003.25    36.1  1988.3    55.8 1976.63    72.2 1965.78
      82  1961.1     105 1952.13   121.3 1948.02   157.4 1942.86   173.8 1941.15
  201.011941.104  211.721941.474   262.4  1940.9   265.6 1940.43   269.6  1938.7
   275.5 1937.32   284.6 1938.63   291.9 1940.04   311.6 1940.59   354.2 1940.54
   373.9 1943.07   406.7 1942.62   472.3 1943.38   498.5 1944.52  519.651946.293
   540.7 1947.78   560.1 1951.57  573.621951.322     628 1951.21   657.1 1956.15
#Mann= 7 ,-1 , 0
       0     .12       0  201.01     .06       0  211.72     .12       0
   269.6    .045       0   284.6     .12       0  519.65     .06       0
  573.62     .12       0
#XS Ineff= 2 , 0
                          435.27         1961.24
Permanent Ineff=
       F       F
Bank Sta=269.6,284.6
XS Rating Curve= 0 ,0
Exp/Cntr=0.3,0.1

Type RM Length L Ch R = 1 ,42918.6 ,345.7,355.2,353.1
XS GIS Cut Line= 3
      2041661.17      167991.797     2041658.566      168098.568
     2041727.576      168572.526
#Sta/Elev= 30
       0  1991.9    29.1 1981.67      68 1964.31    97.1 1953.06   106.8 1949.79
   136.3 1942.72   146.2 1940.96     156 1940.53  185.711941.217   205.2 1940.82
  215.68 1941.17   231.5 1941.44   254.4 1940.59   267.6 1941.72   274.1 1941.86
   280.7 1941.29   323.3 1940.44   333.2 1939.23   339.7 1937.24     343 1937.17
   346.3 1938.21   349.4 1939.97   352.8 1941.49   356.1 1941.94   369.2 1942.54
   395.5 1942.18  463.821943.574   536.6  1947.2   556.2 1948.51   585.8 1949.54
#Mann= 6 ,-1 , 0
       0     .12       0  185.71     .06       0  215.68     .12       0
   333.2    .045       0   349.4     .12       0  463.82     .06       0
#XS Ineff= 2 , 0
                          434.14         1958.42
Permanent Ineff=
       F       F
Bank Sta=333.2,349.4
XS Rating Curve= 0 ,0
Exp/Cntr=0.3,0.1

Type RM Length L Ch R = 1 ,42563.4 ,651.5,667.4,472.5
XS GIS Cut Line= 3
     2041581.743      168015.234     2041566.573      168099.436
      2041516.66      168939.279
#Sta/Elev= 30
       0 1984.07    34.9 1970.25    50.7 1965.32    92.1  1948.8   105.2 1944.66
     115 1942.98   124.8  1942.4  170.841942.412   190.3 1942.94   213.2 1942.76
   236.1 1942.17  254.361940.989   265.6 1941.67   288.5 1940.85   308.2 1941.08
   324.5 1940.49     354 1940.38   363.8 1939.32   367.2 1938.09   370.4 1936.81
   373.6 1936.43   383.5 1938.08   393.3 1940.58   399.8 1941.46  441.481941.767
   566.8 1944.29   727.2 1945.69   789.4 1947.35   848.3  1949.4   926.9 1954.24
#Mann= 6 ,-1 , 0
       0     .12       0  170.84     .06       0  254.36     .12       0
   367.2    .045       0   383.5     .12       0  441.48     .06       0
#XS Ineff= 2 , 0
                          465.23         1950.43
Permanent Ineff=
       F       F
Bank Sta=367.2,383.5
XS Rating Curve= 0 ,0
Exp/Cntr=0.3,0.1

Type RM Length L Ch R = 1 ,41896   ,144.9,147.7,310.4
XS GIS Cut Line= 2
     2041438.514      167961.849      2041045.74      168822.092
#Sta/Elev= 30
       0 1989.24    26.2 1981.83    52.4 1971.93      72 1966.39    94.9 1956.79
     108 1949.04   117.8 1944.56   130.9 1941.06     144 1939.66     150 1937.47
   157.1 1935.78     165 1937.15   183.2 1940.32   232.3 1941.62   284.7 1941.15
  344.791942.958   471.2 1942.53   644.6 1945.34  678.221943.663   690.4 1943.02
   706.8 1939.54   713.3 1939.89   726.4  1942.5   755.9 1942.82     769 1941.56
     805 1944.84  869.671946.088   903.1 1945.85  938.55 1948.33   945.7 1948.61
#Mann= 7 ,-1 , 0
       0     .12       0     150    .045       0     165     .12       0
  344.79     .06       0  678.22     .12       0  869.67    .016       0
  938.55     .06       0
#XS Ineff= 2 , 0
                          378.75         1955.43
Permanent Ineff=
       F       F
Bank Sta=150,165
XS Rating Curve= 0 ,0
Exp/Cntr=0.3,0.1

Type RM Length L Ch R = 1 ,41748.3 ,330.6,335.6,340.3
XS GIS Cut Line= 3
     2041349.972      167864.193     2041101.194      168282.912
     2040694.178      168622.439
#Sta/Elev= 30
       0 2003.22    65.4 1983.56    91.5 1973.02   114.4 1966.44   147.1 1952.68
   160.2 1944.56   166.7 1941.82   186.3 1938.35   202.7 1935.81   208.5  1938.3
   258.2  1942.1  318.441942.226   415.1 1941.81   503.4 1943.71   572.1 1940.35
  636.031940.065   647.4 1937.29   657.2  1940.2  681.57 1940.76     739  1942.1
  784.741947.211   797.9 1949.87   817.5 1950.52  826.631954.744   873.1 1967.35
   922.2 1983.29     932 1985.52  953.921988.307  960.61 1988.77  1017.1 1992.63
#Mann= 10 ,-1 , 0
       0     .12       0   186.3    .045       0   208.5     .12       0
  318.44     .06       0  636.03     .12       0  681.57     .06       0
  784.74    .016       0  826.63     .06       0  953.92     .12       0
  960.61     .06       0
#XS Ineff= 2 , 0
                          489.09         1956.95
Permanent Ineff=
       F       F
Bank Sta=186.3,208.5
XS Rating Curve= 0 ,0
Exp/Cntr=0.3,0.1

Type RM Length L Ch R = 1 ,41412.7 ,348.8,347.5,344.6
XS GIS Cut Line= 2
     2041261.909      167637.962     2040524.451      168297.786
#Sta/Elev= 30
       0 2047.69      36 2037.04    85.2 2019.88     154 1997.86   209.7 1981.98
   235.9 1971.92     249 1967.32   265.4 1962.56   294.9 1952.44   327.7 1942.82
   340.8 1939.93   380.1 1937.72   388.7 1936.38   393.2 1935.42   399.8  1934.9
     403 1935.11  407.56 1936.92   412.9 1939.77   422.7 1940.99   445.6  1940.7
   471.8 1941.95  491.891942.129   599.6 1941.56   668.4  1941.9   717.6 1942.65
     793 1945.58   861.8 1948.87   966.6 1955.07  977.451955.308   989.6 1956.78
#Mann= 5 ,-1 , 0
       0     .12       0   388.7    .045       0  407.56     .12       0
  491.89     .06       0  977.45    .016       0
#XS Ineff= 2 , 0
                           561.9         1968.17
Permanent Ineff=
       F       F
Bank Sta=388.7,407.56
XS Rating Curve= 0 ,0
Exp/Cntr=0.3,0.1