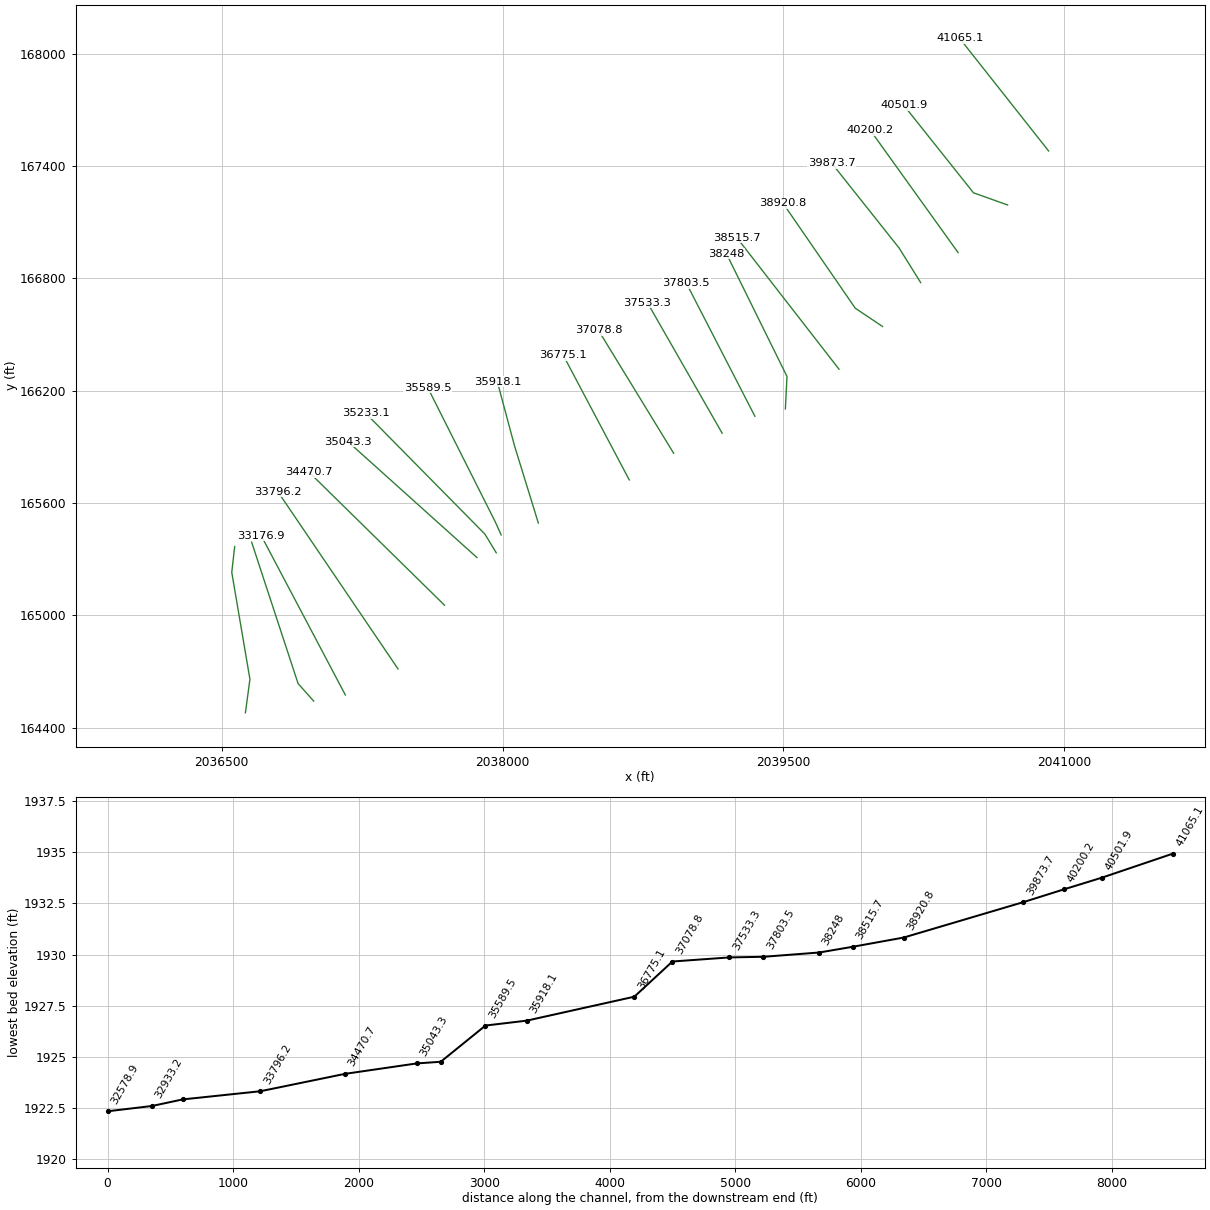
HEC-RAS study BRUSHCK.prj: BRUSHCK

--- BRUSHCK.g01 (geometry) --- (continued)

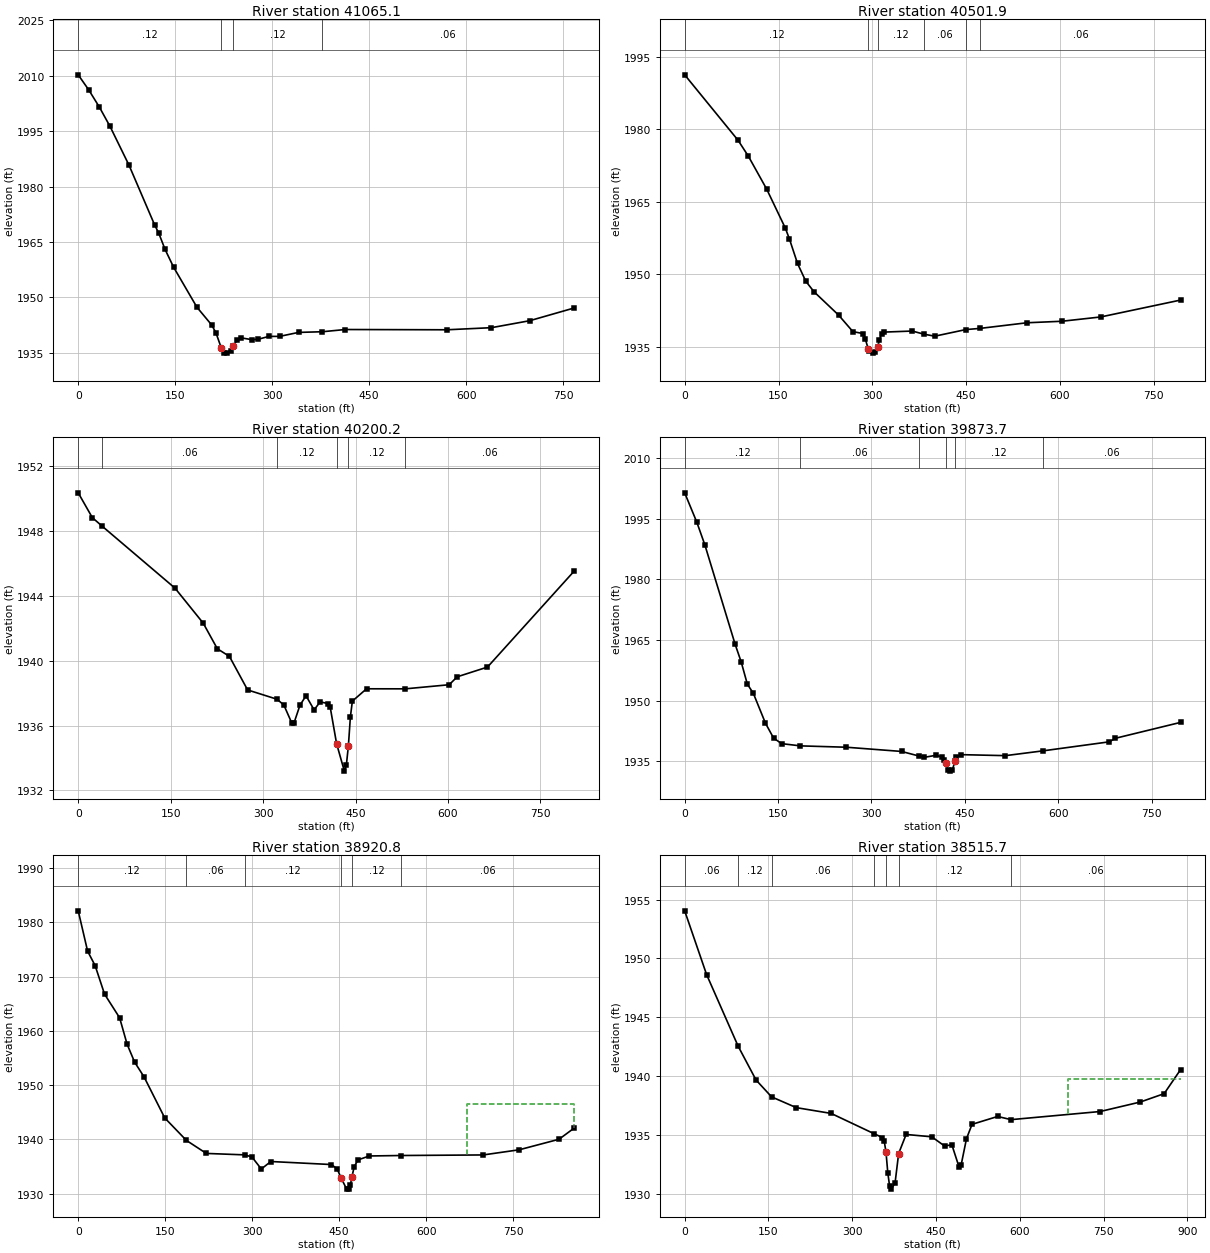
Type RM Length L Ch R = 1 ,41065.1 ,562.2,563.3,541.8
XS GIS Cut Line= 2
     2040916.812      167480.512     2040441.261      168082.377
#Sta/Elev= 30
       0 2010.26    16.4 2006.15    32.8  2001.5    49.2  1996.3    78.7 1985.75
     118 1969.71   124.6 1967.38   134.4 1962.98   147.5 1958.21   183.6 1947.36
   206.5 1942.54   213.1  1940.4  221.43 1936.27   226.2 1934.98   229.5 1934.93
     236  1935.4   239.8 1936.74   245.8 1938.52   252.4 1939.05   268.8 1938.57
   278.6  1938.7     295 1939.46   311.4 1939.46   340.9 1940.54  377.65 1940.72
     413 1941.32   570.4 1941.25   639.2 1941.82   698.2  1943.7   767.1 1947.15
#Mann= 4 ,-1 , 0
       0     .12       0  221.43    .045       0   239.8     .12       0
  377.65     .06       0
Bank Sta=221.43,239.8
XS Rating Curve= 0 ,0
Exp/Cntr=0.3,0.1

Type RM Length L Ch R = 1 ,40501.9 ,302.7,301.7,300.6
XS GIS Cut Line= 3
     2040697.737      167192.101     2040515.445      167257.205
     2040142.181      167725.955
#Sta/Elev= 30
       0 1991.23    85.3 1977.72   101.7 1974.45   131.2  1967.6   160.8  1959.6
   167.3 1957.39   180.4 1952.27   193.6 1948.61   206.7 1946.44     246 1941.62
   268.9  1938.2   285.2  1937.8   288.5 1936.78   293.3  1934.7   295.1 1934.17
   301.6 1933.76   304.9 1933.89   308.3 1934.93   311.4 1936.54   314.7 1937.72
     318  1938.1   363.8 1938.32  382.351937.676   399.8 1937.26  449.431938.624
  472.34 1938.87   547.2 1940.03   602.9 1940.34   665.1 1941.23   792.8 1944.72
#Mann= 6 ,-1 , 0
       0     .12       0   293.3    .045       0   308.3     .12       0
  382.35     .06       0  449.43     .12       0  472.34     .06       0
Bank Sta=293.3,308.3
XS Rating Curve= 0 ,0
Exp/Cntr=0.3,0.1

Type RM Length L Ch R = 1 ,40200.2 ,315.4,326.4,328.3
XS GIS Cut Line= 2
      2040432.98      166938.194      2039963.83      167591.926
#Sta/Elev= 30
       0 1950.36    22.9 1948.83   38.561948.312     157 1944.48   202.8 1942.32
   225.7 1940.74   245.3 1940.27   274.8  1938.2  322.561937.625   333.6 1937.27
   346.7 1936.14     350 1936.15   359.8 1937.26   369.6 1937.84   382.7 1936.97
   392.5 1937.46   405.6 1937.36   408.9 1937.12   419.2 1934.88   431.8 1933.19
     435 1933.55   438.3 1934.74   441.6 1936.55   444.8 1937.51   467.8 1938.27
  530.661938.267   601.8 1938.52   614.9 1939.01     664 1939.61   804.6 1945.53
#Mann= 6 ,-1 , 0
       0     .12       0   38.56     .06       0  322.56     .12       0
   419.2    .045       0   438.3     .12       0  530.66     .06       0
Bank Sta=419.2,438.3
XS Rating Curve= 0 ,0
Exp/Cntr=0.3,0.1

Type RM Length L Ch R = 1 ,39873.7 ,966.1,953,949.6
XS GIS Cut Line= 3
     2040233.327      166777.604      2040118.31      166962.066
     2039758.067      167415.625
#Sta/Elev= 30
       0 2001.41    19.5 1994.14    32.4 1988.54    81.1 1963.91    90.8 1959.56
   100.6  1954.1   110.3  1951.8   129.8  1944.4   142.8 1940.74   155.7 1939.36
  185.891938.809   259.9 1938.47   348.3 1937.43  376.951936.271   384.3 1935.96
   403.9 1936.48   413.7 1936.03     417 1935.38   419.1 1934.45   423.5 1932.82
   426.8 1932.56   430.1 1932.94   434.1 1934.96   436.6 1936.05   443.2 1936.64
   515.2 1936.39   576.11937.589   682.1 1939.81   691.9 1940.69   796.6 1944.62
#Mann= 6 ,-1 , 0
       0     .12       0  185.89     .06       0  376.95     .12       0
   419.1    .045       0   434.1     .12       0   576.1     .06       0
Bank Sta=419.1,434.1
XS Rating Curve= 0 ,0
Exp/Cntr=0.3,0.1

Type RM Length L Ch R = 1 ,38920.8 ,402.2,405.1,406.9
XS GIS Cut Line= 3
     2040029.334      166543.229     2039883.935      166640.885
     2039498.431      167200.998
#Sta/Elev= 30
       0 1982.12    16.2 1974.69    29.2 1972.01    45.4 1966.77    71.4 1962.41
    84.3 1957.53    97.3 1954.23   113.5 1951.52   149.2 1943.95  186.491939.813
   220.9 1937.41  286.781937.144   299.4 1936.77   315.7 1934.54   332.1 1935.92
   436.7 1935.36   446.5 1934.54     453 1932.96   462.8 1930.83   466.1 1930.83
   469.4 1931.62   471.8 1933.04   475.9 1934.97   482.4 1936.22     502 1936.94
  557.021937.027   698.2 1937.13   760.3 1938.08     829 1940.02   855.1 1942.08
#Mann= 6 ,-1 , 0
       0     .12       0  186.49     .06       0  286.78     .12       0
     453    .045       0   471.8     .12       0  557.02     .06       0
#XS Ineff= 2 , 0
                          670.44         1946.57
Permanent Ineff=
       F       F
Bank Sta=453,471.8
XS Rating Curve= 0 ,0
Exp/Cntr=0.3,0.1

Type RM Length L Ch R = 1 ,38515.7 ,274,267.6,266.3
XS GIS Cut Line= 2
     2039797.172         166315.     2039252.424      167016.319
#Sta/Elev= 30
       0 1954.05    39.3 1948.62   95.711942.538   127.8 1939.66  155.591938.228
   199.9 1937.31   262.2 1936.82   339.41935.087   353.9 1934.77   357.2 1934.49
   360.5 1933.52   363.7 1931.76     367 1930.62   370.3 1930.38   376.8 1930.94
   383.1 1933.41   396.5 1935.03   442.4 1934.83   465.3 1934.05   478.4 1934.15
   491.5 1932.23   494.8 1932.39   504.6 1934.67   514.5 1935.89   560.3 1936.56
  584.45 1936.29   743.8 1936.98   815.9 1937.79   858.5  1938.5     888 1940.55
#Mann= 7 ,-1 , 0
       0     .06       0   95.71     .12       0  155.59     .06       0
   339.4     .12       0   360.5    .045       0   383.1     .12       0
  584.45     .06       0
#XS Ineff= 2 , 0
                           685.7         1939.73
Permanent Ineff=
       F       F
Bank Sta=360.5,383.1
XS Rating Curve= 0 ,0
Exp/Cntr=0.3,0.1

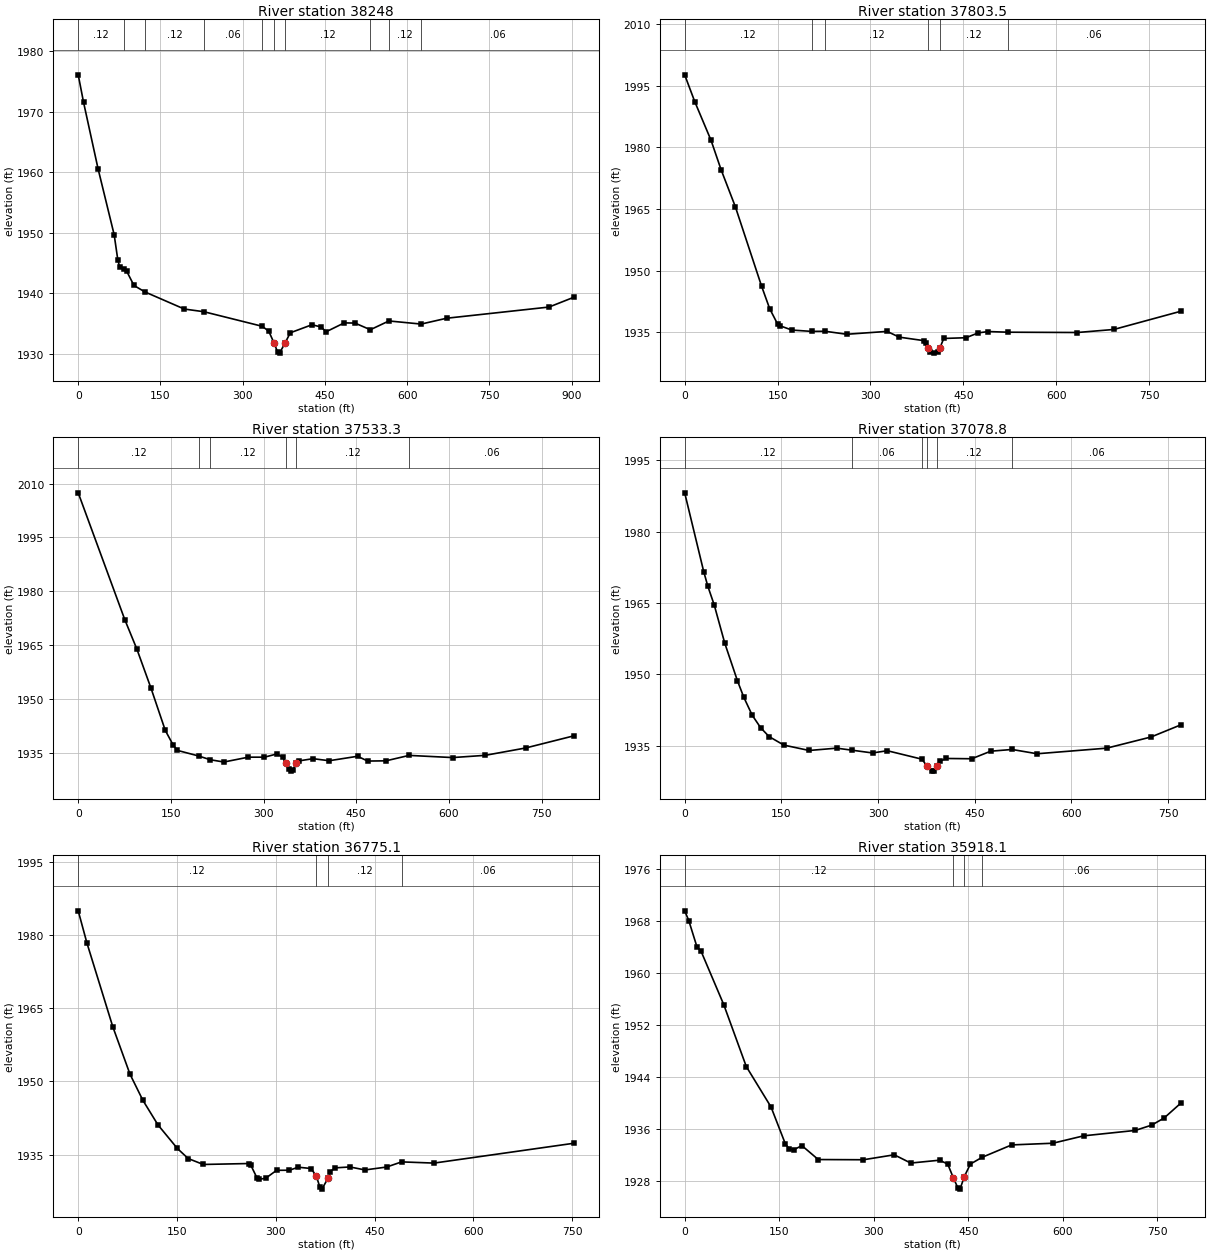
Type RM Length L Ch R = 1 ,38248   ,441.6,444.5,437.4
XS GIS Cut Line= 3
     2039510.671      166102.691     2039519.351      166276.302
     2039196.001      166931.684
#Sta/Elev= 30
       0 1976.12     9.8 1971.55    36.1 1960.63    65.6 1949.67    72.2 1945.54
    75.4  1944.4   82.911944.077    88.6 1943.61   101.7 1941.29  121.511940.227
   193.5 1937.39  229.321936.946   335.61934.539   347.5 1933.73   357.4 1931.74
   363.9 1930.22   367.2  1930.1   377.1 1931.74   386.8 1933.46   426.2 1934.79
   442.6 1934.44   452.4 1933.64   485.2  1935.1   504.8 1935.07  532.851933.969
  566.71 1935.42  625.531934.905     672 1935.87   858.8 1937.72   904.6 1939.36
#Mann= 10 ,-1 , 0
       0     .12       0   82.91     .06       0  121.51     .12       0
  229.32     .06       0   335.6     .12       0   357.4    .045       0
   377.1     .12       0  532.85     .06       0  566.71     .12       0
  625.53     .06       0
Bank Sta=357.4,377.1
XS Rating Curve= 0 ,0
Exp/Cntr=0.3,0.1

Type RM Length L Ch R = 1 ,37803.5 ,263.5,270.3,281.9
XS GIS Cut Line= 2
      2039347.91      166063.628     2038981.157      166775.434
#Sta/Elev= 30
       0 1997.63    16.3 1991.09    42.5 1981.71    58.8 1974.53    81.7 1965.57
   124.2 1946.17   137.3 1940.68   150.3 1936.89   153.6 1936.56   173.2  1935.5
  204.941935.182  227.021935.209   261.5 1934.48   326.8 1935.18   346.4 1933.78
   385.7 1932.94   388.9 1932.46   392.8 1931.12   395.5 1930.26     402 1929.89
   408.5 1930.05   411.8 1931.08   418.3 1933.46   454.3 1933.64   473.9 1934.82
   490.2 1935.14  521.911934.983     634 1934.91   692.9 1935.65   800.7 1940.07
#Mann= 6 ,-1 , 0
       0     .12       0  204.94     .06       0  227.02     .12       0
   392.8    .045       0   411.8     .12       0  521.91     .06       0
Bank Sta=392.8,411.8
XS Rating Curve= 0 ,0
Exp/Cntr=0.3,0.1

Type RM Length L Ch R = 1 ,37533.3 ,450.2,454.5,429.1
XS GIS Cut Line= 2
     2039172.801      165973.452     2038773.876      166670.176
#Sta/Elev= 30
       0 2007.45    75.4 1972.09      95 1963.86     118  1952.9   140.9 1941.23
     154 1937.04   160.6 1935.64  195.451934.059  213.83 1933.03   235.9  1932.4
   275.3 1933.75   301.5 1933.75   321.1 1934.63     331 1933.79  335.71 1932.18
   340.8 1930.35   344.1 1929.86   347.4 1930.17   352.6 1932.09   357.2 1932.71
   380.1 1933.33   406.3 1932.76   452.2    1934   468.6 1932.67   498.1 1932.73
  535.641934.245   606.2 1933.64   658.7 1934.26   724.2 1936.31   802.8 1939.72
#Mann= 6 ,-1 , 0
       0     .12       0  195.45     .06       0  213.83     .12       0
  335.71    .045       0   352.6     .12       0  535.64     .06       0
Bank Sta=335.71,352.6
XS Rating Curve= 0 ,0
Exp/Cntr=0.3,0.1

Type RM Length L Ch R = 1 ,37078.8 ,302.5,303.6,300.5
XS GIS Cut Line= 2
     2038913.883      165866.146     2038512.275      166522.667
#Sta/Elev= 30
       0 1988.16    29.5 1971.62      36 1968.49    45.8 1964.61    62.2 1956.56
    81.9 1948.64    91.7  1945.2   104.8 1941.41   117.9 1938.78     131 1936.92
   153.9 1935.13   193.2    1934   235.8 1934.49  258.921934.074   291.5 1933.48
   314.4 1933.95  368.211932.169     376 1930.71   383.2 1929.66   386.4 1929.73
     391 1930.84   396.3 1931.75   406.1 1932.32   445.4 1932.26   474.9 1933.85
  508.041934.212   546.9 1933.31     655 1934.49   723.8 1936.84   769.6 1939.37
#Mann= 6 ,-1 , 0
       0     .12       0  258.92     .06       0  368.21     .12       0
     376    .045       0     391     .12       0  508.04     .06       0
Bank Sta=376,391
XS Rating Curve= 0 ,0
Exp/Cntr=0.3,0.1

Type RM Length L Ch R = 1 ,36775.1 ,787.7,857.1,790.3
XS GIS Cut Line= 2
     2038676.932       165723.63     2038324.459      166389.038
#Sta/Elev= 30
       0 1984.92    13.1 1978.39    52.4 1961.23    78.6 1951.48    98.2 1946.12
   121.1 1941.09   150.6 1936.26     167  1934.2   189.9 1932.99   258.6 1933.18
   261.9 1932.89   271.7 1930.16     275 1929.95   284.8 1930.18   301.2 1931.79
   320.8 1931.81   333.9 1932.43   353.6 1932.16   361.6 1930.58   366.7 1928.44
     370 1927.94   379.8  1930.3     383 1931.53   389.6 1932.29   412.5 1932.48
   435.4 1931.87   468.2 1932.46  491.031933.518   540.2 1933.27     753 1937.34
#Mann= 4 ,-1 , 0
       0     .12       0   361.6    .045       0   379.8     .12       0
  491.03     .06       0
Bank Sta=361.6,379.8
XS Rating Curve= 0 ,0
Exp/Cntr=0.3,0.1

Type RM Length L Ch R = 1 ,35918.1 ,321.2,328.6,307.1
XS GIS Cut Line= 3
     2038191.243       165493.17     2038064.311      165904.517
     2037971.844      166248.791
#Sta/Elev= 30
       0 1969.58     6.5 1968.08    19.6    1964    26.1 1963.34      62 1955.15
    97.8 1945.62     137 1939.41   159.8 1933.72   166.3 1932.93   172.8  1932.8
   185.9 1933.47     212 1931.32   283.7 1931.29   332.6 1932.05   358.7 1930.78
   404.4 1931.22   417.4 1930.63   426.3 1928.52   433.8  1926.9     437 1926.77
   443.6 1928.67   453.4 1930.63  471.981931.664   518.8 1933.57   584.2 1933.83
   633.2 1934.97     715  1935.8   741.2 1936.62   760.8 1937.71     787 1939.97
#Mann= 4 ,-1 , 0
       0     .12       0   426.3    .045       0   443.6     .12       0
  471.98     .06       0
Bank Sta=426.3,443.6
XS Rating Curve= 0 ,0
Exp/Cntr=0.3,0.1

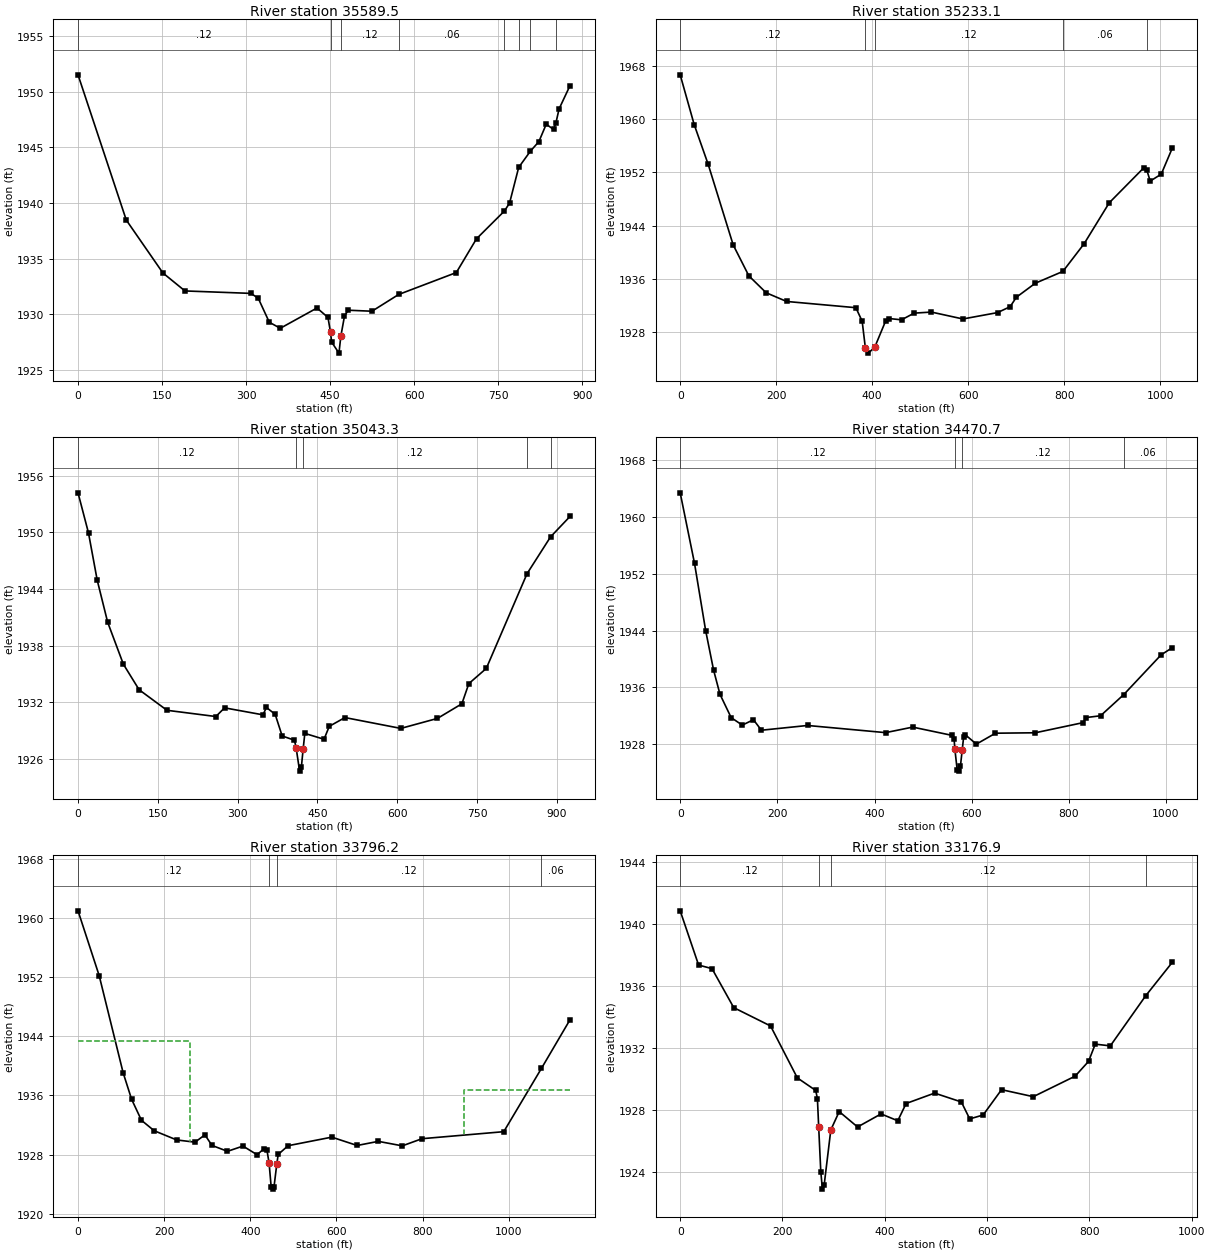
Type RM Length L Ch R = 1 ,35589.5 ,346,356.4,356.5
XS GIS Cut Line= 3
      2037992.68      165429.956     2037961.192      165499.392
     2037600.948      166215.538
#Sta/Elev= 30
       0  1951.5    86.1 1938.47   151.5 1933.72   190.8 1932.11   308.6 1931.89
   321.6 1931.45   341.3  1929.3   360.9 1928.76   426.4 1930.58     446 1929.73
  450.49  1928.4   452.5 1927.52   465.6 1926.53   468.9 1928.04   475.4 1929.84
     482 1930.38   524.5 1930.29  572.041931.791     675 1933.76     711 1936.79
  760.671939.275   769.9 1939.98  786.261943.196  807.16 1944.65   822.3 1945.51
   835.4 1947.07   848.4  1946.6  852.691947.185   858.3 1948.44   877.9 1950.54
#Mann= 8 ,-1 , 0
       0     .12       0  450.49    .045       0   468.9     .12       0
  572.04     .06       0  760.67     .08       0  786.26     .06       0
  807.16    .016       0  852.69     .06       0
Bank Sta=450.49,468.9
XS Rating Curve= 0 ,0
Exp/Cntr=0.3,0.1

Type RM Length L Ch R = 1 ,35233.1 ,190.4,189.8,186.7
XS GIS Cut Line= 3
     2037966.313      165334.679     2037905.549      165434.505
     2037267.528      166081.206
#Sta/Elev= 30
       0 1966.72    29.2 1959.21    58.4 1953.21   110.4 1941.08   143.1 1936.41
   179.2 1933.86   221.8 1932.55   366.1 1931.61   379.2 1929.57   385.8  1925.6
   392.4 1924.76   405.6 1925.69   428.4 1929.66     435 1929.98   461.2 1929.78
   487.5 1930.79   523.5 1930.95   589.1 1929.91   661.3 1930.87   687.5 1931.76
   700.6 1933.19     740  1935.3  797.521937.082   841.7 1941.25   894.1 1947.43
   966.3 1952.72  972.171952.406   979.4  1950.7  1002.4 1951.74  1025.3 1955.65
#Mann= 5 ,-1 , 0
       0     .12       0   385.8    .045       0   405.6     .12       0
  797.52     .06       0  972.17    .016       0
Bank Sta=385.8,405.6
XS Rating Curve= 0 ,0
Exp/Cntr=0.3,0.1

Type RM Length L Ch R = 1 ,35043.3 ,548.3,572.6,561.3
XS GIS Cut Line= 2
     2037863.342      165308.956     2037175.601       165926.91
#Sta/Elev= 30
       0 1954.19    19.7 1949.93    36.1 1944.92    55.7 1940.47    85.2 1936.02
   114.8 1933.31   167.2 1931.13     259 1930.47   275.4 1931.39   347.5 1930.65
   354.1 1931.43   370.5  1930.7   383.6 1928.41   406.6 1927.96   409.8 1927.18
   416.4 1924.68   419.7  1925.1     423    1927   426.2 1928.68   462.3 1928.06
   472.1 1929.43   501.6 1930.36   606.6 1929.21   675.4 1930.27   721.3 1931.82
   734.4 1933.96   767.2 1935.57  843.781945.616  887.981949.521   924.6 1951.69
#Mann= 5 ,-1 , 0
       0     .12       0   409.8    .045       0     423     .12       0
  843.78     .08       0  887.98     .06       0
Bank Sta=409.8,423
XS Rating Curve= 0 ,0
Exp/Cntr=0.3,0.1

Type RM Length L Ch R = 1 ,34470.7 ,611.7,674.5,568.3
XS GIS Cut Line= 2
     2037689.924      165054.514     2036967.268      165764.149
#Sta/Elev= 30
       0 1963.43    29.5 1953.48    52.4    1944    68.8 1938.41    81.9 1935.01
   104.9 1931.72   127.8 1930.66   150.8 1931.42   167.2 1929.94   262.2 1930.61
   422.8  1929.6   478.6 1930.38   560.5  1929.2   563.8 1928.69   565.4 1927.27
   570.3 1924.26   573.6 1924.17   576.9  1924.9   580.4 1927.08   583.4 1928.94
   586.7 1929.31   609.7 1927.98     649 1929.52   730.9 1929.58   829.3 1931.01
   835.8 1931.73   865.3 1931.98  913.07 1934.97   989.9 1940.57  1012.8 1941.58
#Mann= 4 ,-1 , 0
       0     .12       0   565.4    .045       0   580.4     .12       0
  913.07     .06       0
Bank Sta=565.4,580.4
XS Rating Curve= 0 ,0
Exp/Cntr=0.3,0.1

Type RM Length L Ch R = 1 ,33796.2 ,467.5,619.3,610.3
XS GIS Cut Line= 2
      2037441.66      164714.236     2036800.617      165659.815
#Sta/Elev= 30
       0 1961.01    49.1 1952.24   104.8 1939.07   124.4 1935.49   147.3 1932.64
   176.8 1931.23   229.1 1929.98   271.7 1929.68   294.6 1930.67     311 1929.24
     347 1928.44     383 1929.15   415.7 1927.98   432.1 1928.81   438.6 1928.62
   443.6 1926.86   448.4 1923.66   451.7 1923.32     455  1923.6   461.5 1926.71
   464.8 1928.02   487.7  1929.2   589.2 1930.36   648.1 1929.23   697.2 1929.79
   752.9 1929.18   798.7 1930.15   988.5  1931.1  1076.11939.683  1142.4 1946.27
#Mann= 4 ,-1 , 0
       0     .12       0   443.6    .045       0   461.5     .12       0
  1076.1     .06       0
#XS Ineff= 2 , 0
          259.13 1943.39  895.42         1936.79
Permanent Ineff=
       F       F
Bank Sta=443.6,461.5
XS Rating Curve= 0 ,0
Exp/Cntr=0.3,0.1

Type RM Length L Ch R = 1 ,33176.9 ,246.1,243.8,238
XS GIS Cut Line= 2
      2037160.41      164574.913     2036711.192      165425.608
#Sta/Elev= 30
       0 1940.83      36 1937.34    62.2 1937.11   104.7  1934.6   176.7 1933.42
     229 1930.08     265 1929.27   268.3 1928.74   270.8 1926.91   274.9 1924.04
   278.1 1922.92   281.4 1923.16   294.5 1926.73   310.9 1927.91   346.8 1926.92
   392.7 1927.76   425.4 1927.32   441.7 1928.43   497.4  1929.1   549.7 1928.53
   566.1 1927.44   592.3 1927.69   628.3 1929.32   690.4 1928.87   772.2 1930.19
   798.4 1931.14   811.5 1932.25     841 1932.14  909.911935.353     962 1937.51
#Mann= 4 ,-1 , 0
       0     .12       0   270.8    .045       0   294.5     .12       0
  909.91     .06       0
Bank Sta=270.8,294.5
XS Rating Curve= 0 ,0
Exp/Cntr=0.3,0.1

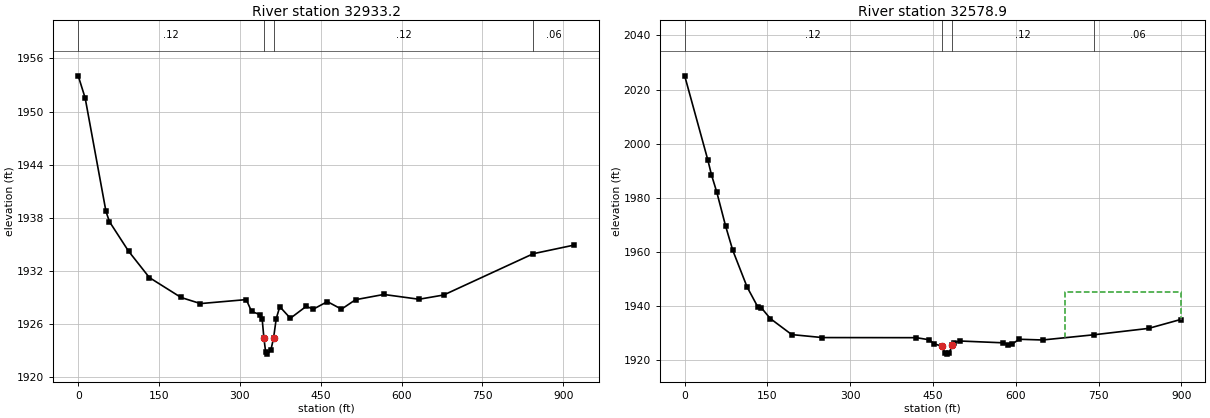
Type RM Length L Ch R = 1 ,32933.2 ,399.7,354.2,360.3
XS GIS Cut Line= 3
     2036991.139      164542.361     2036907.806      164636.111
     2036659.889      165391.102
#Sta/Elev= 30
       0 1954.04    12.9 1951.53    51.5 1938.72    57.9 1937.57    93.3 1934.24
     132 1931.25   190.8    1929   226.8 1928.31   311.8 1928.76   321.6 1927.42
     338 1927.05   341.3 1926.56   344.5 1924.41   347.8 1922.82   351.1  1922.6
   357.6  1923.1  362.49 1924.44   367.4 1926.62     374 1927.96   393.6 1926.65
     423    1928   436.1 1927.68   462.3 1928.53   488.4 1927.68   514.6 1928.75
   566.9 1929.34   632.3  1928.8   678.1 1929.28  844.371933.947   920.1 1934.92
#Mann= 4 ,-1 , 0
       0     .12       0   344.5    .045       0  362.49     .12       0
  844.37     .06       0
Bank Sta=344.5,362.49
XS Rating Curve= 0 ,0
Exp/Cntr=0.3,0.1

Type RM Length L Ch R = 1 ,32578.9 ,400.9,381,375.8
XS GIS Cut Line= 4
     2036626.556      164479.861     2036650.633      164659.215
     2036553.639      165229.861     2036569.264      165367.882
#Sta/Elev= 30
       0 2025.07      42 1993.97    48.5 1988.57    58.2 1982.11    74.3 1969.52
    87.2 1960.62   113.1 1947.12   132.5 1939.77     139 1939.42   155.1 1935.48
     194 1929.55   249.6 1928.45   419.7 1928.41   442.6 1927.66   452.4 1926.13
   465.5  1925.3     472  1922.7   475.3 1922.34   478.6 1922.58   485.1 1925.67
   488.4 1926.57   498.2 1927.19   576.7 1926.52   586.5 1925.89     593 1925.99
   606.1 1927.83   648.6 1927.56  742.021929.493   840.6 1931.84   898.7 1935.12
#Mann= 4 ,-1 , 0
       0     .12       0   465.5    .045       0   485.1     .12       0
  742.02     .06       0
#XS Ineff= 2 , 0
                          689.66         1945.14
Permanent Ineff=
       F       F
Bank Sta=465.5,485.1
XS Rating Curve= 0 ,0
Exp/Cntr=0.3,0.1