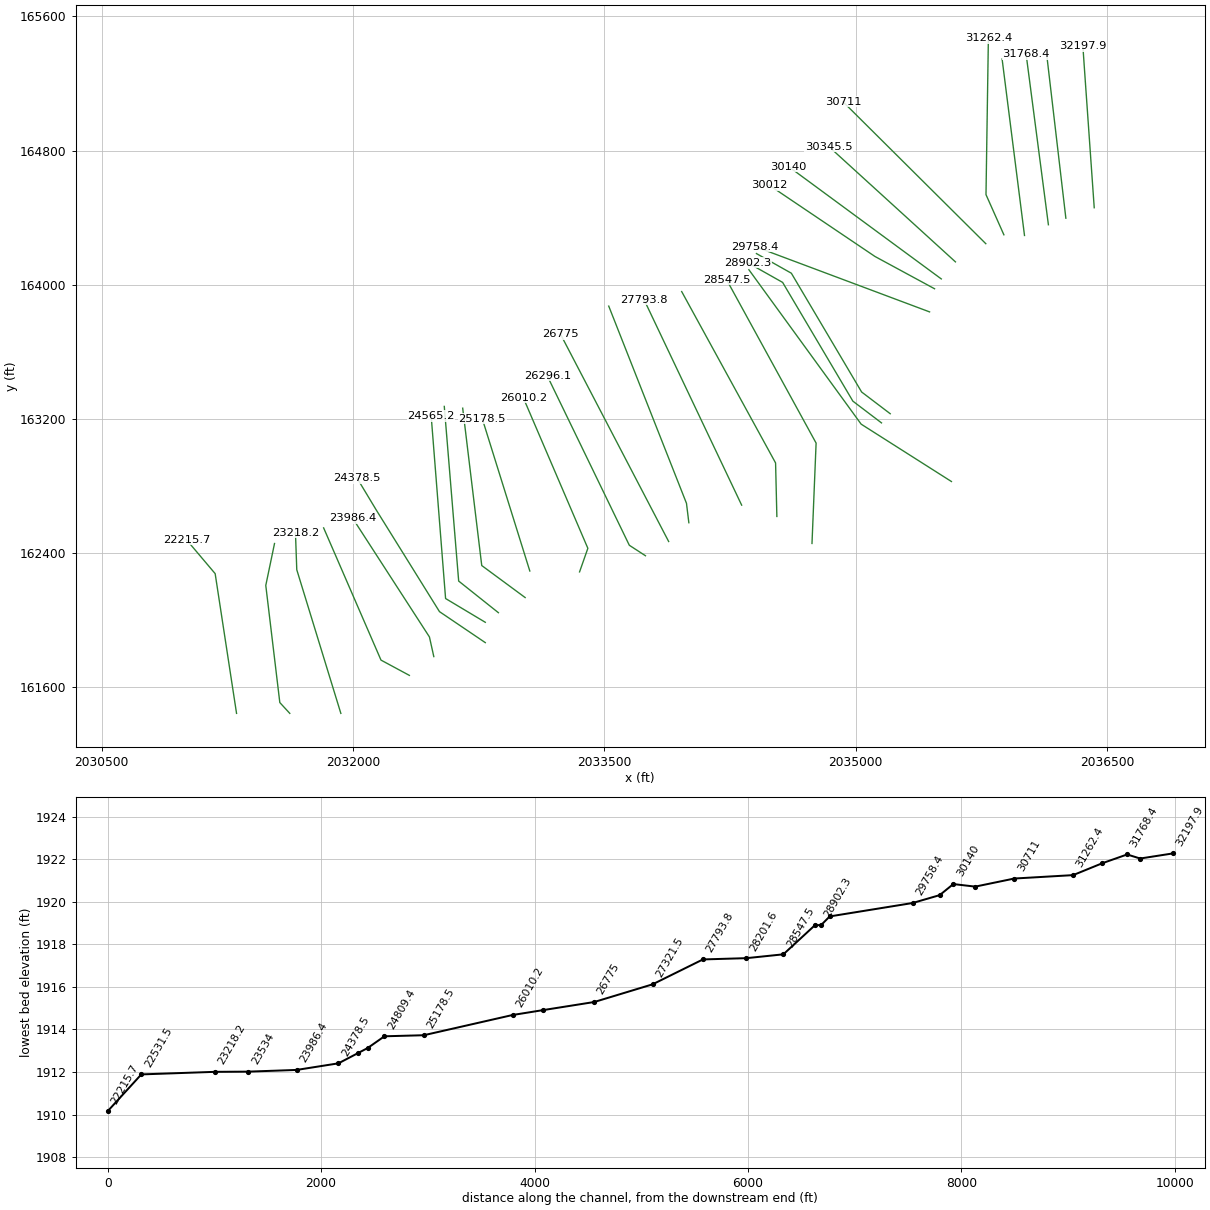
HEC-RAS study BRUSHCK.prj: BRUSHCK

--- BRUSHCK.g01 (geometry) --- (continued)

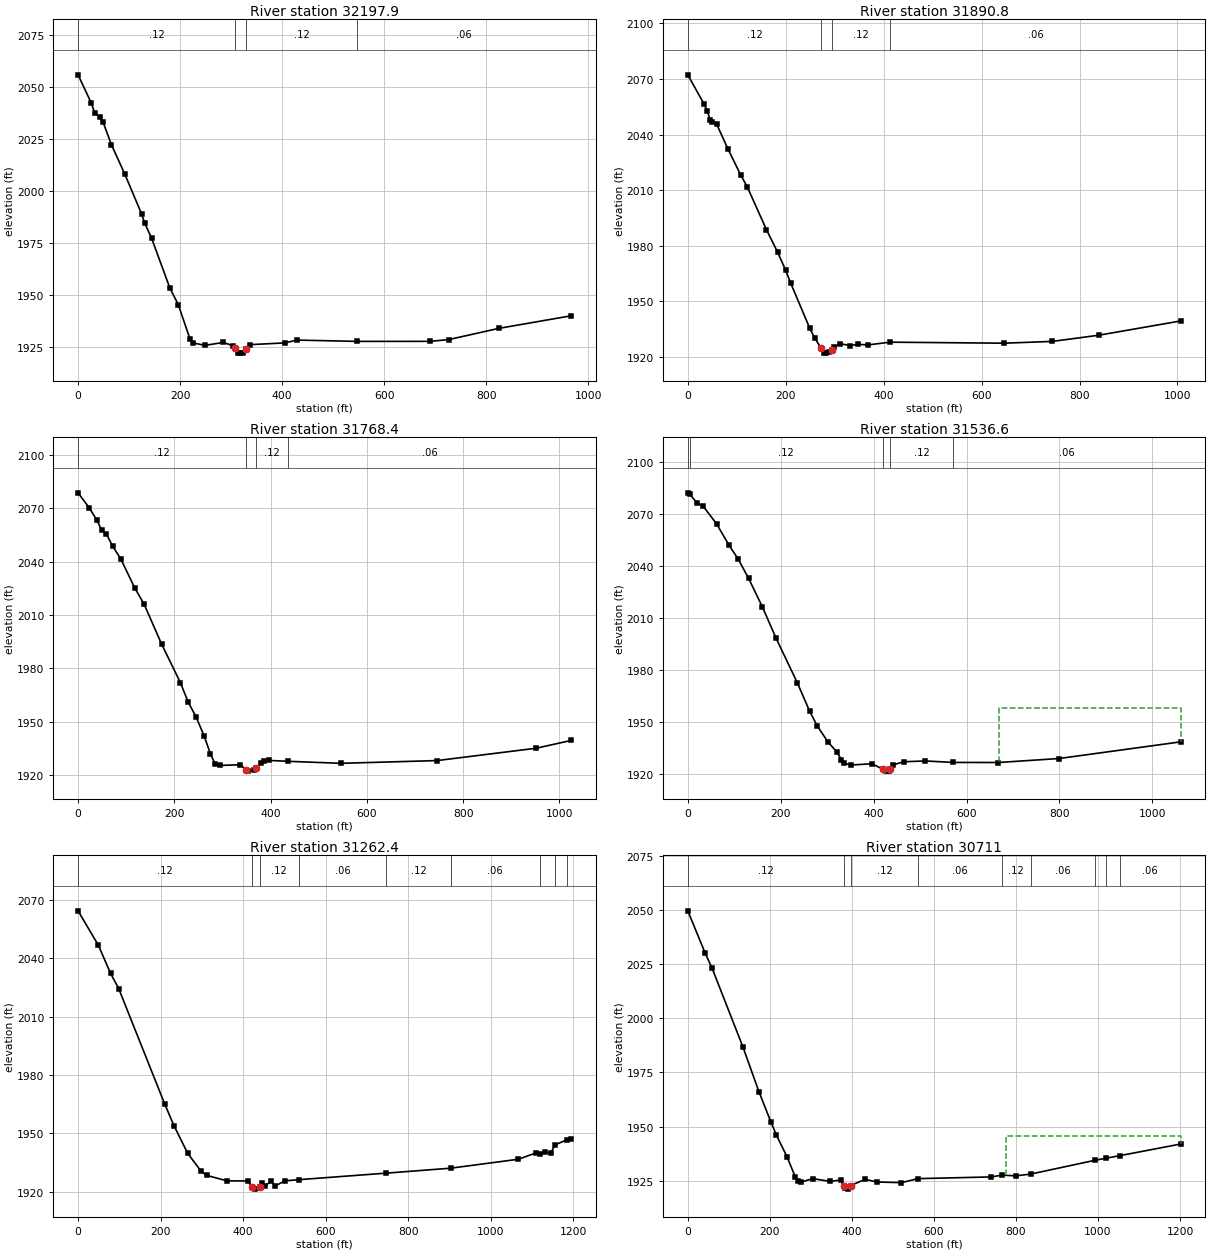
Type RM Length L Ch R = 1 ,32197.9 ,295.3,307.1,302.9
XS GIS Cut Line= 3
     2036423.431      164459.028     2036366.139      165271.528
     2036355.723      165422.569
#Sta/Elev= 30
       0 2056.05    26.2 2042.34    32.7 2037.64    42.5 2035.78    49.1 2033.25
    65.4 2022.44    91.6 2008.32   124.3 1989.26   130.8 1984.64   143.9 1977.61
   179.9 1953.55   196.3 1945.63   219.2 1929.13   225.7 1927.15   248.6 1926.01
   284.6  1927.4   304.2 1925.75   307.5 1924.84     314 1922.53   317.3 1922.27
   323.8 1922.43   329.1 1924.38   336.9 1926.35   405.6 1927.19   428.5 1928.54
  547.091927.913   690.2 1927.93   726.2 1928.78   824.2 1934.16   965.9 1940.21
#Mann= 4 ,-1 , 0
       0     .12       0   307.5    .045       0   329.1     .12       0
  547.09     .06       0
Bank Sta=307.5,329.1
XS Rating Curve= 0 ,0
Exp/Cntr=0.3,0.1

Type RM Length L Ch R = 1 ,31890.8 ,121.4,122.5,122.9
XS GIS Cut Line= 2
      2036254.16      164396.528     2036136.973      165396.528
#Sta/Elev= 30
       0 2072.24    32.8 2056.67    39.4 2052.93    45.9 2047.82    49.2 2046.63
      59  2045.6      82 2032.22   108.2  2018.1   121.4 2011.78   160.7 1988.65
   183.7 1976.37   200.1 1966.66   209.9 1959.98   249.2 1935.37   259.1 1930.24
   272.2 1924.78   278.8 1922.28     282 1922.03   288.6  1922.5  293.99 1923.86
   298.4 1925.36   311.6 1927.11   331.2 1926.11   347.6 1926.79   367.3 1926.44
  412.931927.939   646.1 1927.39   744.5 1928.36   839.6  1931.7  1006.8 1939.41
#Mann= 4 ,-1 , 0
       0     .12       0   272.2    .045       0  293.99     .12       0
  412.93     .06       0
Bank Sta=272.2,293.99
XS Rating Curve= 0 ,0
Exp/Cntr=0.3,0.1

Type RM Length L Ch R = 1 ,31768.4 ,225.5,231.8,229.5
XS GIS Cut Line= 2
     2036149.994      164357.465     2036017.181       165373.09
#Sta/Elev= 30
       0 2078.74    22.9 2070.42    39.3 2063.31    49.1 2057.72    58.9 2055.58
      72 2048.62    88.4 2041.74   117.8 2025.24   137.4    2016   173.4 1993.79
   212.7 1971.93   229.1 1960.88   245.4 1952.62   261.8 1942.09   274.9 1932.05
   284.7 1926.25   294.5 1925.43   337.1 1925.79   348.7 1923.08   353.4 1922.22
   366.5 1922.85   369.8    1924   379.6 1926.78   386.2 1927.74     396 1928.25
  435.84 1927.74   546.5 1926.61   746.1 1928.16   952.3 1935.12  1024.3 1939.47
#Mann= 4 ,-1 , 0
       0     .12       0   348.7    .045       0   369.8     .12       0
  435.84     .06       0
Bank Sta=348.7,369.8
XS Rating Curve= 0 ,0
Exp/Cntr=0.3,0.1

Type RM Length L Ch R = 1 ,31536.6 ,278.9,274.2,254
XS GIS Cut Line= 2
     2036007.375      164293.581     2035873.661      165346.266
#Sta/Elev= 30
       0 2082.05    4.112081.266    19.6 2076.32    32.8 2074.45    62.2  2064.1
    88.4    2052   108.1 2044.08     131 2032.73   160.5 2016.41     190 1998.37
   235.8 1972.65     262 1956.47   278.4 1947.97   301.3 1938.74     321 1932.78
   330.8 1928.33   337.3 1926.42   350.4 1925.32   396.3 1926.05   419.2 1923.03
   425.8 1921.81   432.3 1922.01   436.3 1923.24   442.1 1925.43   465.1 1927.21
   510.9 1927.67  571.131926.824   668.1 1926.77   799.1 1929.07  1061.1 1938.67
#Mann= 5 ,-1 , 0
       0     .06       0    4.11     .12       0   419.2    .045       0
   436.3     .12       0  571.13     .06       0
#XS Ineff= 2 , 0
                          668.85         1958.36
Permanent Ineff=
       F       F
Bank Sta=419.2,436.3
XS Rating Curve= 0 ,0
Exp/Cntr=0.3,0.1

Type RM Length L Ch R = 1 ,31262.4 ,531.8,551.3,555.5
XS GIS Cut Line= 3
     2035884.369      164297.569     2035777.598      164537.153
     2035791.834      165469.227
#Sta/Elev= 30
       0 2064.48    49.2 2046.74    78.7  2032.3    98.4  2024.5   209.8 1965.13
   232.8 1953.72   265.6 1939.67   298.3 1930.42   311.4 1928.35   360.4 1925.52
   412.8 1925.42   420.9 1922.43   429.1 1921.25     440 1922.48   445.5 1924.35
     452 1922.95   468.4  1925.2   478.2 1922.98   501.1 1925.49   534.91926.118
  746.481929.473   902.91932.032  1066.9 1936.63  1109.4 1939.89 1118.461939.459
  1132.3 1940.34  1145.4 1939.66 1155.011943.952 1184.551946.676  1194.5 1947.23
#Mann= 9 ,-1 , 0
       0     .12       0   420.9    .045       0     440     .12       0
   534.9     .06       0  746.48     .12       0   902.9     .06       0
 1118.46    .016       0 1155.01     .08       0 1184.55     .06       0
Bank Sta=420.9,440
XS Rating Curve= 0 ,0
Exp/Cntr=0.3,0.1

Type RM Length L Ch R = 1 ,30711   ,363.2,365.5,362.3
XS GIS Cut Line= 2
     2035776.419      164244.584     2034923.778      165091.623
#Sta/Elev= 30
       0 2049.68    42.6 2030.04      59 2023.28   134.3 1986.85   173.6 1966.03
     203 1951.98   216.1 1946.01   242.3  1935.9     262 1926.75   268.5 1924.89
   275.1 1924.28   304.6 1925.94   347.1 1924.66   373.3 1925.33   379.9 1922.54
   383.2 1921.46   389.7 1921.09   397.4 1922.76   432.3 1925.59   461.8 1924.38
   520.7 1924.08  561.211925.935   740.1 1926.73  766.19 1927.56   799.1 1927.22
  835.561928.024  992.731934.417 1020.591935.404  1052.91936.541  1201.9 1941.94
#Mann= 9 ,-1 , 0
       0     .12       0   379.9    .045       0   397.4     .12       0
  561.21     .06       0  766.19     .12       0  835.56     .06       0
  992.73    .016       0 1020.59     .08       0  1052.9     .06       0
#XS Ineff= 2 , 0
                          774.79          1945.5
Permanent Ineff=
       F       F
Bank Sta=379.9,397.4
XS Rating Curve= 0 ,0
Exp/Cntr=0.3,0.1

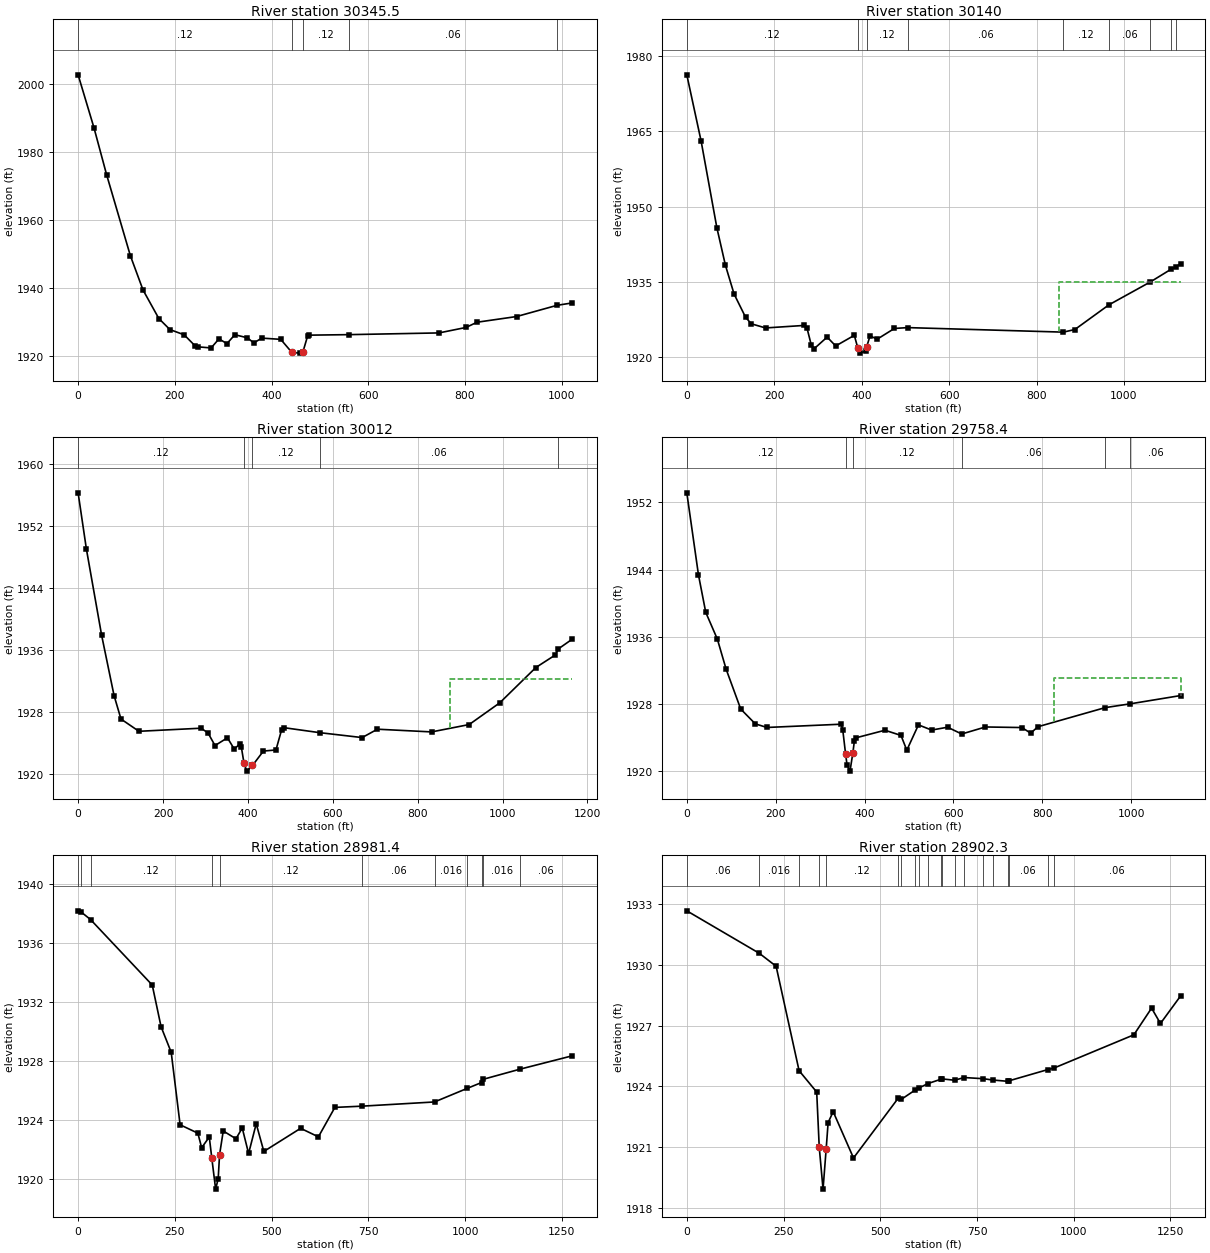
Type RM Length L Ch R = 1 ,30345.5 ,204.5,205.5,207
XS GIS Cut Line= 2
     2035595.306      164136.111     2034840.098      164823.611
#Sta/Elev= 30
       0 2002.77    32.7 1987.21    58.9 1973.33     108 1949.46   134.2 1939.33
   166.9 1930.92   189.8 1927.66   219.3 1926.11   242.2 1922.81   248.8 1922.55
     275 1922.24   291.3 1924.92   307.7  1923.5   324.1 1926.14   350.2 1925.22
   363.3 1923.71   379.7 1925.14     419 1924.77   441.9 1920.93   458.3 1920.71
   464.8 1921.05   474.6 1925.78   477.9 1926.01  559.67 1926.16   746.3 1926.67
     802 1928.28   824.9 1929.82   906.7  1931.5  990.041934.796  1021.3 1935.51
#Mann= 5 ,-1 , 0
       0     .12       0   441.9    .045       0   464.8     .12       0
  559.67     .06       0  990.04    .016       0
Bank Sta=441.9,464.8
XS Rating Curve= 0 ,0
Exp/Cntr=0.3,0.1

Type RM Length L Ch R = 1 ,30140   ,125,128,128.9
XS GIS Cut Line= 2
     2035510.794      164034.389     2034600.514      164703.819
#Sta/Elev= 30
       0  1976.2    32.8 1962.99    68.8 1945.76    88.4 1938.29   108.1  1932.6
   134.3 1927.99   147.4 1926.67   180.1 1925.84   268.6 1926.34   275.1 1925.76
   284.9 1922.39   291.5 1921.72     321 1924.02   340.6 1922.26   383.2 1924.37
  391.34  1921.8   396.1 1920.83   409.4 1921.23   411.1    1922   419.2 1924.25
   435.6 1923.61   474.9 1925.74  505.261925.908  861.231925.007   887.6 1925.52
  965.68 1930.44 1060.281934.987 1108.681937.567 1119.031938.028  1129.9 1938.62
#Mann= 9 ,-1 , 0
       0     .12       0  391.34    .045       0   411.1     .12       0
  505.26     .06       0  861.23     .12       0  965.68     .06       0
 1060.28    .016       0 1108.68     .06       0 1119.03     .08       0
#XS Ineff= 2 , 0
                          851.33         1934.93
Permanent Ineff=
       F       F
Bank Sta=391.34,411.1
XS Rating Curve= 0 ,0
Exp/Cntr=0.3,0.1

Type RM Length L Ch R = 1 ,30012   ,247.3,253.6,254.3
XS GIS Cut Line= 3
     2035470.647      163975.769      2035115.47      164168.079
      2034485.41      164592.491
#Sta/Elev= 30
       0 1956.22    19.5 1948.97    55.4 1937.84    84.7 1930.06     101 1927.03
   143.3 1925.45   289.9 1925.85   306.2 1925.22   322.5 1923.61   351.8 1924.61
   368.1 1923.13   381.1 1923.86   384.4 1923.47   390.9  1921.3   397.4 1920.31
   410.8 1921.04   436.6  1922.9   466.1 1923.04   479.2  1925.6   485.8 1925.91
  568.721925.276   669.1 1924.64   705.2 1925.72   832.8 1925.37   921.3 1926.32
   993.3 1929.12  1078.4 1933.68  1124.3  1935.3 1131.361936.081  1163.6 1937.32
#Mann= 5 ,-1 , 0
       0     .12       0   390.9    .045       0   410.8     .12       0
  568.72     .06       0 1131.36    .016       0
#XS Ineff= 2 , 0
                          875.75         1932.14
Permanent Ineff=
       F       F
Bank Sta=390.9,410.8
XS Rating Curve= 0 ,0
Exp/Cntr=0.3,0.1

Type RM Length L Ch R = 1 ,29758.4 ,790.3,777,759.9
XS GIS Cut Line= 2
     2035440.848      163837.782     2034399.994      164227.257
#Sta/Elev= 30
       0 1953.15    26.2 1943.37    42.6 1938.89    68.8 1935.68    88.5  1932.1
   121.3 1927.35   154.1 1925.58   180.3 1925.15   347.5 1925.54   350.8  1924.9
   357.3 1921.97   360.6 1920.66   367.2 1919.94   373.7 1922.15     377 1923.52
   380.3 1923.91   445.8 1924.82   481.9  1924.2     495 1922.44   521.2 1925.46
   550.8 1924.84   586.8 1925.18  618.561924.371     672 1925.21     754 1925.14
   773.7 1924.47   790.1 1925.24  941.251927.517  997.55 1927.97  1111.3 1928.96
#Mann= 6 ,-1 , 0
       0     .12       0   357.3    .045       0   373.7     .12       0
  618.56     .06       0  941.25    .016       0  997.55     .06       0
#XS Ineff= 2 , 0
                          826.91         1931.05
Permanent Ineff=
       F       F
Bank Sta=357.3,373.7
XS Rating Curve= 0 ,0
Exp/Cntr=0.3,0.1

Type RM Length L Ch R = 1 ,28981.4 ,78.9,79.1,79
XS GIS Cut Line= 4
     2035206.164      163230.454      2035035.41      163360.069
     2034616.139      164068.403     2034407.806       164185.59
#Sta/Elev= 30
       0 1938.21    7.561938.134   32.081937.619   191.6 1933.17   214.4 1930.34
   240.6  1928.6   263.6 1923.68   309.5 1923.11   319.3 1922.12     339 1922.85
   345.6  1921.4   355.4 1919.31     362 1920.01   365.6 1921.65   375.1 1923.26
   407.9 1922.73   424.2 1923.46   440.6 1921.73   460.3 1923.75     480 1921.87
   575.1 1923.44     621 1922.86   663.6 1924.86  734.271924.945  921.08 1925.23
 1006.071926.158 1042.591926.548 1046.431926.765 1142.121927.457  1276.5 1928.36
#Mann= 11 ,-1 , 0
       0     .12       0    7.56    .016       0   32.08     .12       0
   345.6    .045       0   365.6     .12       0  734.27     .06       0
  921.08    .016       0 1006.07     .08       0 1042.59     .06       0
 1046.43    .016       0 1142.12     .06       0
Bank Sta=345.6,365.6
XS Rating Curve= 0 ,0
Exp/Cntr=0.3,0.1

Type RM Length L Ch R = 1 ,28902.3 ,56.8,60.6,62.9
XS GIS Cut Line= 4
     2035154.081      163175.766     2034983.327      163305.382
     2034564.056      164013.715     2034355.723      164130.903
#Sta/Elev= 30
       0 1932.67  187.431930.569   230.8 1929.93  290.191924.766   335.7 1923.71
   342.3 1920.97   352.1 1918.91   360.2  1920.9   365.2  1922.2   378.3 1922.74
   430.8 1920.45  546.581923.412  554.741923.354  589.061923.795  600.641923.918
  623.391924.131  657.711924.349  658.631924.363  692.041924.294  716.631924.428
  766.03 1924.37  790.751924.305  829.341924.241  832.621924.265  932.321924.817
  948.621924.894  1155.4 1926.54  1201.2 1927.86  1224.1  1927.1  1276.5 1928.47
#Mann= 20 ,-1 , 0
       0     .06       0  187.43    .016       0  290.19     .12       0
   342.3    .045       0   360.2     .12       0  546.58     .06       0
  554.74     .12       0  589.06    .016       0  600.64     .06       0
  623.39     .12       0  657.71    .016       0  658.63     .06       0
  692.04     .12       0  716.63     .06       0  766.03     .12       0
  790.75     .06       0  829.34     .12       0  832.62     .06       0
  932.32     .12       0  948.62     .06       0
Bank Sta=342.3,360.2
XS Rating Curve= 0 ,0
Exp/Cntr=0.3,0.1

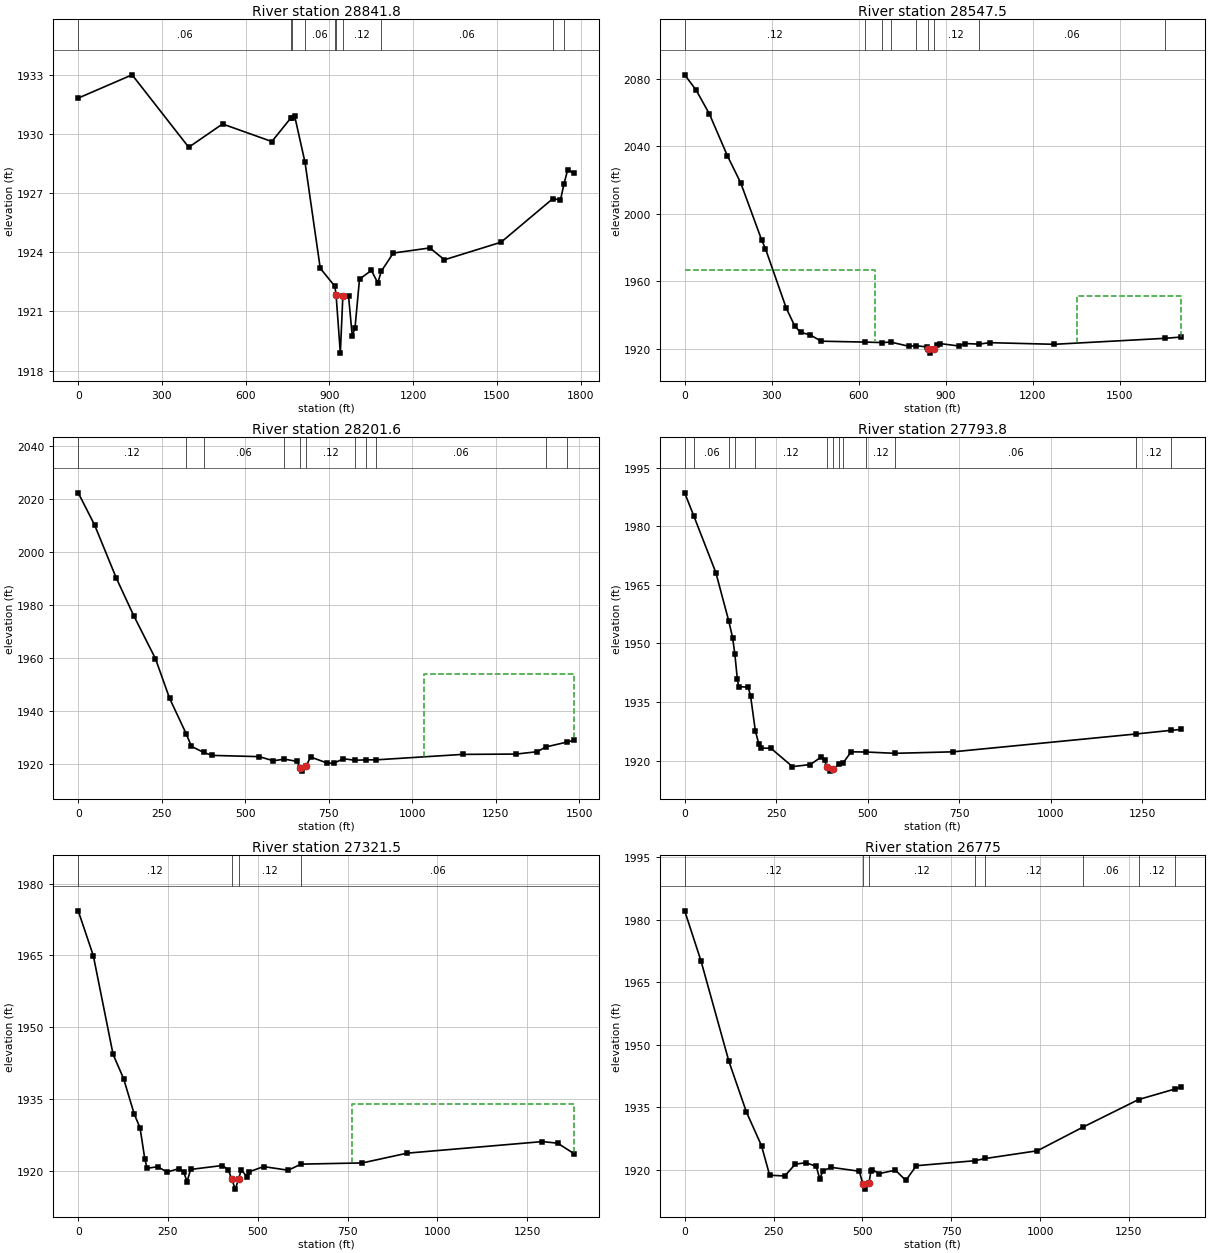
Type RM Length L Ch R = 1 ,28841.8 ,295.8,294.3,289.2
XS GIS Cut Line= 3
     2035571.348      162826.161     2035032.661       163168.29
     2034362.776      164089.236
#Sta/Elev= 30
       0 1931.81   193.1 1932.99     396 1929.32   517.1  1930.5   693.8 1929.61
  761.211930.792  766.651930.797   775.6  1930.9  812.721928.552   867.2 1923.19
  919.651922.276  924.06 1921.82   939.2 1918.89   948.2 1921.76   968.7 1921.76
   981.8 1919.78   991.6 1920.14  1007.9 1922.64  1050.5 1923.08  1073.4 1922.45
  1086.21923.045    1129 1923.96  1259.9 1924.22  1312.3 1923.62  1515.2 1924.51
 1701.251926.724  1727.9 1926.64 1740.371927.453    1754 1928.19    1777    1928
#Mann= 10 ,-1 , 0
       0     .06       0  761.21     .12       0  766.65    .016       0
  812.72     .06       0  919.65     .12       0  924.06    .045       0
   948.2     .12       0  1086.2     .06       0 1701.25    .016       0
 1740.37     .12       0
Bank Sta=924.06,948.2
XS Rating Curve= 0 ,0
Exp/Cntr=0.3,0.1

Type RM Length L Ch R = 1 ,28547.5 ,344.5,345.8,343.4
XS GIS Cut Line= 3
     2034739.317      162456.803     2034763.817      163055.382
     2034229.963       164029.34
#Sta/Elev= 30
       0 2082.41    39.3 2073.42    85.1 2059.26   147.3 2034.44   193.2 2018.38
   265.2 1984.65   278.3 1979.49   350.3 1944.14   379.7 1933.52   399.4  1929.9
   432.1 1928.34   471.4  1924.6   620.81924.075  681.721923.783  710.061924.084
   772.7  1921.6  797.351921.975     835 1921.15   838.6 1919.97   844.8 1917.53
   857.9 1919.79     871  1922.5   880.8 1923.17   946.4 1921.74     966 1923.22
 1015.231922.862  1051.2 1923.73    1274 1922.76 1656.351926.305  1709.8 1927.04
#Mann= 9 ,-1 , 0
       0     .12       0   620.8    .016       0  681.72     .12       0
  710.06     .06       0  797.35     .12       0   838.6    .045       0
   857.9     .12       0 1015.23     .06       0 1656.35    .016       0
#XS Ineff= 2 , 0
          657.32 1966.67 1351.27         1951.19
Permanent Ineff=
       F       F
Bank Sta=838.6,857.9
XS Rating Curve= 0 ,0
Exp/Cntr=0.3,0.1

Type RM Length L Ch R = 1 ,28201.6 ,402.4,407.8,401.5
XS GIS Cut Line= 3
     2034529.681      162617.828     2034522.025      162936.983
     2033961.734      163959.028
#Sta/Elev= 30
       0 2022.26    48.9 2010.18     114 1990.13   166.1 1975.99   231.3 1959.74
   273.6 1944.78  323.411931.411   338.9  1926.7  375.461924.398   401.1 1923.28
   541.9 1922.81   584.4 1921.25  617.311921.875   656.5 1920.99     663  1918.5
   669.6 1917.35   682.7  1919.4   695.8 1922.67   744.9 1920.41   764.5 1920.29
     794 1922.01  828.771921.454  862.431921.596  891.911921.603  1150.8 1923.66
  1311.3 1923.78  1373.5 1924.66 1400.711926.482 1464.291928.329  1484.8 1928.98
#Mann= 11 ,-1 , 0
       0     .12       0  323.41    .016       0  375.46     .06       0
  617.31     .12       0     663    .045       0   682.7     .12       0
  828.77     .06       0  862.43     .12       0  891.91     .06       0
 1400.71     .12       0 1464.29     .06       0
#XS Ineff= 2 , 0
                         1035.61         1953.83
Permanent Ineff=
       F       F
Bank Sta=663,682.7
XS Rating Curve= 0 ,0
Exp/Cntr=0.3,0.1

Type RM Length L Ch R = 1 ,27793.8 ,474.6,472.3,447.8
XS GIS Cut Line= 2
     2034319.575      162685.357     2033737.776      163909.548
#Sta/Elev= 30
       0 1988.52   25.361982.501    85.1 1968.12  120.59 1955.67     131 1951.44
  137.071947.297     144 1940.78   147.3 1938.92   173.5 1938.77   180.1 1936.52
  193.111927.611     203 1924.11   209.5 1923.18   235.7 1923.14   294.6 1918.44
   343.8 1918.98   373.2 1920.92     383 1920.02  388.691918.225   396.2 1917.29
     406 1917.82  421.441919.043  433.241919.445   455.1 1922.23  495.911922.181
  574.211921.848   733.4 1922.23 1234.761926.809 1329.561927.734  1355.4 1927.96
#Mann= 13 ,-1 , 0
       0     .12       0   25.36     .06       0  120.59     .12       0
  137.07    .016       0  193.11     .12       0  388.69    .045       0
     406     .06       0  421.44     .12       0  433.24     .06       0
  495.91     .12       0  574.21     .06       0 1234.76     .12       0
 1329.56     .06       0
Bank Sta=388.69,406
XS Rating Curve= 0 ,0
Exp/Cntr=0.3,0.1

Type RM Length L Ch R = 1 ,27321.5 ,538.9,546.5,544.9
XS GIS Cut Line= 3
     2034004.475       162580.38      2033990.38      162696.007
     2033526.439      163872.308
#Sta/Elev= 30
       0 1974.32    42.1 1964.93    97.1  1944.3   126.3 1939.24   155.8 1931.86
   172.2 1928.93   185.3  1922.5   191.8 1920.48   221.3  1920.8   247.5 1919.69
   280.3  1920.4   293.4 1919.74   303.2 1917.69     313 1920.24   401.5 1921.06
   417.9 1920.19   427.7 1918.14   437.5 1916.12   446.6 1918.23   453.9 1920.14
   470.3 1918.68   476.8 1919.76   516.1 1920.83   584.9 1920.07  620.241921.347
   791.3  1921.6   915.8 1923.64  1292.5 1926.06  1335.1 1925.73    1381 1923.52
#Mann= 4 ,-1 , 0
       0     .12       0   427.7    .045       0   446.6     .12       0
  620.24     .06       0
#XS Ineff= 2 , 0
                          761.33            1934
Permanent Ineff=
       F       F
Bank Sta=427.7,446.6
XS Rating Curve= 0 ,0
Exp/Cntr=0.3,0.1

Type RM Length L Ch R = 1 ,26775   ,477.3,478.9,463
XS GIS Cut Line= 2
     2033883.925      162468.442     2033238.244      163705.641
#Sta/Elev= 30
       0 1982.16    45.9 1970.12   124.5 1945.98   173.6 1933.85   216.2 1925.71
   239.1 1918.63   281.7 1918.45   311.2 1921.29   340.7 1921.63   370.2 1920.78
     380 1917.78   389.8 1919.76   412.8 1920.52   491.4 1919.59   501.2 1916.59
   507.8 1915.29  518.66  1916.8   524.2 1919.66   527.4 1919.99   547.1 1919.02
     593 1919.84   622.4 1917.38   651.9 1920.92  816.051922.111  846.421922.652
   992.6 1924.51 1120.281930.166 1277.131936.809 1380.48 1939.37  1395.6 1939.75
#Mann= 8 ,-1 , 0
       0     .12       0   501.2    .045       0  518.66     .12       0
  816.05     .06       0  846.42     .12       0 1120.28     .06       0
 1277.13     .12       0 1380.48     .06       0
Bank Sta=501.2,518.66
XS Rating Curve= 0 ,0
Exp/Cntr=0.3,0.1

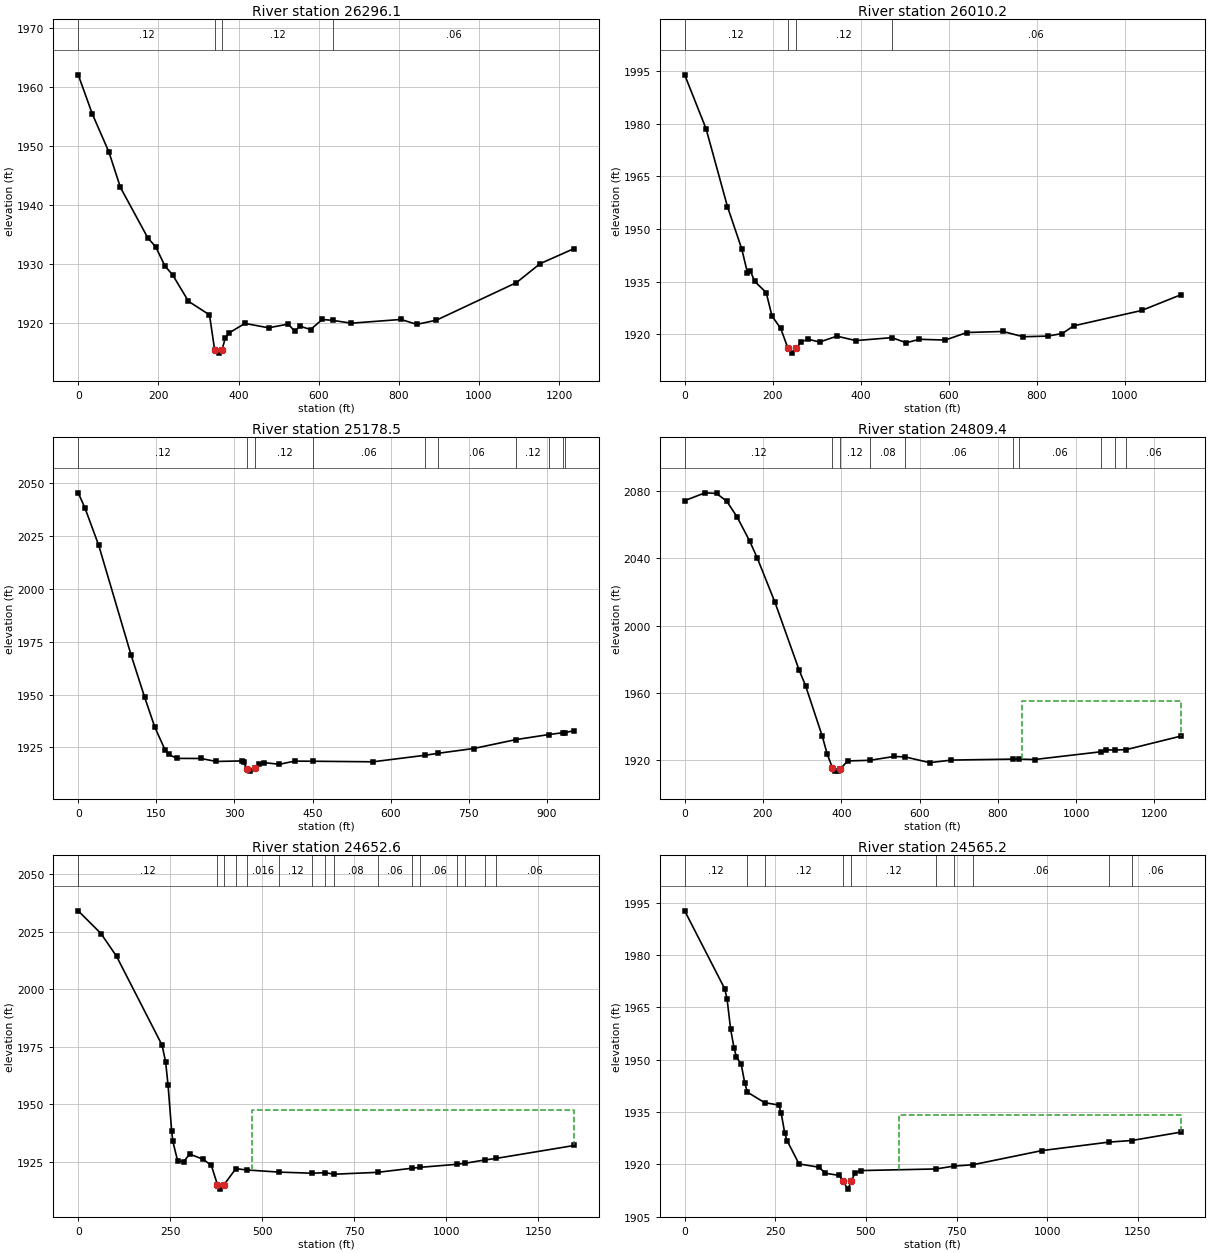
Type RM Length L Ch R = 1 ,26296.1 ,284.5,285.9,283.4
XS GIS Cut Line= 3
     2033745.588      162383.507     2033649.234      162446.007
     2033159.651      163456.423
#Sta/Elev= 30
       0 1962.03    35.1 1955.42    76.6 1948.96   105.3 1942.97   173.8 1934.41
   193.4 1932.91   216.3 1929.68     236 1928.12   275.2 1923.68   327.6 1921.39
   340.7 1915.36   350.5 1914.91  358.55  1915.4   366.9 1917.44   376.7 1918.34
     416 1919.94   474.9  1919.2     524 1919.82   540.4 1918.62   553.5 1919.48
   579.7  1918.9   609.1 1920.61  635.451920.451   681.2 1919.98   805.5 1920.61
   844.8 1919.78   893.9 1920.49  1093.6 1926.85  1152.5 1930.05  1237.6 1932.62
#Mann= 4 ,-1 , 0
       0     .12       0   340.7    .045       0  358.55     .12       0
  635.45     .06       0
Bank Sta=340.7,358.55
XS Rating Curve= 0 ,0
Exp/Cntr=0.3,0.1

Type RM Length L Ch R = 1 ,26010.2 ,820.1,831.7,826.7
XS GIS Cut Line= 3
     2033352.359      162287.153     2033401.838      162427.778
     2033016.422      163326.215
#Sta/Elev= 30
       0  1993.9    48.6 1978.54    97.2 1956.38   129.6 1944.36   142.6 1937.56
   149.1  1938.1   158.9 1935.12   185.2 1931.91   198.3 1925.26     218 1921.74
   234.1 1916.26   244.2 1914.68     254 1916.01   263.9 1917.86   280.3 1918.63
   306.5 1917.84   345.9 1919.51   388.6 1918.25  470.711919.087   503.4 1917.63
   532.9 1918.62     592  1918.4   641.2 1920.55   723.2 1920.84   769.1 1919.34
   824.9 1919.53   857.7 1920.26   883.9 1922.45  1038.1 1926.82  1126.7 1931.26
#Mann= 4 ,-1 , 0
       0     .12       0   234.1    .045       0     254     .12       0
  470.71     .06       0
Bank Sta=234.1,254
XS Rating Curve= 0 ,0
Exp/Cntr=0.3,0.1

Type RM Length L Ch R = 1 ,25178.5 ,370.4,369.1,364
XS GIS Cut Line= 2
     2033055.484      162292.361      2032771.63      163201.215
#Sta/Elev= 30
       0 2045.56    13.1 2038.27    39.3 2020.75   101.4 1968.82   127.6 1948.69
   147.2 1934.46   166.9 1923.71   173.4 1921.64   189.8 1919.76   235.6 1919.72
     265 1918.31   314.1 1918.56   317.4    1918   323.6 1914.84   330.5 1913.73
   340.3 1915.28   346.8    1917   356.6 1917.79   386.1 1916.96   415.5 1918.47
  451.611918.412     566 1918.15   665.81921.237  690.821922.174   759.1 1924.44
  840.611928.671  903.841931.067  931.06 1931.94  934.791932.002   952.2 1932.88
#Mann= 10 ,-1 , 0
       0     .12       0   323.6    .045       0   340.3     .12       0
  451.61     .06       0   665.8     .12       0  690.82     .06       0
  840.61     .12       0  903.84     .06       0  931.06     .08       0
  934.79    .016       0
Bank Sta=323.6,340.3
XS Rating Curve= 0 ,0
Exp/Cntr=0.3,0.1

Type RM Length L Ch R = 1 ,24809.4 ,157.2,156.8,154.8
XS GIS Cut Line= 3
     2033027.642      162134.164     2032768.626      162325.085
     2032654.998      163263.453
#Sta/Elev= 30
       0 2074.29      52 2078.93    81.3 2078.56   107.3 2073.98   133.3 2064.85
   165.8 2050.41   185.3 2040.31   230.8 2013.84   292.5 1973.61   308.8 1964.43
   351.2 1934.63   364.3  1923.7   377.4 1915.67   383.9 1913.85   390.5 1913.68
     397 1914.87   416.6 1919.73  473.491920.107   534.4 1922.37  562.751922.151
     626 1918.71   681.6 1920.24  837.611920.811  853.541920.785   894.1 1920.58
 1062.361925.147  1077.3 1926.31 1098.341926.199  1128.11926.449    1267 1934.43
#Mann= 10 ,-1 , 0
       0     .12       0   377.4    .045       0     397     .12       0
  473.49     .08       0  562.75     .06       0  837.61     .08       0
  853.54     .06       0 1062.36    .016       0 1098.34     .08       0
  1128.1     .06       0
#XS Ineff= 2 , 0
                          862.63         1955.29
Permanent Ineff=
       F       F
Bank Sta=377.4,397
XS Rating Curve= 0 ,0
Exp/Cntr=0.3,0.1

Type RM Length L Ch R = 1 ,24652.6 ,87.7,87.4,87.5
XS GIS Cut Line= 3
     2032867.939      162043.897     2032631.005      162232.465
     2032545.067      163274.132
#Sta/Elev= 30
       0 2034.11    61.9 2024.23   104.2 2014.33   227.9 1975.72   237.7 1968.32
   244.2 1958.29     254  1938.5   257.2 1933.87   270.2 1925.44   286.5 1925.01
   302.8 1928.37   338.8 1926.15   361.8 1923.48   378.5 1914.99   384.7 1913.13
  395.99 1914.96  428.311922.018  457.951921.466  546.87 1920.52  635.781920.047
  671.361920.279  695.061919.614  813.621920.425  906.541922.204   928.91922.597
 1030.791923.947 1051.99 1924.38  1105.6 1925.82 1135.541926.471    1348  1932.1
#Mann= 16 ,-1 , 0
       0     .12       0   378.5    .045       0  395.99     .12       0
  428.31     .08       0  457.95    .016       0  546.87     .12       0
  635.78     .06       0  671.36    .016       0  695.06     .08       0
  813.62     .06       0  906.54     .08       0   928.9     .06       0
 1030.79    .016       0 1051.99     .08       0  1105.6    .016       0
 1135.54     .06       0
#XS Ineff= 2 , 0
                          472.47         1947.33
Permanent Ineff=
       F       F
Bank Sta=378.5,395.99
XS Rating Curve= 0 ,0
Exp/Cntr=0.3,0.1

Type RM Length L Ch R = 1 ,24565.2 ,174.3,186.6,197
XS GIS Cut Line= 3
     2032789.814      161986.605      2032552.88      162128.298
     2032466.942       163216.84
#Sta/Elev= 30
       0 1992.69   110.4 1970.36   116.9 1967.46   126.7 1958.77   136.4 1953.23
   142.9 1950.76   155.9 1948.75   165.6 1943.36  173.141940.694  220.321937.694
   259.8    1937   266.3 1934.66   276.1 1928.88   282.6 1926.77   315.4 1920.12
   371.2 1919.17   387.6 1917.46   426.9 1916.82   436.7 1915.27   449.9  1912.9
   459.7 1915.13   469.5 1917.55   485.9 1918.22  692.57 1918.68  743.071919.507
  794.44 1919.88   984.4 1923.93 1170.931926.389 1232.591926.832    1368 1929.23
#Mann= 10 ,-1 , 0
       0     .12       0  173.14    .016       0  220.32     .12       0
   436.7    .045       0   459.7     .12       0  692.57     .06       0
  743.07     .12       0  794.44     .06       0 1170.93     .08       0
 1232.59     .06       0
#XS Ineff= 2 , 0
                          590.39         1934.17
Permanent Ineff=
       F       F
Bank Sta=436.7,459.7
XS Rating Curve= 0 ,0
Exp/Cntr=0.3,0.1

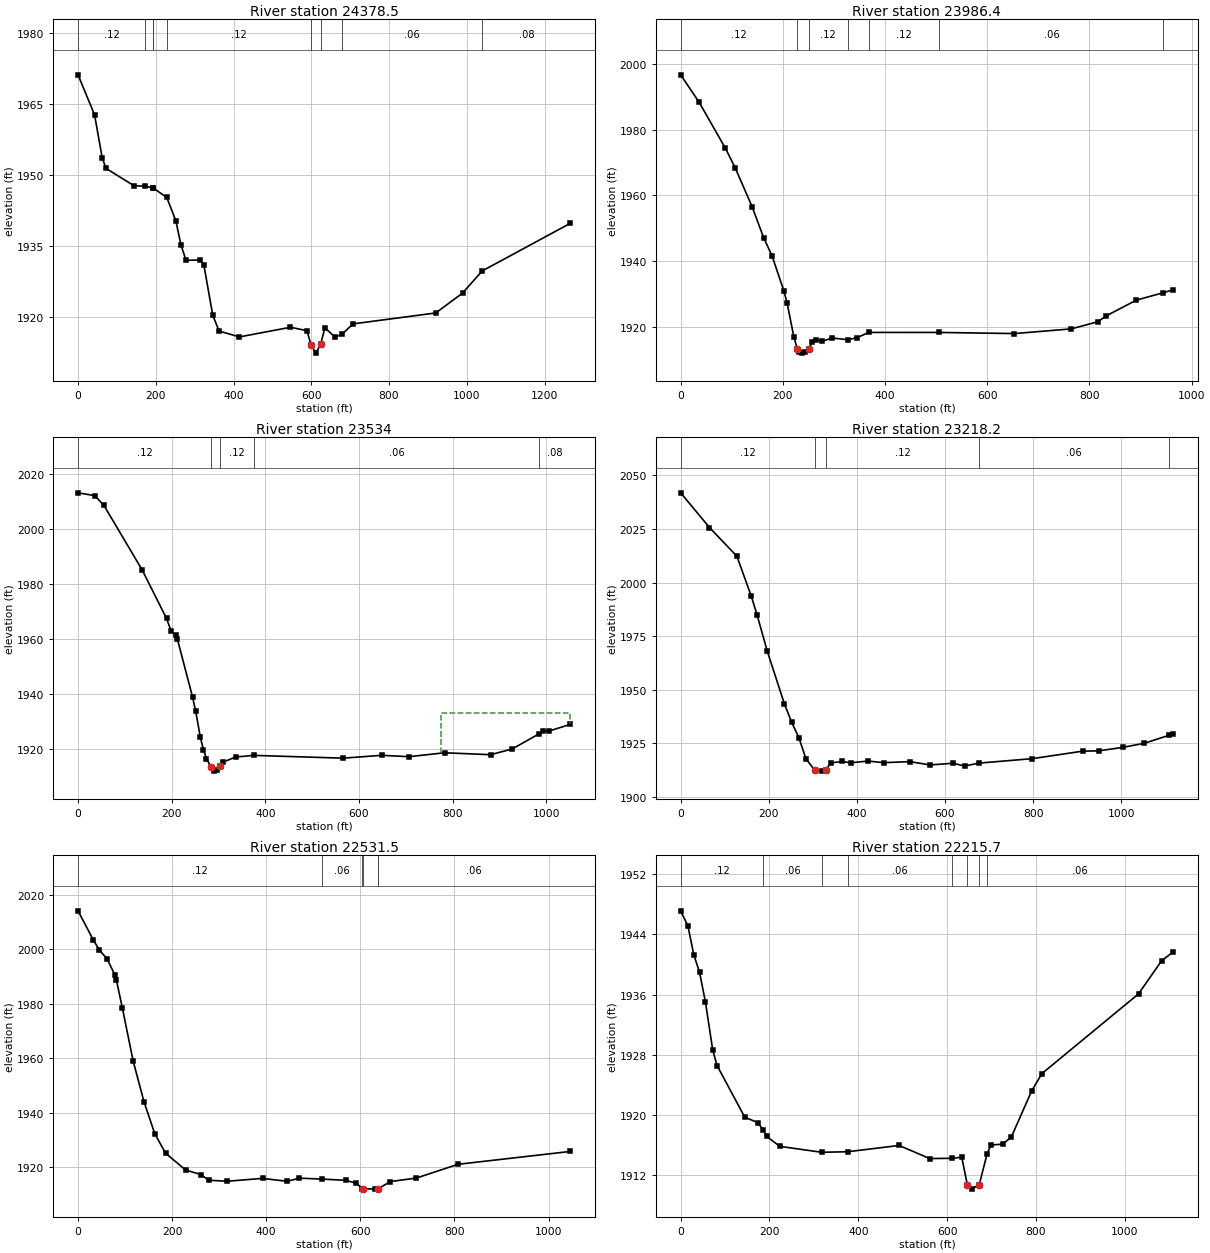
Type RM Length L Ch R = 1 ,24378.5 ,389.5,392.2,392.2
XS GIS Cut Line= 4
     2032789.859      161865.278     2032516.422      162050.173
     2032138.817      162656.944     2032024.234      162847.048
#Sta/Elev= 30
       0 1971.15    42.5 1962.71    62.1 1953.65    71.9  1951.4   143.8 1947.75
   172.51947.629  192.651947.287  193.241947.259  228.311945.271   251.6 1940.33
   264.7 1935.27   277.8 1931.99   313.7 1932.08   323.6 1931.04   346.5 1920.42
   362.9 1917.06   415.3 1915.83   546.4 1917.87   589.1 1917.14   598.9 1914.18
     612 1912.41   623.9 1914.28     635 1917.76   661.2 1915.77  678.551916.354
   707.1 1918.58   920.2 1920.89     989 1925.08 1039.521929.748  1266.7 1939.83
#Mann= 9 ,-1 , 0
       0     .12       0   172.5    .016       0  192.65     .08       0
  193.24    .016       0  228.31     .12       0   598.9    .045       0
   623.9     .12       0  678.55     .06       0 1039.52     .08       0
Bank Sta=598.9,623.9
XS Rating Curve= 0 ,0
Exp/Cntr=0.3,0.1

Type RM Length L Ch R = 1 ,23986.4 ,456.5,452.4,442.9
XS GIS Cut Line= 3
     2032482.567      161781.944     2032456.526      161899.132
     2031998.192      162607.465
#Sta/Elev= 30
       0 1996.62    35.7  1988.4    87.6 1974.32   107.1 1968.24   139.7 1956.61
   162.6 1947.09   178.9 1941.61   201.8 1931.09   208.3 1927.32   221.4 1917.13
     228 1913.43   231.2 1912.47   237.8  1912.1   244.3 1912.33   250.8 1913.46
   257.4 1915.38   263.9  1916.2     277 1915.72   296.6 1916.69  327.081916.178
   345.7 1916.81  367.931918.388  505.951918.382   653.1 1918.04   764.3 1919.46
   816.6 1921.64   832.9 1923.42   891.8  1928.2  944.761930.456   963.7 1931.33
#Mann= 7 ,-1 , 0
       0     .12       0     228    .045       0   250.8     .12       0
  327.08     .06       0  367.93     .12       0  505.95     .06       0
  944.76     .08       0
Bank Sta=228,250.8
XS Rating Curve= 0 ,0
Exp/Cntr=0.3,0.1

Type RM Length L Ch R = 1 ,23534   ,318.2,315.8,312.6
XS GIS Cut Line= 3
     2032336.734      161669.965     2032167.463      161761.111
     2031825.189      162549.576
#Sta/Elev= 30
       0 2013.13    35.8 2012.11    55.4 2008.53   136.9 1985.13     189 1967.49
   198.8 1962.95   208.6 1961.31   211.9 1960.15   244.7 1938.88   251.3 1933.73
   261.2 1924.36   267.7 1919.84   274.3 1916.59   284.1 1913.52   290.7 1912.02
   297.2 1912.35   303.8 1913.72   310.4 1915.33   336.6 1917.15  375.06 1917.74
   566.2 1916.73   648.3 1917.76   707.3 1917.27   782.8 1918.69   881.2 1917.99
   927.1 1920.06  984.98 1925.59   992.8 1926.54  1005.9 1926.59  1051.8 1929.02
#Mann= 5 ,-1 , 0
       0     .12       0   284.1    .045       0   303.8     .12       0
  375.06     .06       0  984.98     .08       0
#XS Ineff= 2 , 0
                          775.35         1933.14
Permanent Ineff=
       F       F
Bank Sta=284.1,303.8
XS Rating Curve= 0 ,0
Exp/Cntr=0.3,0.1

Type RM Length L Ch R = 1 ,23218.2 ,684.1,686.8,680.5
XS GIS Cut Line= 3
      2031927.88      161443.403     2031664.859      162300.173
     2031657.047      162521.528
#Sta/Elev= 30
       0 2041.87    65.4 2025.69   127.6 2012.28   160.3 1993.64   173.4 1984.94
   196.3 1968.15   235.5 1943.37   251.9 1934.83   268.2 1927.66   284.6 1917.66
   304.2  1912.5   320.6 1912.01   330.4 1912.69   340.2 1915.83   366.3 1916.51
     386 1915.92   425.2 1916.69   461.2 1915.96   520.1 1916.44   565.9  1914.9
   618.2 1915.68   644.4  1914.4  677.871915.766   798.1 1917.83   912.5 1921.33
   948.4 1921.46  1003.7  1923.1  1052.6 1925.02 1108.861928.764  1117.7 1929.56
#Mann= 5 ,-1 , 0
       0     .12       0   304.2    .045       0   330.4     .12       0
  677.87     .06       0 1108.86     .08       0
Bank Sta=304.2,330.4
XS Rating Curve= 0 ,0
Exp/Cntr=0.3,0.1

Type RM Length L Ch R = 1 ,22531.5 ,314.2,315.7,315.5
XS GIS Cut Line= 4
     2031623.192      161443.403     2031563.687      161507.929
     2031479.963      162206.423     2031532.047      162456.423
#Sta/Elev= 30
       0 2014.11    32.5 2003.41    45.5 1999.67    61.8 1996.45      78 1990.67
    81.3 1988.86    94.3 1978.35   117.2  1958.9   140.1 1944.04     163 1932.27
   185.9 1925.12   228.5 1918.92   261.2 1917.24   277.6 1915.16   316.8 1914.78
   392.1 1915.84   444.4 1914.76   470.6 1915.92   518.71915.572   568.8 1915.13
   591.7 1914.05  604.291912.117   604.7 1912.07   630.9 1911.89   637.5    1912
  637.711912.014   663.7 1914.66   719.3 1915.97   807.6 1921.01  1046.6 1925.74
#Mann= 6 ,-1 , 0
       0     .12       0   518.7     .06       0  604.29     .12       0
   604.7    .045       0   637.5     .12       0  637.71     .06       0
Bank Sta=604.7,637.5
XS Rating Curve= 0 ,0
Exp/Cntr=0.3,0.1

Type RM Length L Ch R = 1 ,22215.7 ,540.1,549.2,557.7
XS GIS Cut Line= 3
     2031305.484      161443.403      2031177.88      162276.736
     2031006.005      162479.861
#Sta/Elev= 30
       0 1947.12    16.4  1945.1    29.5  1941.3    42.6 1938.94    55.8    1935
    72.2 1928.64      82 1926.57   144.3 1919.72   173.9 1918.99  185.481918.049
   193.5 1917.18   223.1 1915.84  317.981915.051  376.371915.127     492 1915.96
   560.9 1914.22  610.861914.254   633.1  1914.4   645.8 1910.68   656.1 1910.16
   672.5 1910.77  690.081914.817   698.7 1916.01     725 1916.14   744.6 1917.06
   790.6 1923.21   813.5  1925.5  1031.2 1936.09  1083.2 1940.49  1109.1 1941.65
#Mann= 8 ,-1 , 0
       0     .12       0  185.48     .06       0  317.98     .12       0
  376.37     .06       0  610.86     .12       0   645.8    .045       0
   672.5     .12       0  690.08     .06       0
Bank Sta=645.8,672.5
XS Rating Curve= 0 ,0
Exp/Cntr=0.3,0.1