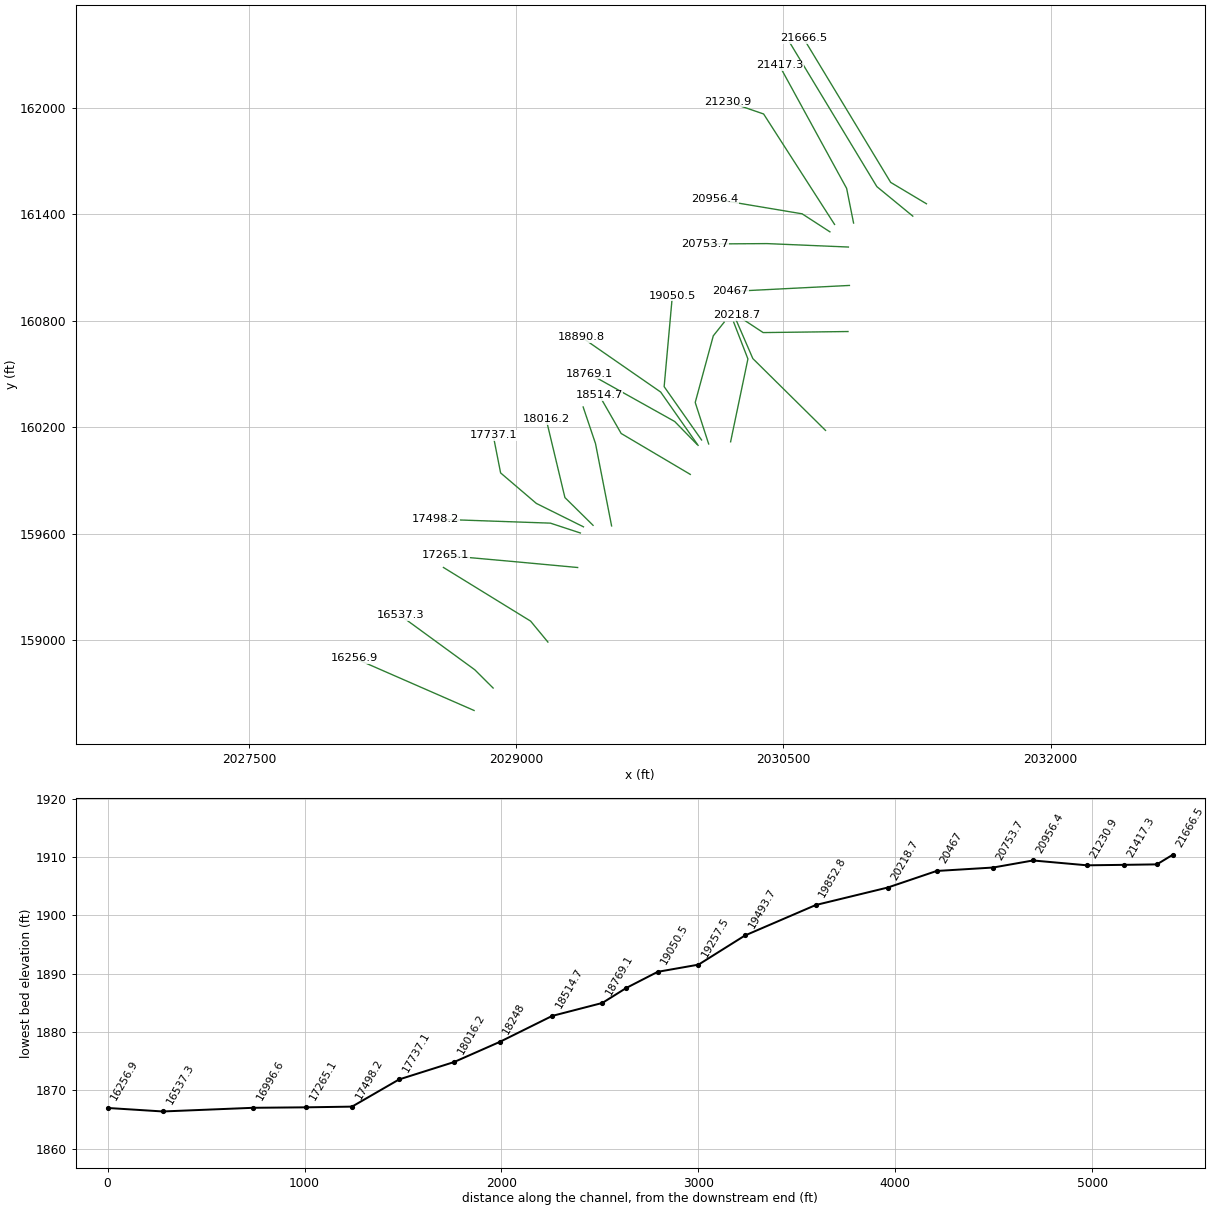
HEC-RAS study BRUSHCK.prj: BRUSHCK

--- BRUSHCK.g01 (geometry) --- (continued)

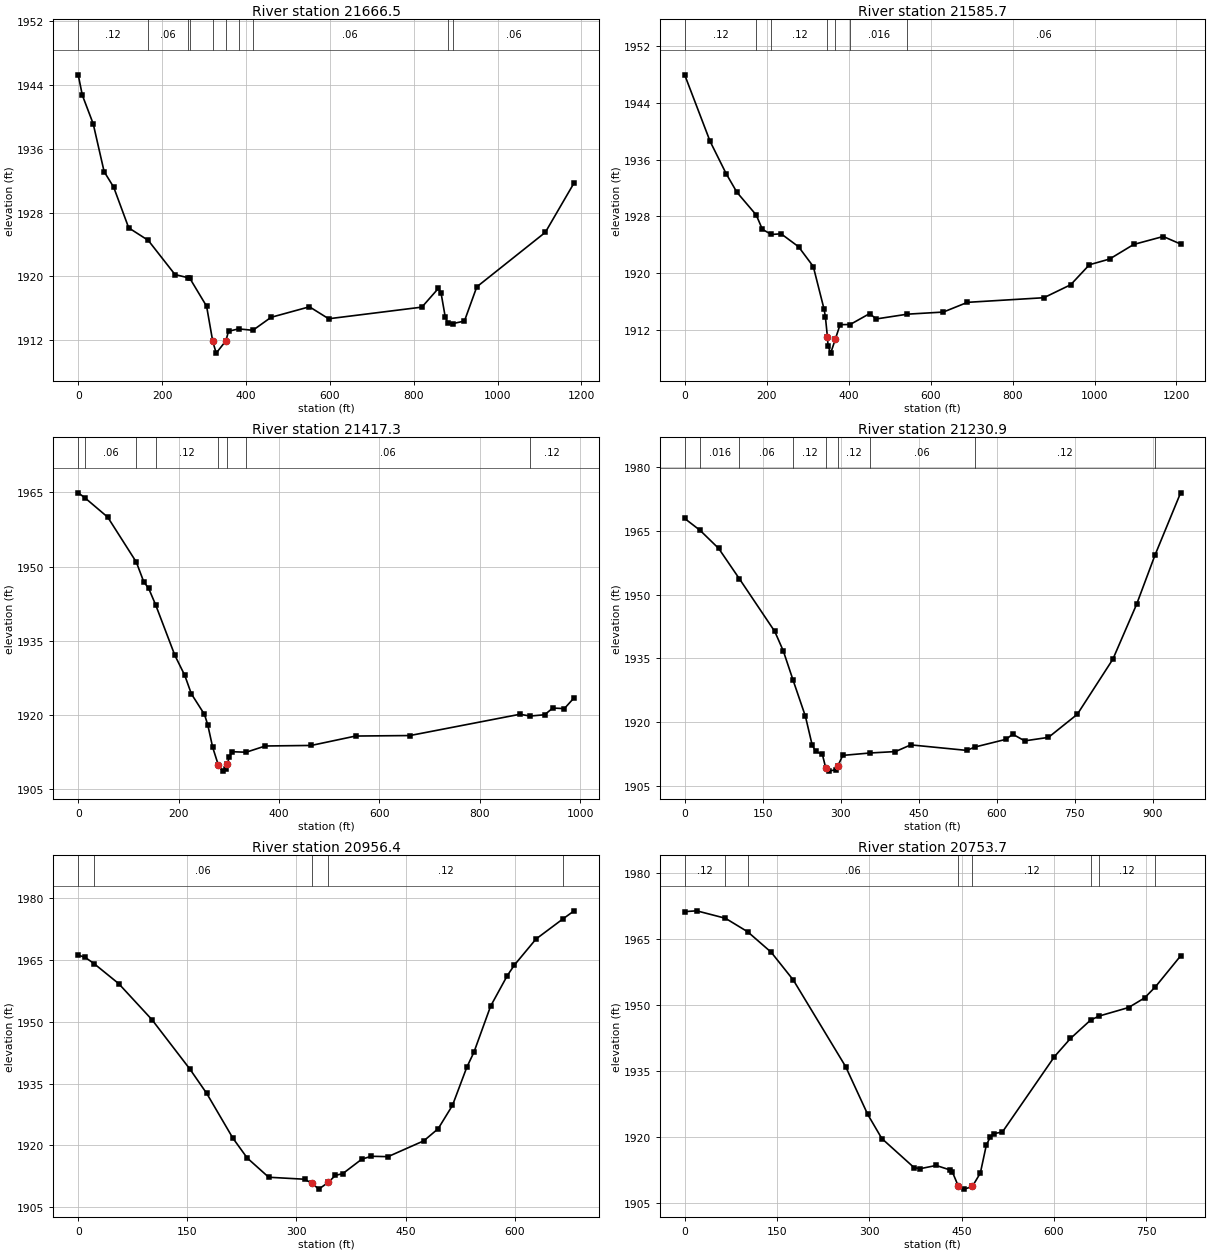
Type RM Length L Ch R = 1 ,21666.5 ,80.4,80.8,80.9
XS GIS Cut Line= 3
     2031303.195      161458.352     2031102.359      161578.819
     2030612.776      162391.319
#Sta/Elev= 30
       0 1945.29     9.8 1942.74    35.8 1939.14    61.8 1933.15    84.6  1931.2
   120.4  1926.1  167.011924.531   230.9 1920.24  261.651919.852  265.551919.828
   306.2 1916.27  320.86 1911.86   329.1 1910.39     352 1911.92   358.5 1913.13
  382.48 1913.43  416.531913.252   459.9 1914.88   551.5  1916.2   597.3  1914.7
   819.7 1916.16     859 1918.51   865.5 1917.89   875.3 1914.94   881.31914.201
  893.491914.095   921.1 1914.41   950.6  1918.7  1114.1 1925.54  1182.8 1931.75
#Mann= 10 ,-1 , 0
       0     .12       0  167.01     .06       0  261.65     .12       0
  265.55    .016       0  320.86    .045       0     352    .016       0
  382.48     .12       0  416.53     .06       0   881.3     .08       0
  893.49     .06       0
Bank Sta=320.86,352
XS Rating Curve= 0 ,0
Exp/Cntr=0.3,0.1

Type RM Length L Ch R = 1 ,21585.7 ,169.2,168.4,167.2
XS GIS Cut Line= 3
     2031226.595      161388.688      2031024.76      161554.925
     2030535.177      162367.425
#Sta/Elev= 30
       0 1947.96    62.1 1938.57   101.3 1934.02   127.5  1931.4  174.541928.205
   189.6 1926.18  211.591925.455   235.3 1925.55   277.8 1923.73   313.8 1920.94
     340 1914.95   343.3 1913.87  348.39 1910.96   349.8 1909.74   356.3 1908.73
   367.9 1910.76   379.2 1912.74  403.821912.765   451.2  1914.3   467.6 1913.55
  543.561914.222   631.1 1914.52     690 1915.89   876.4 1916.54   941.9 1918.37
   987.6 1921.19  1036.7 1921.99  1095.6 1924.05  1167.6 1925.17  1210.1 1924.11
#Mann= 7 ,-1 , 0
       0     .12       0  174.54    .016       0  211.59     .12       0
  348.39    .045       0   367.9     .12       0  403.82    .016       0
  543.56     .06       0
Bank Sta=348.39,367.9
XS Rating Curve= 0 ,0
Exp/Cntr=0.3,0.1

Type RM Length L Ch R = 1 ,21417.3 ,184.5,186.4,187.6
XS GIS Cut Line= 3
     2030894.026      161349.653     2030854.963      161544.965
     2030477.359      162237.673
#Sta/Elev= 30
       0 1964.89   12.851963.925    58.8 1959.97  115.781950.888   130.6  1946.9
   140.4 1945.57  154.161942.283   192.6 1932.04   212.3    1928   225.4 1924.27
   251.6  1920.1   258.1    1918   267.9 1913.46   278.9 1909.96   287.6 1908.65
   293.9 1909.06   297.4 1910.06   300.7 1911.49   307.2 1912.57  334.641912.471
   372.7 1913.73   464.3 1913.84   552.7 1915.74   660.8 1915.84   880.1 1920.14
  900.321919.781   929.2 1920.04   945.6  1921.4   968.5 1921.28   988.1 1923.48
#Mann= 8 ,-1 , 0
       0     .12       0   12.85     .06       0  115.78    .016       0
  154.16     .12       0   278.9    .045       0   297.4     .12       0
  334.64     .06       0  900.32     .12       0
Bank Sta=278.9,297.4
XS Rating Curve= 0 ,0
Exp/Cntr=0.3,0.1

Type RM Length L Ch R = 1 ,21230.9 ,255,274.5,292.9
XS GIS Cut Line= 3
     2030787.255       161341.84     2030388.817      161964.236
     2030185.692      162034.548
#Sta/Elev= 30
       0 1967.85   29.711965.059    65.4 1960.82  105.381953.675   173.3 1941.34
   189.7 1936.78  208.711929.846   232.2 1921.45   245.2 1914.72   251.8 1913.24
   264.9 1912.48   271.4 1909.28   277.9 1908.57     291 1908.92   294.7 1909.82
   304.1 1912.26  355.921912.821   405.5 1913.16   434.9 1914.73   542.8 1913.43
  557.711914.204     618 1916.03   631.1 1917.23     654 1915.67   699.8 1916.49
   755.3 1921.91   823.7 1934.84   869.3  1947.7  904.651959.237     954 1973.87
#Mann= 9 ,-1 , 0
       0     .06       0   29.71    .016       0  105.38     .06       0
  208.71     .12       0   271.4    .045       0   294.7     .12       0
  355.92     .06       0  557.71     .12       0  904.65     .06       0
Bank Sta=271.4,294.7
XS Rating Curve= 0 ,0
Exp/Cntr=0.3,0.1

Type RM Length L Ch R = 1 ,20956.4 ,199.6,202.7,206.7
XS GIS Cut Line= 3
     2030761.213      161300.173     2030604.963      161401.736
     2030116.543      161483.953
#Sta/Elev= 30
       0 1966.13     9.8 1965.54   22.061964.012    55.6 1959.21   101.4 1950.46
   153.7 1938.44   176.6  1932.6   212.6 1921.75   232.3 1916.94   261.8 1912.28
     311  1911.8   320.8 1910.87   330.7  1909.4   343.8 1911.06   353.6 1912.75
   363.5 1913.14   389.7 1916.66   402.8 1917.36   425.8 1917.27     475 1921.11
   494.7 1924.04   514.4 1929.71     534 1938.91   543.9  1942.6   566.8 1953.75
   589.8 1961.17   599.6 1963.74   629.2 1970.02  666.741974.962   681.6 1976.85
#Mann= 5 ,-1 , 0
       0    .016       0   22.06     .06       0   320.8    .045       0
   343.8     .12       0  666.74     .06       0
Bank Sta=320.8,343.8
XS Rating Curve= 0 ,0
Exp/Cntr=0.3,0.1

Type RM Length L Ch R = 1 ,20753.7 ,282.4,286.7,285.7
XS GIS Cut Line= 3
     2030864.991      161214.525     2030407.809      161233.869
     2030059.601      161231.689
#Sta/Elev= 30
       0 1971.14    19.6 1971.32    66.21969.632  102.451966.558   140.6 1961.92
   176.5 1955.62   261.5 1935.99   297.4 1925.14   320.3 1919.67   372.6 1913.09
   382.4 1912.82   408.6 1913.56   431.4 1912.53   434.7 1912.17   444.5  1908.9
   454.3 1908.19   467.4 1908.79   480.4 1911.84   490.1 1918.17   496.6 1920.03
   503.2  1920.8   516.2 1921.14   600.8 1938.25   626.8 1942.36   659.4 1946.52
   673.21947.443   721.2 1949.38   747.2 1951.56  764.931954.094   805.8  1961.1
#Mann= 8 ,-1 , 0
       0     .12       0    66.2    .016       0  102.45     .06       0
   444.5    .045       0   467.4     .12       0   659.4     .06       0
   673.2     .12       0  764.93     .06       0
Bank Sta=444.5,467.4
XS Rating Curve= 0 ,0
Exp/Cntr=0.3,0.1

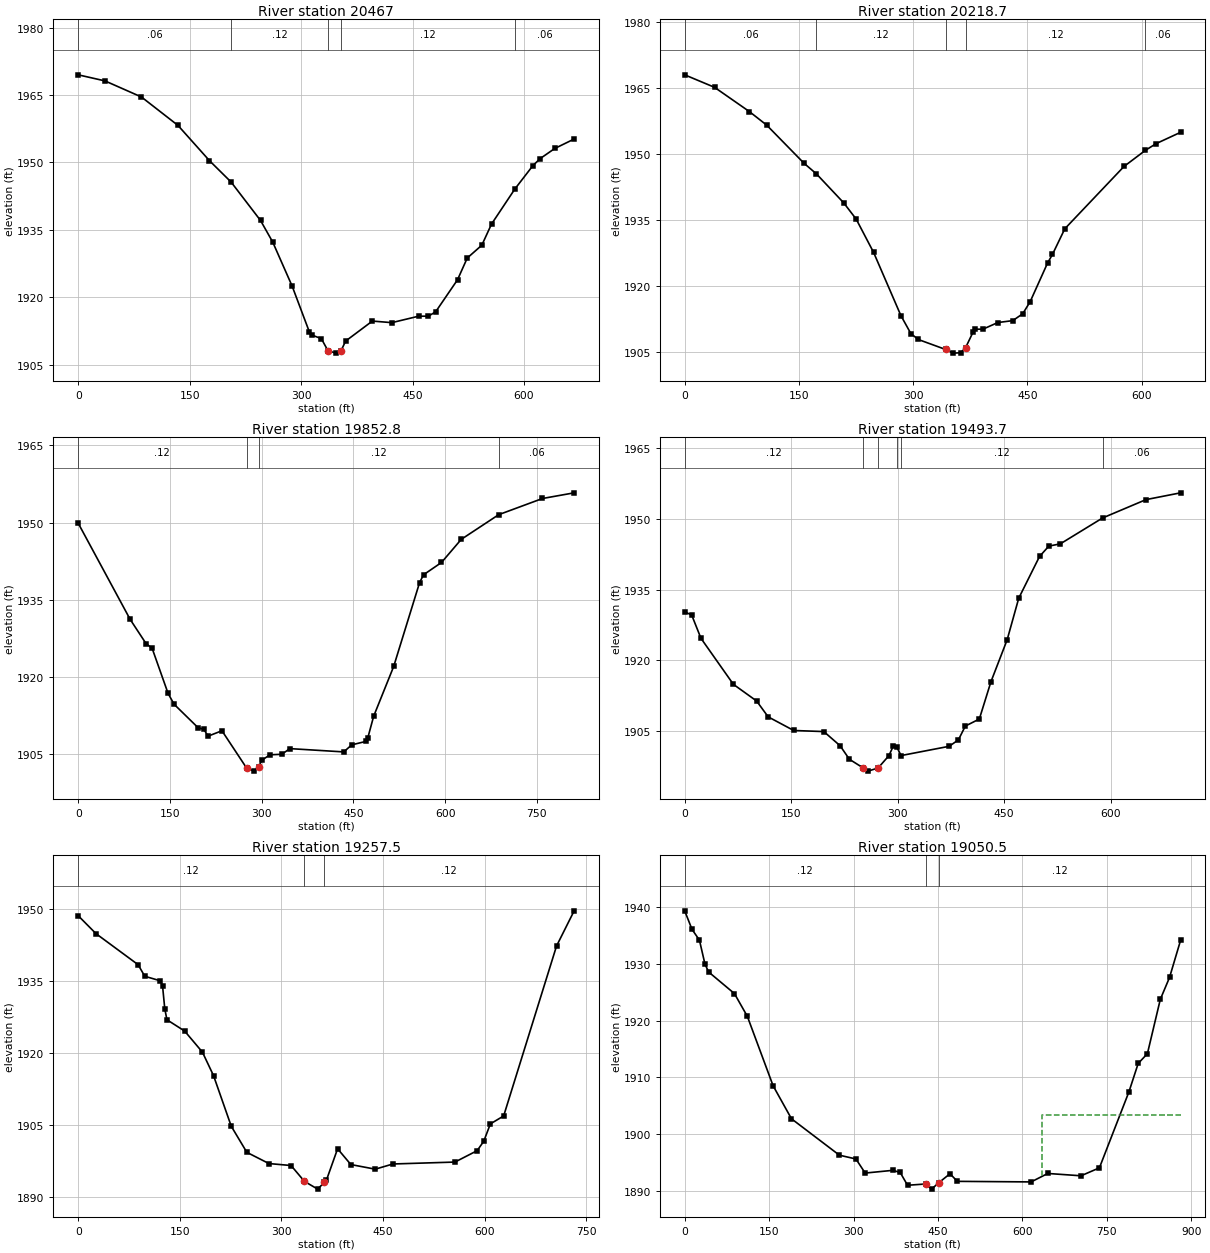
Type RM Length L Ch R = 1 ,20467   ,249.1,248.3,247.6
XS GIS Cut Line= 2
     2030870.588       160998.09     2030203.922      160964.236
#Sta/Elev= 30
       0  1969.5      36 1968.15    85.1 1964.57   134.2 1958.26   176.7  1950.4
  205.811945.646   245.4  1937.1   261.8  1932.3     288 1922.48   310.9 1912.41
   314.1 1911.64   327.2 1910.83   336.1 1908.15   346.8  1907.6   353.4    1908
   359.9 1910.28   395.9 1914.73   422.1 1914.38   458.1 1915.81   471.2 1915.82
     481 1916.77   510.5 1923.91   523.6 1928.75   543.2  1931.6   556.3 1936.31
  587.711944.105   611.9 1949.29   621.7 1950.86   641.4 1953.12   667.5 1955.22
#Mann= 5 ,-1 , 0
       0     .06       0  205.81     .12       0   336.1    .045       0
   353.4     .12       0  587.71     .06       0
Bank Sta=336.1,353.4
XS Rating Curve= 0 ,0
Exp/Cntr=0.3,0.1

Type RM Length L Ch R = 1 ,20218.7 ,384.3,365.8,346.9
XS GIS Cut Line= 3
     2030862.714      160738.393     2030386.213      160732.465
      2030240.38      160828.819
#Sta/Elev= 30
       0 1968.06    39.2 1965.22    84.9 1959.71   107.7 1956.62   156.7 1947.95
  173.071945.521   208.9 1938.93   225.2 1935.25   248.1 1927.67     284 1913.28
     297 1909.22   306.8 1907.86   342.7 1905.59   352.5 1904.76   362.3 1904.84
   368.8 1905.96   378.6  1909.5   381.9  1910.2   391.7 1910.21   411.3 1911.72
   430.8 1912.15   443.9  1913.7   453.7 1916.46   476.5 1925.23     483 1927.21
   499.2 1933.04   576.9 1947.21  604.941950.874     619  1952.4   651.3 1954.99
#Mann= 5 ,-1 , 0
       0     .06       0  173.07     .12       0   342.7    .045       0
   368.8     .12       0  604.94     .06       0
Bank Sta=342.7,368.8
XS Rating Curve= 0 ,0
Exp/Cntr=0.3,0.1

Type RM Length L Ch R = 1 ,19852.8 ,381.6,359.2,336.7
XS GIS Cut Line= 3
     2030736.387       160181.25     2030328.401      160585.764
     2030234.651      160802.778
#Sta/Elev= 30
       0 1949.88    84.9 1931.22     111  1926.5   120.8 1925.62   146.9 1916.86
   156.7 1914.75   195.9  1910.2   205.7 1909.85   212.2 1908.54     235  1909.6
   275.2 1902.38   287.3 1901.76     295 1902.62   300.3 1903.87   313.4 1904.93
     333 1905.03     346 1906.13   434.2 1905.49   447.2 1906.86   470.1 1907.52
   473.3 1908.13   483.1 1912.42   515.8 1922.07   558.2 1938.37   564.7 1939.88
     594 1942.26   626.3 1946.75  687.481951.536   759.1 1954.68   810.9 1955.78
#Mann= 4 ,-1 , 0
       0     .12       0   275.2    .045       0     295     .12       0
  687.48     .06       0
Bank Sta=275.2,295
XS Rating Curve= 0 ,0
Exp/Cntr=0.3,0.1

Type RM Length L Ch R = 1 ,19493.7 ,237.5,236.2,234.6
XS GIS Cut Line= 3
     2030203.401      160117.014     2030300.623      160584.028
     2030220.762      160790.625
#Sta/Elev= 30
       0 1930.26     9.8 1929.65    22.9 1924.69    68.6 1914.93   101.3  1911.4
   117.6 1908.04   153.6 1905.15     196 1904.92   218.9 1901.92     232 1899.05
   251.6  1897.2   258.1 1896.54   272.4  1897.2   287.5 1899.79   294.1 1901.92
  298.681901.648  304.851899.838   372.5  1901.8   385.5 1903.16   395.3 1906.09
     415 1907.58   431.3 1915.46   454.2 1924.38   470.5 1933.18   499.8 1942.03
   512.9 1944.22   529.1  1944.7  588.57 1950.18   649.7 1954.07   698.5 1955.51
#Mann= 6 ,-1 , 0
       0     .12       0   251.6    .045       0   272.4     .12       0
  298.68     .06       0  304.85     .12       0  588.57     .06       0
Bank Sta=251.6,272.4
XS Rating Curve= 0 ,0
Exp/Cntr=0.3,0.1

Type RM Length L Ch R = 1 ,19257.5 ,202.6,207.1,211.3
XS GIS Cut Line= 4
     2030080.137      160104.861     2030004.662      160338.661
     2030106.179      160714.236     2030166.942      160790.625
#Sta/Elev= 30
       0 1948.52    26.2 1944.79    88.4 1938.32    98.3  1935.9   121.2 1934.96
   124.5 1933.94   127.8 1929.14     131 1926.84   157.2 1924.48   183.4 1920.09
   199.8  1915.2     226 1904.64     249 1899.21   281.6 1896.87   314.3 1896.46
     334 1893.16   353.6 1891.54   363.4 1892.95   366.6 1893.44     383 1899.95
   402.6 1896.66   438.6  1895.7   464.7 1896.78   556.3 1897.18     589 1899.55
   598.8 1901.51   608.6 1905.14   628.2 1906.79   706.3 1942.21   732.3 1949.54
#Mann= 3 ,-1 , 0
       0     .12       0     334    .045       0   363.4     .12       0
Bank Sta=334,363.4
XS Rating Curve= 0 ,0
Exp/Cntr=0.3,0.1

Type RM Length L Ch R = 1 ,19050.5 ,136.5,159.7,182.3
XS GIS Cut Line= 3
     2030040.206       160127.43     2029830.137      160427.778
     2029876.323      160940.341
#Sta/Elev= 30
       0 1939.34    13.1 1936.06    26.2 1934.18      36 1929.97    42.5 1928.57
    88.4 1924.76   111.3 1920.76   157.1 1908.52   189.8  1902.7   274.9 1896.29
   304.3 1895.62   320.7 1893.14   369.8 1893.62   382.9 1893.25     396 1890.99
   428.8 1891.22   438.6 1890.31   451.8 1891.46   471.4 1893.02   484.5 1891.68
   615.6 1891.58   645.2 1893.07   704.2 1892.66   736.9 1894.06   789.4 1907.46
   805.8 1912.45   822.2 1914.18   845.1 1923.74   861.5  1927.6   881.2 1934.17
#Mann= 3 ,-1 , 0
       0     .12       0   428.8    .045       0   451.8     .12       0
#XS Ineff= 2 , 0
                          634.82         1903.33
Permanent Ineff=
       F       F
Bank Sta=428.8,451.8
XS Rating Curve= 0 ,0
Exp/Cntr=0.3,0.1

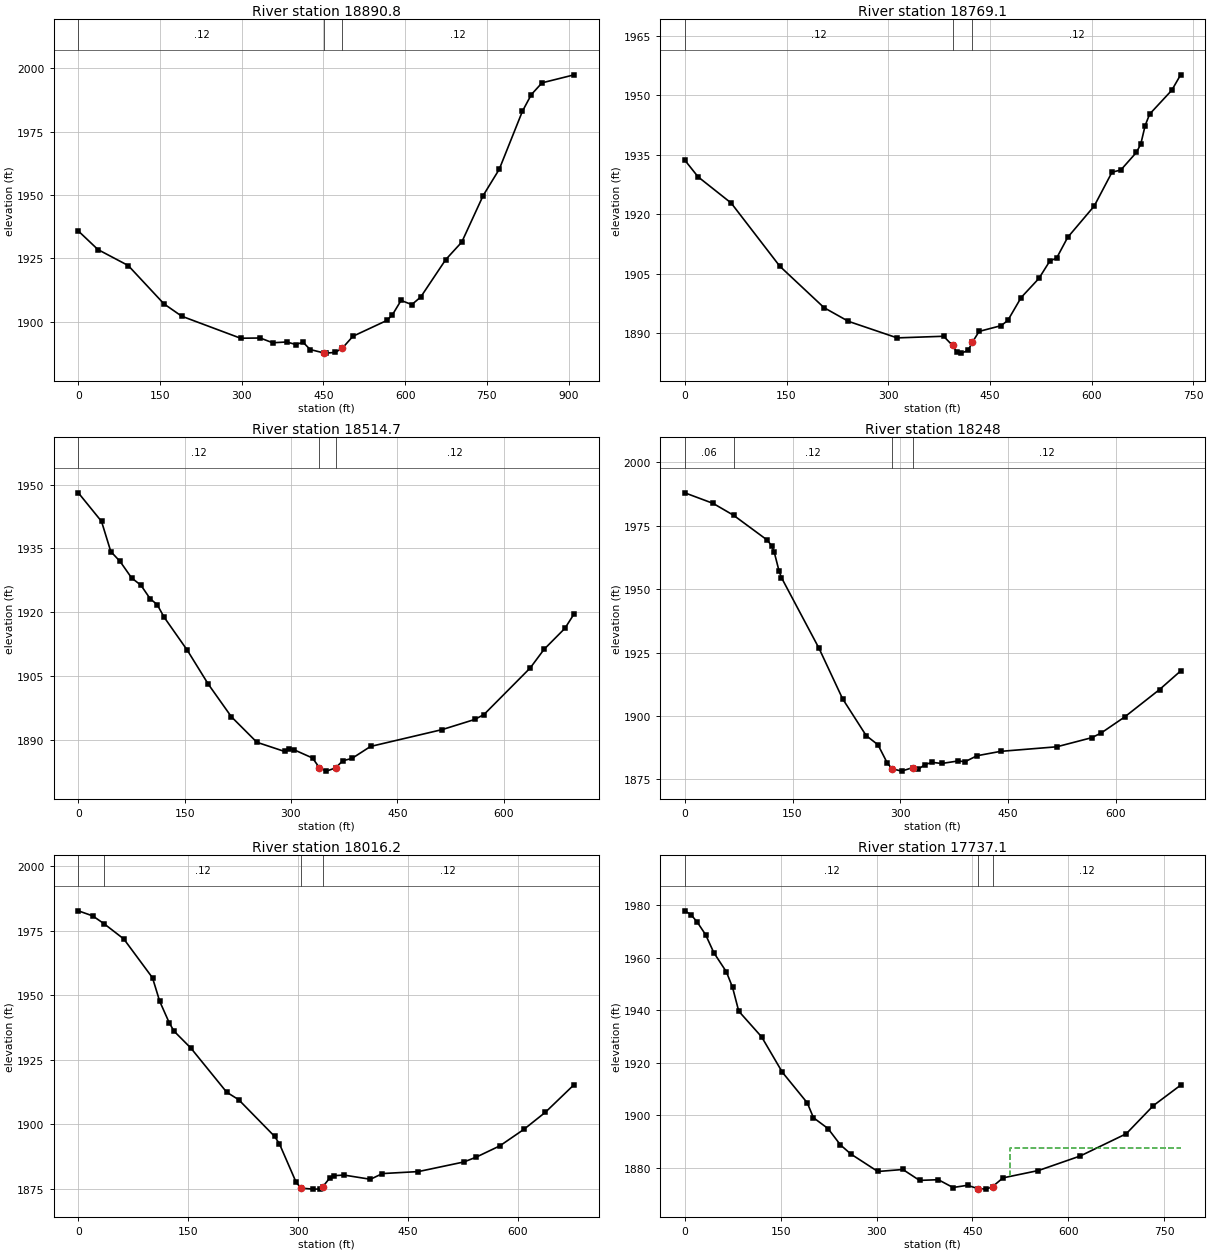
Type RM Length L Ch R = 1 ,18890.8 ,118.7,121.7,124.9
XS GIS Cut Line= 3
     2030020.675      160097.048     2029810.606      160397.396
     2029364.317      160707.671
#Sta/Elev= 30
       0 1935.74      36 1928.41    91.6  1922.1   157.1 1906.99   189.8 1902.11
   297.8 1893.42   333.8 1893.51   356.7 1891.63   382.9 1891.94   399.3 1890.91
   412.4 1891.87   425.5 1888.96   451.7 1887.56   454.9 1887.54   471.3 1887.83
   484.4 1889.44     504 1894.19   566.3 1900.44   576.1 1902.52   592.4 1908.34
   612.1 1906.69   628.5 1909.69   674.3 1924.43   703.8 1931.36   743.1 1949.74
   772.6  1960.1   815.1 1982.98   831.5 1989.58   851.1 1994.21   910.1 1997.37
#Mann= 3 ,-1 , 0
       0     .12       0   451.7    .045       0   484.4     .12       0
Bank Sta=451.7,484.4
XS Rating Curve= 0 ,0
Exp/Cntr=0.3,0.1

Type RM Length L Ch R = 1 ,18769.1 ,255.2,254.4,253.3
XS GIS Cut Line= 3
     2030014.165      160103.125     2029889.165      160231.597
     2029407.719      160501.508
#Sta/Elev= 30
       0  1933.6    19.6 1929.39    68.4 1922.79   140.1 1906.87   205.4 1896.42
   241.3 1892.98   313.2 1888.81   381.7 1889.22   394.8 1886.91   401.3 1885.17
   407.9 1884.97   417.7 1885.65   424.2 1887.75     434 1890.44   466.6  1891.9
   476.4 1893.22     496 1898.98   522.2 1903.79   538.5 1908.23   548.3 1908.91
   564.6 1914.13   603.8 1922.04     630 1930.56     643 1931.12   665.9 1935.53
   672.4 1937.63   678.9 1942.32   685.5  1945.2   718.1  1951.2   731.2  1955.1
#Mann= 3 ,-1 , 0
       0     .12       0   394.8    .045       0   424.2     .12       0
Bank Sta=394.8,424.2
XS Rating Curve= 0 ,0
Exp/Cntr=0.3,0.1

Type RM Length L Ch R = 1 ,18514.7 ,285.7,266.7,247.6
XS GIS Cut Line= 3
     2029976.967      159933.397     2029588.817      160163.889
     2029465.554      160379.167
#Sta/Elev= 30
       0 1948.06    32.7 1941.36    45.8 1934.28    58.9 1931.96    75.2 1928.08
    88.3 1926.38   101.4 1923.19   111.2 1921.84     121 1918.88   153.8  1911.1
   183.2 1903.19   215.9 1895.51   251.9 1889.52   291.1 1887.36   297.7 1887.93
   304.2 1887.77   330.4 1885.83   340.2 1883.52     350 1882.75   363.1 1883.52
   372.9 1885.17     386 1885.73   412.2 1888.54   513.4  1892.5   559.1 1894.87
   572.2 1896.02   637.5 1906.96   657.1 1911.34   686.4 1916.25   699.5 1919.67
#Mann= 3 ,-1 , 0
       0     .12       0   340.2    .045       0   363.1     .12       0
Bank Sta=340.2,363.1
XS Rating Curve= 0 ,0
Exp/Cntr=0.3,0.1

Type RM Length L Ch R = 1 ,18248   ,230.9,231.8,232.8
XS GIS Cut Line= 3
     2029534.998      159643.055      2029444.72      160106.597
     2029375.276      160313.194
#Sta/Elev= 30
       0 1987.96    39.4  1983.8   67.981979.094   114.8 1969.33   121.3 1966.93
   124.6 1964.48   131.2 1957.14   134.5 1954.57   186.9 1926.65   219.7 1906.78
   252.5 1892.28   268.9 1888.68     282  1881.4   288.6 1879.24   301.7 1878.29
   317.4 1879.68   324.7 1878.98   334.5  1880.9   344.4 1881.75   357.5  1881.3
   380.4 1882.29   390.3 1882.02   406.7 1884.35   439.5 1886.08   517.8 1887.88
   566.6 1891.48   579.6 1893.32   612.1 1899.59   660.9 1910.45   690.2 1917.76
#Mann= 4 ,-1 , 0
       0     .06       0   67.98     .12       0   288.6    .045       0
   317.4     .12       0
Bank Sta=288.6,317.4
XS Rating Curve= 0 ,0
Exp/Cntr=0.3,0.1

Type RM Length L Ch R = 1 ,18016.2 ,261.1,279.1,293.3
XS GIS Cut Line= 3
     2029430.831      159646.528     2029272.845      159802.778
     2029167.342      160245.271
#Sta/Elev= 30
       0 1982.66    19.6  1980.7   35.391977.604    62.1 1971.75   101.3 1956.71
   111.1 1947.63   124.2 1939.24   130.7 1936.04   153.6 1929.51   202.6 1912.39
   218.9  1909.5     268 1895.28   274.6  1892.4   297.5 1877.44   304.3 1875.22
   320.4 1874.84   330.2 1874.87   333.5 1875.64   343.3 1879.14   349.8 1880.07
   362.9 1880.28   398.9 1878.66   415.3 1880.87   464.4 1881.64   526.6 1885.37
   542.9 1887.18   575.6  1891.6   608.4 1897.98   637.8 1904.62   677.1 1915.34
#Mann= 4 ,-1 , 0
       0     .06       0   35.39     .12       0   304.3    .045       0
   333.5     .12       0
Bank Sta=304.3,333.5
XS Rating Curve= 0 ,0
Exp/Cntr=0.3,0.1

Type RM Length L Ch R = 1 ,17737.1 ,226.7,238.9,253.6
XS GIS Cut Line= 4
     2029377.012      159637.847     2029112.535      159769.687
     2028911.734      159941.667     2028870.067      160153.472
#Sta/Elev= 30
       0 1977.89     9.7 1976.44    19.5 1973.57    32.5 1968.82    45.5 1961.91
      65 1954.68    74.7 1948.74    84.4 1939.66   120.2 1929.87   152.6  1916.4
   191.6 1904.74   201.3 1899.07   224.1 1894.93   243.6 1888.69   259.8 1885.24
     302 1878.58   341.2 1879.34   367.3 1875.19   396.7 1875.45   419.6 1872.48
   442.4 1873.32   458.7 1872.04   471.8 1871.86   481.6 1872.83   497.9 1876.15
   553.4 1878.95   618.8 1884.49   690.7 1892.95   733.2 1903.69   775.8 1911.46
#Mann= 3 ,-1 , 0
       0     .12       0   458.7    .045       0   481.6     .12       0
#XS Ineff= 2 , 0
                          508.31         1887.57
Permanent Ineff=
       F       F
Bank Sta=458.7,481.6
XS Rating Curve= 0 ,0
Exp/Cntr=0.3,0.1

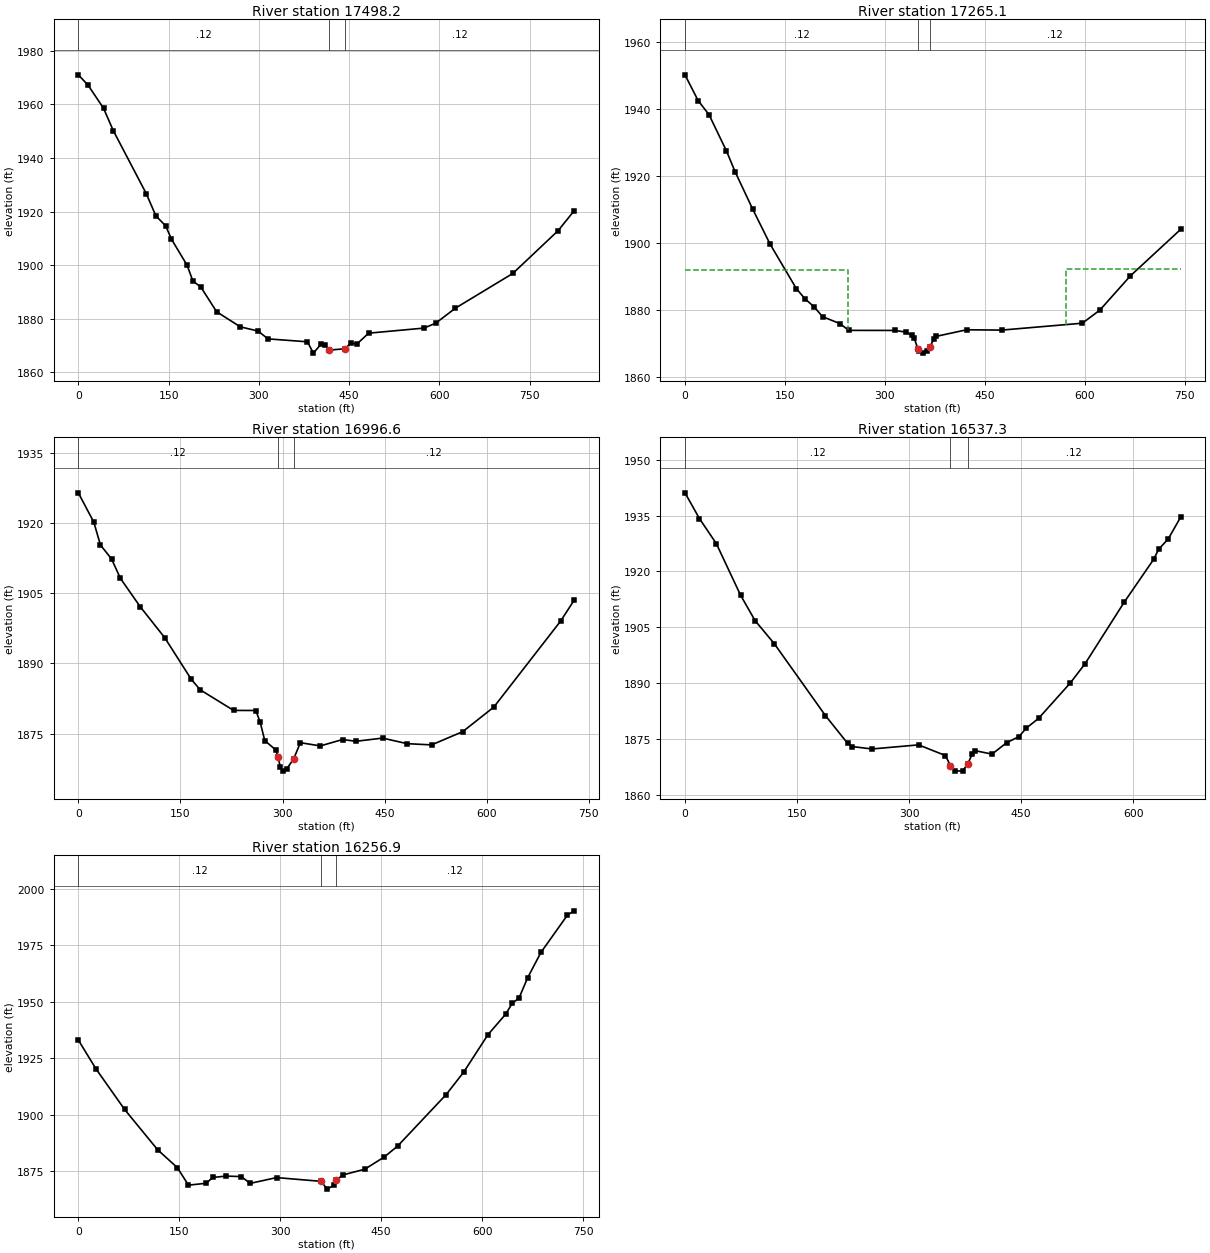
Type RM Length L Ch R = 1 ,17498.2 ,232.3,233.1,230.7
XS GIS Cut Line= 3
     2029359.651      159603.125     2029191.248       159658.68
     2028545.415       159681.25
#Sta/Elev= 30
       0 1971.07    16.1 1967.24    41.9 1958.59      58 1950.28   112.8 1926.77
     129 1918.38   145.1 1914.73   154.8 1909.72   180.6 1900.05   190.4 1894.12
   203.6 1891.86   229.8 1882.64   269.2 1877.01   298.7 1875.44   315.1 1872.52
   380.7 1871.43   390.6  1867.2   403.7 1870.68   410.2 1870.31   416.8 1868.32
     443 1868.83   452.9 1870.94   462.7 1870.56   482.4 1874.65   574.2 1876.54
   593.9 1878.38   626.7    1884   721.9 1896.93   797.3 1912.92   823.6 1920.26
#Mann= 3 ,-1 , 0
       0     .12       0   416.8    .045       0     443     .12       0
Bank Sta=416.8,443
XS Rating Curve= 0 ,0
Exp/Cntr=0.3,0.1

Type RM Length L Ch R = 1 ,17265.1 ,278.8,268.5,257.8
XS GIS Cut Line= 3
     2029344.315      159408.666     2028985.286      159442.064
     2028603.447      159476.508
#Sta/Elev= 30
       0 1950.12    19.7 1942.44    36.1 1938.22    62.3 1927.38    75.4 1921.13
   101.6 1910.06   127.8 1899.58   167.2 1886.32   180.3 1883.24   193.4 1880.99
   206.5 1877.96   232.7 1875.88   245.8 1873.87   314.7 1873.85   331.1 1873.38
   340.9 1872.38   344.2 1871.52  349.55 1868.33   350.7 1867.62   357.3 1867.08
   363.9 1867.69   367.4 1868.84   373.7 1871.36     377 1872.08   422.8 1874.05
   475.3 1873.95   596.5 1876.01   622.7 1879.91   668.6 1890.14     744    1904
#Mann= 3 ,-1 , 0
       0     .12       0  349.55    .045       0   367.4     .12       0
#XS Ineff= 2 , 0
          244.21 1891.79  571.62         1892.26
Permanent Ineff=
       F       F
Bank Sta=349.55,367.4
XS Rating Curve= 0 ,0
Exp/Cntr=0.3,0.1

Type RM Length L Ch R = 1 ,16996.6 ,460.2,459.3,457.5
XS GIS Cut Line= 3
     2029177.359      158988.542     2029080.137      159106.597
     2028590.695      159408.871
#Sta/Elev= 30
       0  1926.4    22.8 1920.12    32.5 1915.26    48.8  1912.3    61.8 1908.15
    91.1 1902.06   126.9 1895.49     166 1886.58   179.1 1884.35   228.1 1879.96
   260.8 1879.94   267.3 1877.38   273.9 1873.53   290.2  1871.5   293.5 1869.95
   296.8 1867.86     300    1867   306.6 1867.55   316.4 1869.62   326.2 1873.07
   355.6 1872.38   388.3 1873.75   407.9 1873.37   447.1 1874.05   483.1 1872.86
     519  1872.6   564.8 1875.43   610.5 1880.68   708.6 1899.03   728.2 1903.43
#Mann= 3 ,-1 , 0
       0     .12       0   293.5    .045       0   316.4     .12       0
Bank Sta=293.5,316.4
XS Rating Curve= 0 ,0
Exp/Cntr=0.3,0.1

Type RM Length L Ch R = 1 ,16537.3 ,276.5,280.3,284.3
XS GIS Cut Line= 3
     2028869.633      158729.427     2028766.769      158832.292
       2028348.8      159138.281
#Sta/Elev= 30
       0 1941.11    19.4 1934.18      42 1927.46    74.4 1913.62    93.8  1906.8
   119.6 1900.58   188.1 1881.26   217.6 1873.86   224.2 1872.96   250.4 1872.32
   312.7 1873.42   348.7 1870.55   355.3 1867.85   361.8 1866.37   371.7 1866.46
   378.2 1868.19   384.8 1871.07   388.1 1871.88     411 1870.94   430.7 1874.02
   447.1 1875.64   456.9 1877.92   473.3 1880.53   515.9 1890.07   535.6 1895.22
   588.1 1911.78   627.4 1923.25     634 1925.91   647.1  1928.8   663.5 1934.58
#Mann= 3 ,-1 , 0
       0     .12       0   355.3    .045       0   378.2     .12       0
Bank Sta=355.3,378.2
XS Rating Curve= 0 ,0
Exp/Cntr=0.3,0.1

Type RM Length L Ch R = 1 ,16256.9 ,243.9,242.1,239.7
XS GIS Cut Line= 2
     2028762.705      158603.054      2028088.41      158898.728
#Sta/Elev= 30
       0    1933    26.2 1920.24    68.7 1902.28   117.8 1884.41   147.2 1876.45
   163.6 1868.73   189.8 1869.56   199.6 1872.12   219.2 1872.74   242.2 1872.53
   255.2 1869.51   294.5 1872.08   360.5 1870.42   369.8 1866.97   379.6 1868.71
   382.9  1870.8   392.7 1873.24   425.4 1875.77   454.8 1881.27   474.5 1886.09
   546.5 1908.87   572.7 1918.88   608.6 1935.41   634.8 1944.44   644.6 1949.29
   654.5  1951.5   667.6 1960.66   687.2 1971.79   726.5 1988.28   736.3 1990.22
#Mann= 3 ,-1 , 0
       0     .12       0   360.5    .045       0   382.9     .12       0
Bank Sta=360.5,382.9
XS Rating Curve= 0 ,0
Exp/Cntr=0.3,0.1