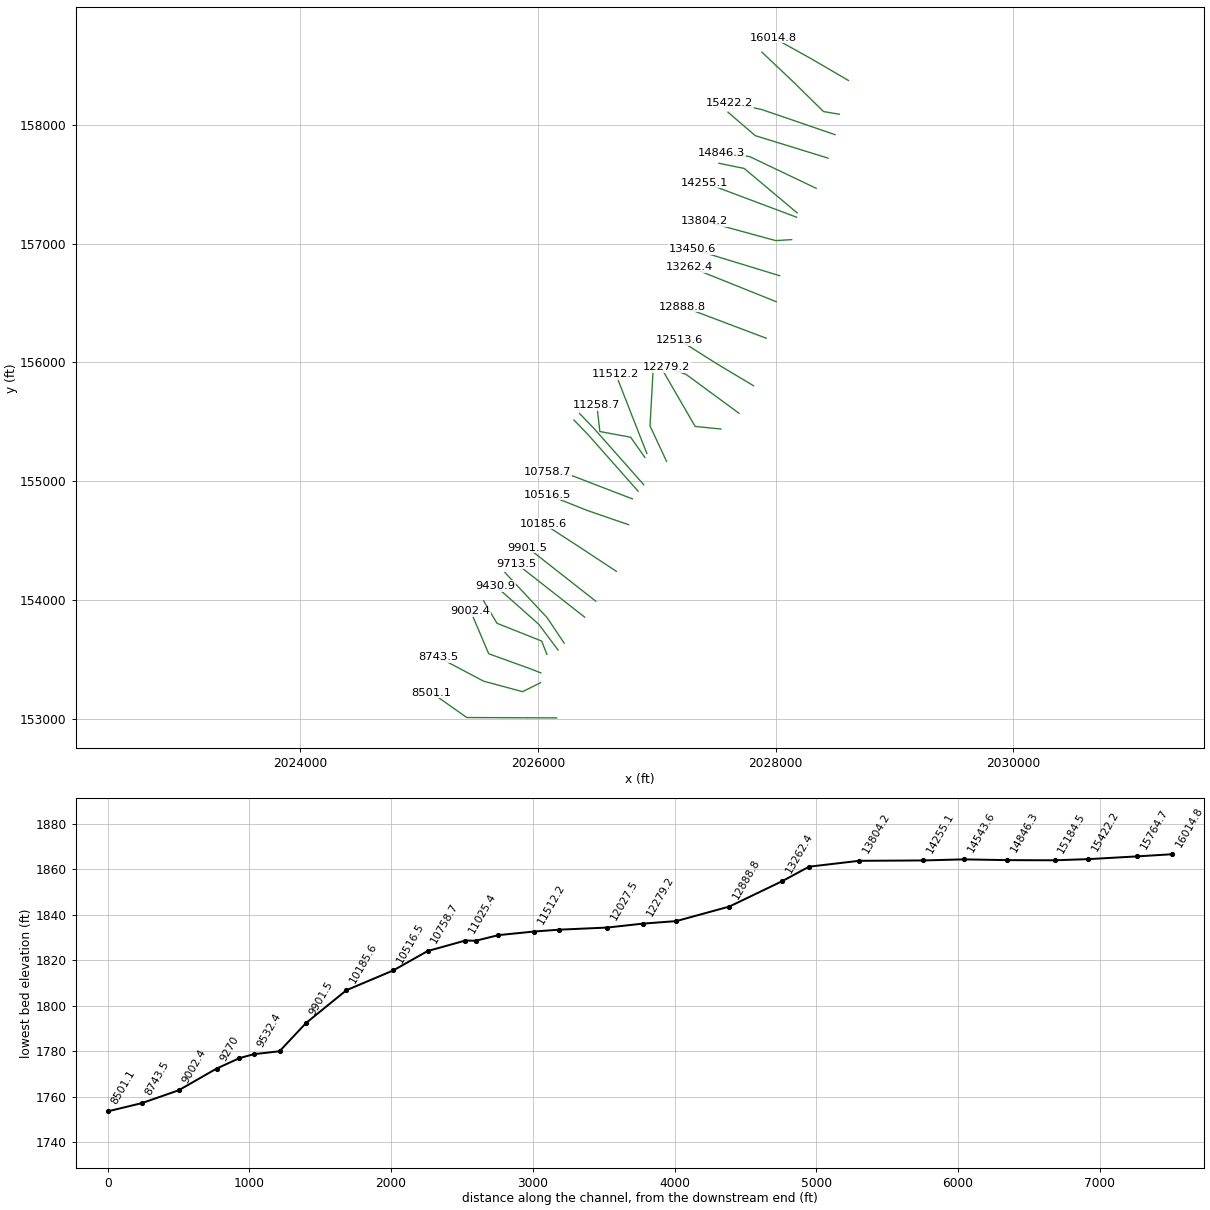
HEC-RAS study BRUSHCK.prj: BRUSHCK

--- BRUSHCK.g01 (geometry) --- (continued)

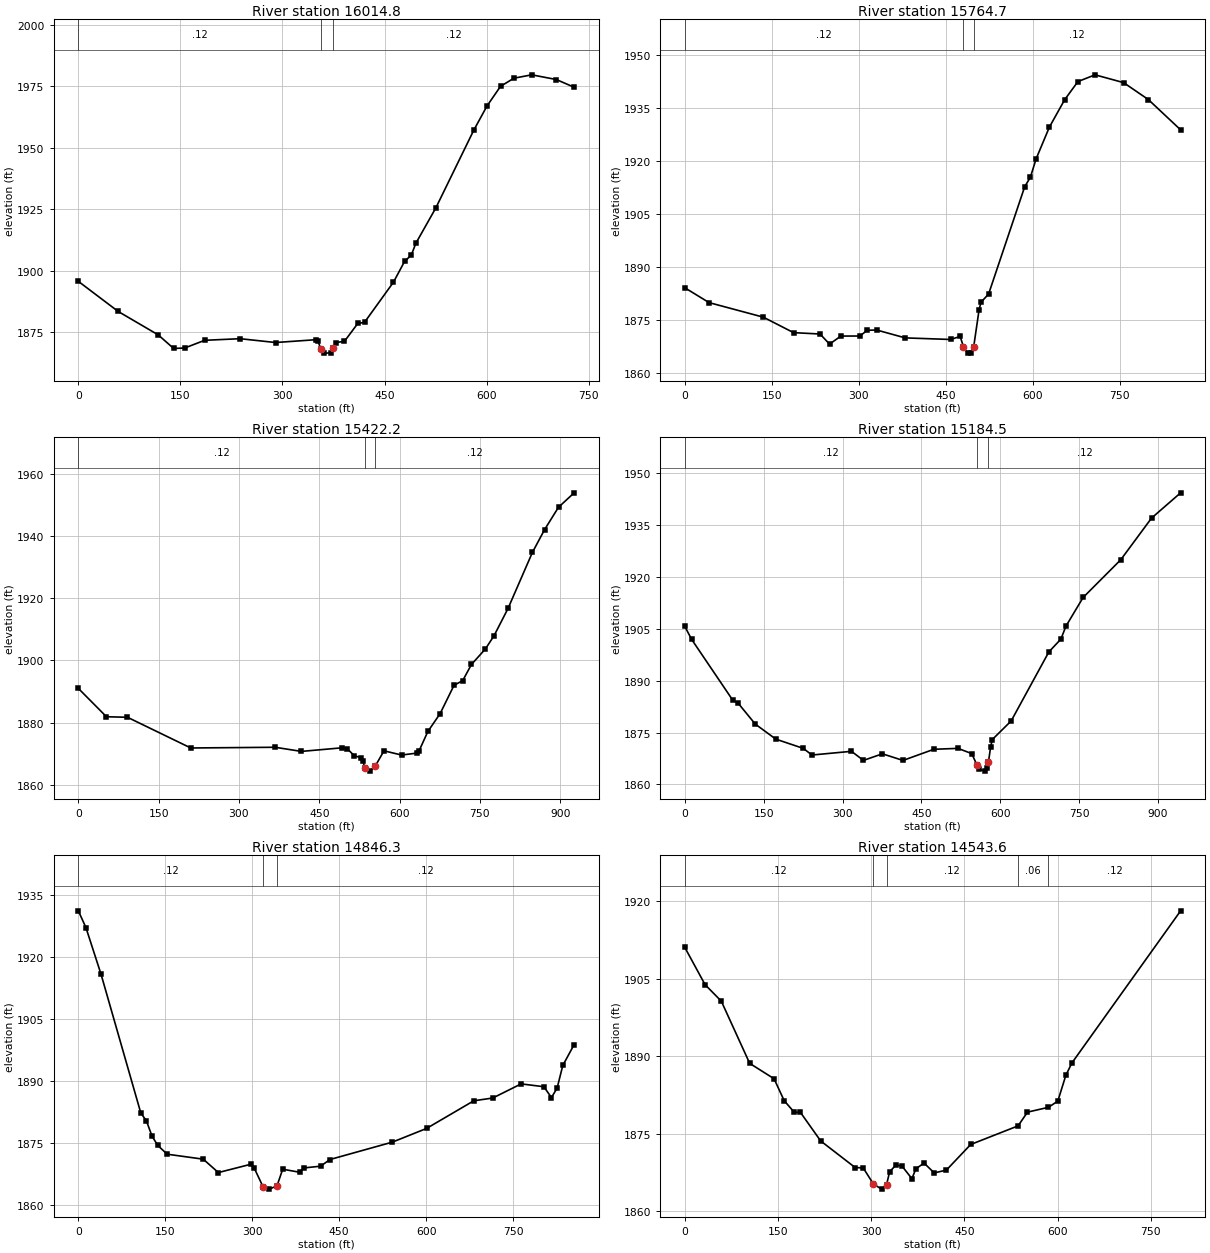
Type RM Length L Ch R = 1 ,16014.8 ,254.8,250.1,243.5
XS GIS Cut Line= 3
     2028612.447      158371.828     2028297.263      158555.591
     2027979.201      158732.296
#Sta/Elev= 30
       0 1895.69    58.6 1883.45   117.3 1873.96   140.1 1868.43   156.4 1868.62
   185.7 1871.74   237.8 1872.39   289.9 1870.84   348.6 1871.97   351.8 1871.62
   356.7 1868.08   361.6 1866.53   371.4 1866.62   374.7 1868.79     378 1870.81
   391.1 1871.31   410.7 1878.58   420.6 1879.04   463.2 1895.37   479.6 1903.85
   489.4 1906.34     496 1911.12   525.5 1925.56   581.2  1957.1   600.8    1967
   620.5  1974.9   640.2 1978.21   666.4 1979.58   702.5 1977.67   728.7 1974.53
#Mann= 3 ,-1 , 0
       0     .12       0   356.7    .045       0   374.7     .12       0
Bank Sta=356.7,374.7
XS Rating Curve= 0 ,0
Exp/Cntr=0.3,0.1

Type RM Length L Ch R = 1 ,15764.7 ,329.6,342.4,351.6
XS GIS Cut Line= 4
       2028536.3        158087.5     2028402.853      158110.323
     2028148.931      158359.711     2027884.573       158610.04
#Sta/Elev= 30
       0  1884.1    41.9 1879.89   135.4 1875.77   187.6 1871.38   233.3 1870.99
   249.7 1868.13   269.3 1870.41   301.9 1870.42     315 1872.06   331.3 1872.11
   380.3 1869.89   458.6 1869.44     475  1870.3  480.79 1867.38     488 1865.57
   494.6 1865.67   498.3 1867.28   507.7 1877.87     511    1880   524.1 1882.32
   586.4 1912.76   596.2 1915.44   606.1 1920.67     629 1929.66   655.3 1937.41
   678.2 1942.57   707.8 1944.48     757 1942.27   799.6 1937.48   855.4 1928.88
#Mann= 3 ,-1 , 0
       0     .12       0  480.79    .045       0   498.3     .12       0
Bank Sta=480.79,498.3
XS Rating Curve= 0 ,0
Exp/Cntr=0.3,0.1

Type RM Length L Ch R = 1 ,15422.2 ,237.3,237.8,237.7
XS GIS Cut Line= 3
     2028499.408      157916.059     2027878.748      158128.733
     2027613.991      158180.816
#Sta/Elev= 30
       0    1891    52.5 1881.88    91.8  1881.7     210 1871.82   367.4 1872.05
   416.6 1870.72   492.1 1871.87   501.9 1871.64     515 1869.37   528.2 1868.64
   531.4 1867.71   534.7 1865.49   544.6 1864.37   554.4 1865.97   570.8 1870.91
   603.6 1869.55   633.1 1870.19   636.4 1870.93   652.8 1877.15   675.6 1882.87
   701.6    1892   717.8  1893.5   734.1  1898.7   760.1 1903.68   776.4 1907.98
   802.4 1916.72   847.9 1934.75   870.6 1942.08   896.7 1949.31   925.9 1953.95
#Mann= 3 ,-1 , 0
       0     .12       0   534.7    .045       0   554.4     .12       0
Bank Sta=534.7,554.4
XS Rating Curve= 0 ,0
Exp/Cntr=0.3,0.1

Type RM Length L Ch R = 1 ,15184.5 ,340.4,338.2,341
XS GIS Cut Line= 3
     2028440.814      157718.576     2027828.835      157907.378
     2027599.389      158104.799
#Sta/Elev= 30
       0 1905.63    13.1 1901.87    91.5 1884.27   101.3  1883.5     134 1877.44
   173.2 1873.09   225.5 1870.42   241.8 1868.51     317 1869.58   339.8 1866.96
   375.8 1868.86     415 1866.95   473.8 1870.17   519.5 1870.43   545.7 1868.93
   555.5  1865.7   558.8 1864.43   571.8 1863.86   575.1 1864.63   577.6  1866.5
   581.6 1870.78   584.9 1872.98   620.8 1878.36   692.5 1898.29   715.3 1901.97
   725.1 1905.75   757.6    1914   829.2 1924.89   887.8 1936.93   943.1 1944.22
#Mann= 3 ,-1 , 0
       0     .12       0   555.5    .045       0   577.6     .12       0
Bank Sta=555.5,577.6
XS Rating Curve= 0 ,0
Exp/Cntr=0.3,0.1

Type RM Length L Ch R = 1 ,14846.3 ,304.5,302.7,178
XS GIS Cut Line= 3
     2028340.988       157464.67     2027781.092      157731.597
     2027547.629      157759.864
#Sta/Elev= 30
       0 1931.28    13.1 1927.22    39.2 1915.92   107.7 1882.39   117.5 1880.42
   127.3 1876.71   137.1 1874.49   153.4 1872.38   215.5 1871.18   241.6 1867.94
   297.1 1869.93   303.6 1868.98   318.9 1864.44   329.7 1863.93   342.8 1864.75
   352.6 1868.75     382 1868.01   388.5 1869.05   417.9 1869.48   434.2  1871.1
   541.9 1875.31   600.7 1878.61   682.3 1885.31     715 1885.98     764  1889.4
   803.2 1888.71   816.2 1886.09     826 1888.36   835.8 1893.85   855.4 1898.92
#Mann= 3 ,-1 , 0
       0     .12       0   318.9    .045       0   342.8     .12       0
Bank Sta=318.9,342.8
XS Rating Curve= 0 ,0
Exp/Cntr=0.3,0.1

Type RM Length L Ch R = 1 ,14543.6 ,289.7,288.5,352.8
XS GIS Cut Line= 3
     2028180.397      157258.507     2027735.519      157631.771
     2027522.845      157675.173
#Sta/Elev= 30
       0  1911.1    32.6 1903.88    58.7 1900.69   104.4 1888.63   143.6 1885.65
   159.9  1881.4   176.2 1879.14     186 1879.14   218.6  1873.6     274 1868.45
   287.1 1868.36   303.4 1865.27   316.5 1864.26   324.7 1865.15   329.5 1867.61
   339.3 1868.88   349.1 1868.78   365.4 1866.29   371.9 1868.21     385 1869.31
   401.3  1867.4   420.9 1867.95     460 1872.91  536.241876.519   551.4 1879.18
  585.161880.116   600.2 1881.32   613.1 1886.31   622.8  1888.7   797.8 1918.19
#Mann= 5 ,-1 , 0
       0     .12       0   303.4    .045       0   324.7     .12       0
  536.24     .06       0  585.16     .12       0
Bank Sta=303.4,324.7
XS Rating Curve= 0 ,0
Exp/Cntr=0.3,0.1

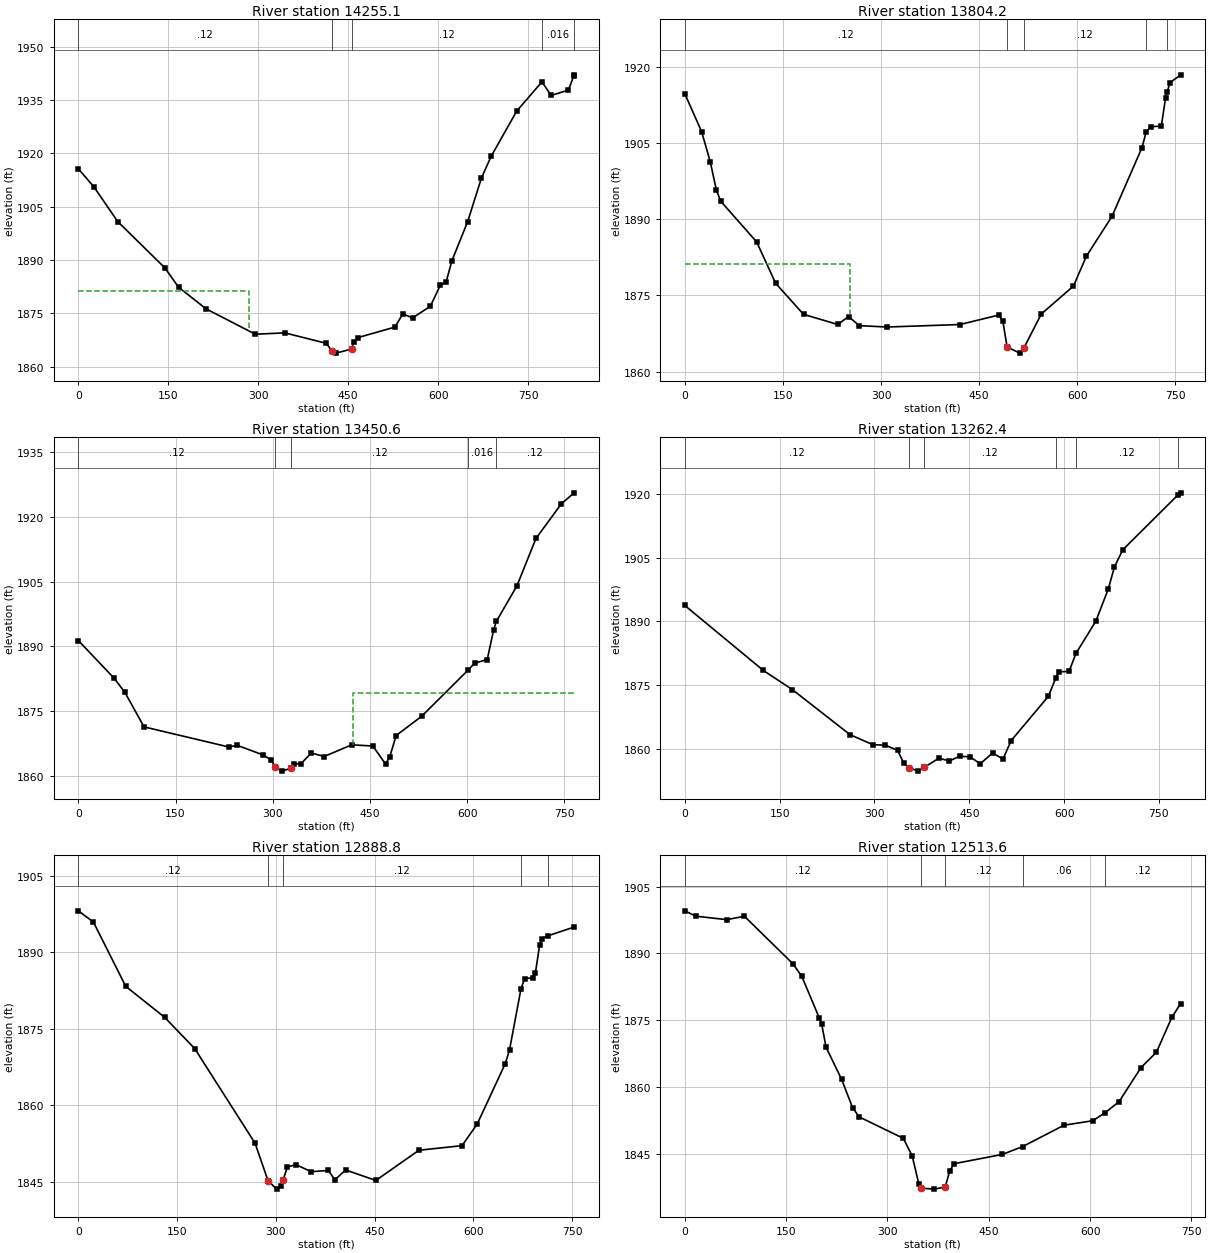
Type RM Length L Ch R = 1 ,14255.1 ,441.9,450.9,449.2
XS GIS Cut Line= 3
     2028176.057      157221.614     2027494.633      157477.691
     2027401.317      157510.243
#Sta/Elev= 30
       0 1915.66    26.2 1910.52    65.6 1900.82   144.3 1887.78   167.2 1882.32
   213.1 1876.24   295.1 1869.11   344.3 1869.49   413.2 1866.56     423 1864.46
   429.6 1863.79   455.8 1864.95   459.1 1866.83   465.6 1868.13   527.9 1871.12
     541 1874.83   557.4  1873.7     587 1876.98   603.4 1882.83   613.2 1883.75
     623 1889.82   649.2 1900.78   672.2 1913.08   688.6 1919.24   731.1 1931.92
  773.021940.112   788.5  1936.3   817.2  1937.8  826.111941.755   826.8  1942.1
#Mann= 5 ,-1 , 0
       0     .12       0     423    .045       0   455.8     .12       0
  773.02    .016       0  826.11     .12       0
#XS Ineff= 2 , 0
          284.91 1881.31
Permanent Ineff=
       F       F
Bank Sta=423,455.8
XS Rating Curve= 0 ,0
Exp/Cntr=0.3,0.1

Type RM Length L Ch R = 1 ,13804.2 ,354.2,353.7,360.3
XS GIS Cut Line= 3
     2028134.824      157032.812     2027999.394      157024.912
     2027399.147      157189.062
#Sta/Elev= 30
       0 1914.81    25.8 1907.28    38.8 1901.42    48.4 1895.74    54.9  1893.6
   109.8 1885.57   138.9  1877.4   181.5 1871.28   233.9 1869.28   250.3 1870.85
   266.7 1869.05   309.2 1868.78   420.6 1869.27   479.6 1871.13   486.1 1870.01
   492.7 1864.83   512.3 1863.63   518.6 1864.71   545.1 1871.36   594.2 1876.86
   613.8 1882.71   653.1 1890.62     699 1904.18  705.241907.218   712.1 1908.29
   728.5  1908.4     735 1914.02  737.611915.222   741.6 1916.95     758 1918.52
#Mann= 5 ,-1 , 0
       0     .12       0   492.7    .045       0   518.6     .12       0
  705.24    .016       0  737.61     .12       0
#XS Ineff= 2 , 0
           252.8 1881.29
Permanent Ineff=
       F       F
Bank Sta=492.7,518.6
XS Rating Curve= 0 ,0
Exp/Cntr=0.3,0.1

Type RM Length L Ch R = 1 ,13450.6 ,189.9,188.2,187.5
XS GIS Cut Line= 2
     2028033.999      156729.447     2027302.274      156952.863
#Sta/Elev= 30
       0 1891.33    55.6 1882.53    71.9  1879.3   101.4 1871.31   232.1 1866.65
   245.2 1867.03   284.4 1864.84   297.5 1863.67   304.1 1861.98   313.9 1861.05
   327.7  1861.7   333.5 1862.75   343.3 1862.74   359.6 1865.26   379.3 1864.44
   421.8 1867.15   454.5 1866.87   474.1 1862.69   480.6 1864.38   490.4 1869.31
   529.7 1873.76  601.961884.553   611.4 1886.08     631 1886.93   640.8 1893.76
  645.031895.776   676.8 1904.02   706.2 1915.01   745.4 1923.04   765.1 1925.58
#Mann= 5 ,-1 , 0
       0     .12       0   304.1    .045       0   327.7     .12       0
  601.96    .016       0  645.03     .12       0
#XS Ineff= 2 , 0
                          424.19         1879.17
Permanent Ineff=
       F       F
Bank Sta=304.1,327.7
XS Rating Curve= 0 ,0
Exp/Cntr=0.3,0.1

Type RM Length L Ch R = 1 ,13262.4 ,373.6,373.6,372.7
XS GIS Cut Line= 2
     2028005.519      156510.716     2027277.619      156802.778
#Sta/Elev= 30
       0 1893.73   124.2 1878.43   169.9 1873.94   261.4  1863.3   297.4 1860.95
     317 1860.83   336.6 1859.62   346.4 1856.59   354.4 1855.55   369.3 1854.72
   379.1 1855.63     402 1857.78   418.3 1857.11   434.6 1858.21     451  1858.1
   467.3 1856.45   486.9    1859   503.3 1857.56   516.3 1861.92   575.2 1872.35
  587.021876.723   591.5 1878.09   607.8  1878.2  618.731882.436   650.3 1890.06
   669.9 1897.63   679.7 1902.84   692.8 1906.83  779.731919.707   784.3 1920.25
#Mann= 6 ,-1 , 0
       0     .12       0   354.4    .045       0   379.1     .12       0
  587.02    .016       0  618.73     .12       0  779.73     .06       0
Bank Sta=354.4,379.1
XS Rating Curve= 0 ,0
Exp/Cntr=0.3,0.1

Type RM Length L Ch R = 1 ,12888.8 ,378.2,375.2,370.9
XS GIS Cut Line= 2
     2027920.531      156203.784      2027216.02      156469.894
#Sta/Elev= 30
       0 1898.12    22.9 1895.92      72 1883.31     131 1877.24   176.8  1871.1
   268.5 1852.52   288.1 1845.21   301.2 1843.54   307.8 1844.12   311.1 1845.42
   317.6 1847.89   330.7 1848.34   353.6 1846.96   379.8  1847.2   389.6 1845.36
     406  1847.3   451.9 1845.24   517.3 1851.16   582.8 1852.07   605.8  1856.3
   648.3 1868.11   654.9 1870.82  672.241882.766   677.8 1884.81   690.9    1885
   694.2 1885.91   700.7 1891.44     704 1892.66  713.12 1893.21   753.1 1894.94
#Mann= 5 ,-1 , 0
       0     .12       0   288.1    .045       0   311.1     .12       0
  672.24    .016       0  713.12     .12       0
Bank Sta=288.1,311.1
XS Rating Curve= 0 ,0
Exp/Cntr=0.3,0.1

Type RM Length L Ch R = 1 ,12513.6 ,234.8,234.5,234.3
XS GIS Cut Line= 3
     2027814.372       155803.75     2027503.176       155990.06
      2027189.39      156188.636
#Sta/Elev= 30
       0 1899.56    16.3 1898.36    62.1 1897.58    88.2 1898.34   160.1 1887.68
   173.2 1884.86   199.3 1875.45   202.6 1874.18   209.1 1868.96     232 1861.81
   248.3 1855.42   258.1 1853.34   323.5 1848.52   336.6 1844.59   346.4 1838.31
   349.6 1837.35   369.2 1837.13   385.5 1837.61     392 1841.13   398.5 1842.83
   470.2 1844.92  500.241846.683   561.4 1851.47   603.8 1852.47  621.921854.239
   642.8 1856.73   675.4 1864.41   698.2 1867.84     721 1875.67     734 1878.74
#Mann= 5 ,-1 , 0
       0     .12       0   349.6    .045       0   385.5     .12       0
  500.24     .06       0  621.92     .12       0
Bank Sta=349.6,385.5
XS Rating Curve= 0 ,0
Exp/Cntr=0.3,0.1

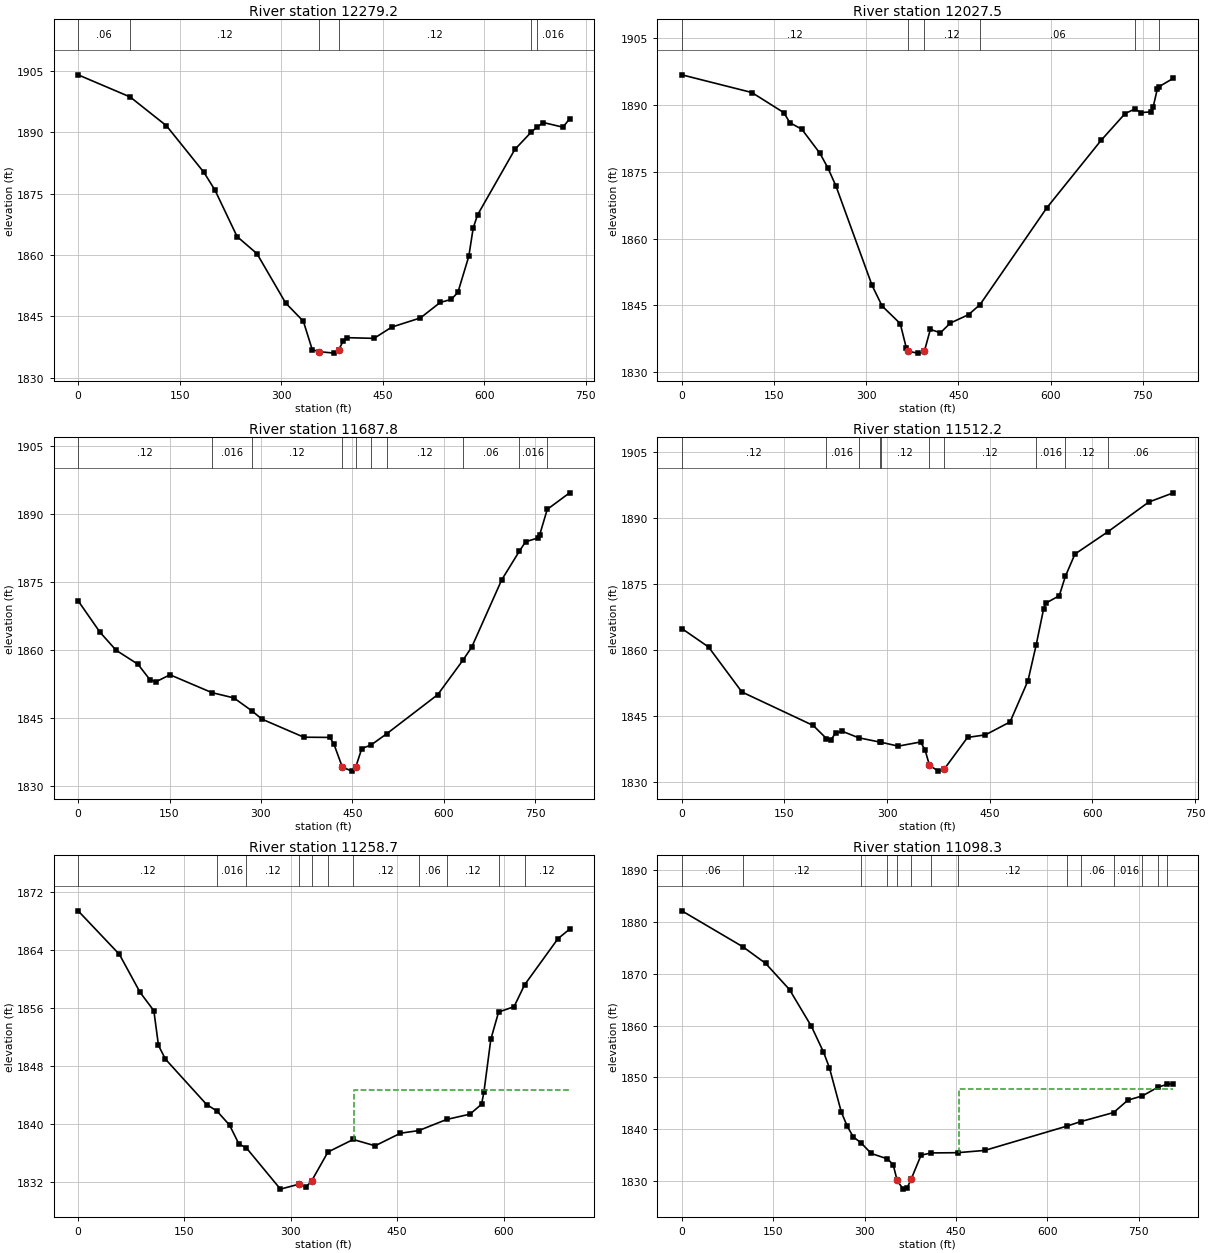
Type RM Length L Ch R = 1 ,12279.2 ,263.8,251.6,238.7
XS GIS Cut Line= 3
     2027692.116      155572.309     2027247.813       155898.61
     2027084.477      155960.764
#Sta/Elev= 30
       0 1904.09   76.831898.679   130.5 1891.63   185.9 1880.22   202.2 1875.88
   234.8 1864.54   264.2 1860.35   306.6 1848.28   332.7 1843.82   345.8  1836.9
   355.5 1836.39   378.4 1836.03   384.9 1836.85   391.4 1838.94   397.9 1839.81
   437.1 1839.64   463.2 1842.39   505.6 1844.64   534.9 1848.43   551.2 1849.17
     561  1850.9   577.1 1859.72   583.6 1866.66   590.1 1869.86   645.1 1885.84
  669.571890.128   678.21891.346   687.2 1892.42   716.3 1891.28     726 1893.37
#Mann= 6 ,-1 , 0
       0     .06       0   76.83     .12       0   355.5    .045       0
   384.9     .12       0  669.57     .06       0   678.2    .016       0
Bank Sta=355.5,384.9
XS Rating Curve= 0 ,0
Exp/Cntr=0.3,0.1

Type RM Length L Ch R = 1 ,12027.5 ,351,339.7,329.6
XS GIS Cut Line= 3
     2027540.206       155439.93     2027323.192      155461.632
     2027031.683      155965.008
#Sta/Elev= 30
       0 1896.76   113.9 1892.79     166 1888.27   175.8 1886.02   195.3 1884.54
   224.6 1879.17   237.7 1875.86   250.8  1871.8   309.6 1849.49   325.9 1844.87
   355.4 1840.93   365.2  1835.5   368.4 1834.67   384.8  1834.3   394.6 1834.68
   404.4 1839.63   420.7 1838.86     437 1841.05   466.5 1842.93  485.31  1845.2
   593.9 1866.91   682.1 1882.03   721.4 1888.08  737.031889.079   747.5 1888.29
   763.8 1888.45   767.1 1889.61   773.6  1893.5  776.861894.132   799.8 1895.98
#Mann= 6 ,-1 , 0
       0     .12       0   368.4    .045       0   394.6     .12       0
  485.31     .06       0  737.03    .016       0  776.86     .06       0
Bank Sta=368.4,394.6
XS Rating Curve= 0 ,0
Exp/Cntr=0.3,0.1

Type RM Length L Ch R = 1 ,11687.8 ,165.9,175.6,182.9
XS GIS Cut Line= 3
     2027082.064      155169.006     2026943.418      155465.972
     2026969.836      155944.086
#Sta/Elev= 30
       0 1870.86      36 1863.92    62.3 1859.98    98.3 1856.88     118 1853.46
   127.8 1853.04   150.8 1854.57  219.581850.641   255.6 1849.48  286.061846.542
   301.5 1844.82   370.4 1840.83     413 1840.78   419.6 1839.39   433.5 1834.27
   449.1 1833.36   455.6 1834.26   465.5 1838.33  480.721839.116  506.231841.564
   590.1 1850.19   631.61857.802   645.9 1860.65   695.1 1875.46  724.081881.777
   734.4 1883.86   754.1 1884.67   757.4 1885.34  769.861890.986   806.6 1894.63
#Mann= 10 ,-1 , 0
       0     .12       0  219.58    .016       0  286.06     .12       0
   433.5    .045       0   455.6     .12       0  480.72     .06       0
  506.23     .12       0   631.6     .06       0  724.08    .016       0
  769.86     .06       0
Bank Sta=433.5,455.6
XS Rating Curve= 0 ,0
Exp/Cntr=0.3,0.1

Type RM Length L Ch R = 1 ,11512.2 ,232.4,253.5,274.5
XS GIS Cut Line= 3
     2026917.376      155233.767     2026850.102      155403.038
     2026655.194      155902.411
#Sta/Elev= 30
       0 1864.96      39 1860.77    87.8 1850.54     192 1842.93  211.311839.968
   218.1 1839.67   224.6 1841.24   234.4 1841.62  258.161840.149  289.061839.168
  290.691839.135   316.2 1838.24   348.8 1839.18   355.4 1837.38   361.9 1833.85
     375 1832.56   383.7 1833.08   417.5 1840.22   443.6  1840.8   479.6 1843.73
   505.8  1853.1  517.641861.134   528.6  1869.4   531.9 1870.73   551.5 1872.42
  560.43 1876.82   574.4 1881.88  622.881886.989   682.3  1893.7   718.2  1895.8
#Mann= 10 ,-1 , 0
       0     .12       0  211.31    .016       0  258.16     .12       0
  289.06     .06       0  290.69     .12       0   361.9    .045       0
   383.7     .12       0  517.64    .016       0  560.43     .12       0
  622.88     .06       0
Bank Sta=361.9,383.7
XS Rating Curve= 0 ,0
Exp/Cntr=0.3,0.1

Type RM Length L Ch R = 1 ,11258.7 ,172.7,160.4,147.1
XS GIS Cut Line= 4
     2026900.015      155201.215     2026780.658      155370.486
     2026521.313      155418.849     2026496.369      155639.583
#Sta/Elev= 30
       0 1869.39    58.2 1863.38    87.4 1858.13   106.8  1855.6   113.3 1850.82
     123 1848.93   181.2 1842.65  195.741841.757   213.6  1839.8   226.7 1837.21
  237.311836.655   285.3 1830.97   311.3 1831.65   321.1 1831.22   329.4 1832.12
   352.31836.093  387.911837.824   418.8 1836.95   454.6 1838.69  480.331839.051
  519.611840.586   552.6 1841.32   568.9 1842.69   572.2 1844.33     582 1851.66
  592.961855.418   614.7 1856.15  629.671859.182   676.7 1865.55   693.1 1866.86
#Mann= 11 ,-1 , 0
       0     .12       0  195.74    .016       0  237.31     .12       0
   311.3    .045       0   329.4     .12       0   352.3    .016       0
  387.91     .12       0  480.33     .06       0  519.61     .12       0
  592.96    .016       0  629.67     .12       0
#XS Ineff= 2 , 0
                          389.37         1844.67
Permanent Ineff=
       F       F
Bank Sta=311.3,329.4
XS Rating Curve= 0 ,0
Exp/Cntr=0.3,0.1

Type RM Length L Ch R = 1 ,11098.3 ,73,72.9,73
XS GIS Cut Line= 3
     2026890.964      154971.133     2026470.328      155446.441
      2026350.97      155570.139
#Sta/Elev= 30
       0 1882.09   100.11875.169   137.4 1871.98   176.7 1866.92   212.7 1859.83
   232.3 1854.94   242.1 1851.91   261.7 1843.34   271.6 1840.56   281.4 1838.55
  294.54 1837.35   310.8 1835.36  337.431834.317   346.8 1833.22   353.3 1830.18
   363.2 1828.49   369.7 1828.73   376.2 1830.37   392.6 1835.03  409.261835.459
  452.661835.507   497.3 1835.95  632.86 1840.66  654.251841.482  708.621843.243
     732 1845.63  755.93 1846.45  781.881848.159  796.98 1848.67   806.6  1848.8
#Mann= 14 ,-1 , 0
       0     .06       0   100.1     .12       0  294.54    .016       0
  337.43     .12       0   353.3    .045       0   376.2     .12       0
  409.26    .016       0  452.66     .12       0  632.86     .08       0
  654.25     .06       0  708.62    .016       0  755.93     .12       0
  781.88     .08       0  796.98     .06       0
#XS Ineff= 2 , 0
                          454.49         1847.83
Permanent Ineff=
       F       F
Bank Sta=353.3,376.2
XS Rating Curve= 0 ,0
Exp/Cntr=0.3,0.1

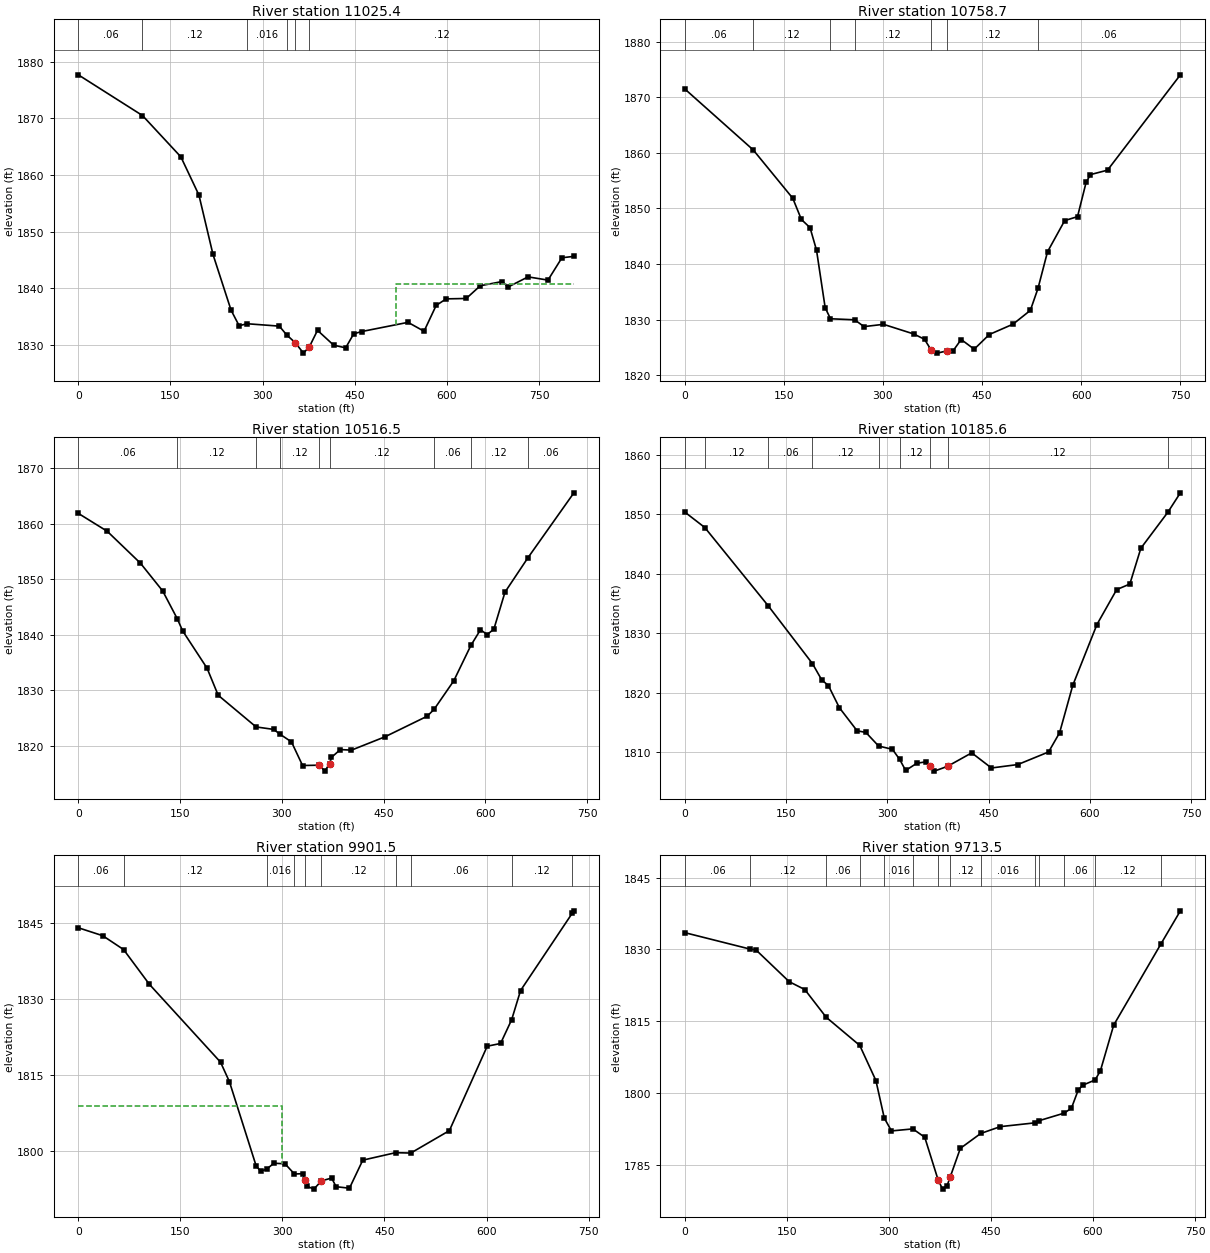
Type RM Length L Ch R = 1 ,11025.4 ,256,266.7,277.2
XS GIS Cut Line= 3
      2026843.22       154916.88     2026422.585      155392.187
     2026303.227      155515.885
#Sta/Elev= 30
       0 1877.68  104.451870.497   166.9 1863.21   196.3 1856.47   219.2 1845.99
   248.6 1836.17   261.7 1833.43  274.841833.773   327.2 1833.35  339.251831.784
   353.1 1830.43   366.4 1828.59   376.2 1829.74   389.3 1832.61   415.5    1830
   435.1 1829.52   448.2 1831.99   461.3  1832.4   536.6 1834.02   562.7 1832.45
   582.4    1837   598.7 1838.16   631.4 1838.23   654.2 1840.47   689.8 1841.22
   699.6 1840.26     732 1842.04   764.4 1841.47   787.1 1845.41   806.6 1845.66
#Mann= 6 ,-1 , 0
       0     .06       0  104.45     .12       0  274.84    .016       0
  339.25     .12       0   353.1    .045       0   376.2     .12       0
#XS Ineff= 2 , 0
                          517.24         1840.86
Permanent Ineff=
       F       F
Bank Sta=353.1,376.2
XS Rating Curve= 0 ,0
Exp/Cntr=0.3,0.1

Type RM Length L Ch R = 1 ,10758.7 ,240.9,242.2,240.9
XS GIS Cut Line= 3
     2026794.859      154852.262     2026294.547      155044.965
     2026083.219      155079.186
#Sta/Elev= 30
       0 1871.49  103.61 1860.52   163.5 1851.82   176.5 1848.01   189.6 1846.54
   199.4  1842.5   212.5 1832.15  220.531830.152  257.181829.962   271.3 1828.74
   300.8 1829.15   346.5 1827.42   362.9 1826.46   372.7 1824.57   382.3 1823.97
   397.3 1824.39   405.4 1824.27   418.4 1826.42   438.1 1824.68     461 1827.32
   496.9 1829.18   523.1 1831.66  534.671835.614   549.1  1842.2   575.1 1847.81
   594.5 1848.52   607.5 1854.68     614 1856.08   639.9 1856.88   750.2 1874.03
#Mann= 7 ,-1 , 0
       0     .06       0  103.61     .12       0  220.53    .016       0
  257.18     .12       0   372.7    .045       0   397.3     .12       0
  534.67     .06       0
Bank Sta=372.7,397.3
XS Rating Curve= 0 ,0
Exp/Cntr=0.3,0.1

Type RM Length L Ch R = 1 ,10516.5 ,335.2,330.9,325.8
XS GIS Cut Line= 3
     2026763.244      154634.934     2026416.665      154754.406
     2026078.337       154888.81
#Sta/Elev= 30
       0 1861.86    42.6 1858.64    91.6 1852.89   124.4 1847.89  145.831842.903
   153.8 1840.71   189.8 1833.99   206.2 1829.12  262.051823.417     288 1822.97
  297.481822.092   314.2 1820.73   330.6 1816.47   355.5 1816.53   363.3 1815.46
   370.5  1816.8   373.2 1817.94   386.3 1819.34   402.7 1819.24   451.9 1821.63
   514.2 1825.34  524.471826.577   553.5 1831.72  578.76  1838.1   592.9 1840.91
   602.7 1840.05   612.6 1841.01     629 1847.68  662.54 1853.82   730.6 1865.56
#Mann= 9 ,-1 , 0
       0     .06       0  145.83     .12       0  262.05    .016       0
  297.48     .12       0   355.5    .045       0   370.5     .12       0
  524.47     .06       0  578.76     .12       0  662.54     .06       0
Bank Sta=355.5,370.5
XS Rating Curve= 0 ,0
Exp/Cntr=0.3,0.1

Type RM Length L Ch R = 1 ,10185.6 ,285.7,284.1,281.4
XS GIS Cut Line= 3
     2026660.176      154242.885     2026357.094      154442.617
     2026046.108      154644.488
#Sta/Elev= 30
       0 1850.41    29.61847.806  123.811834.568  189.041824.864   202.7 1822.13
   212.6 1821.17   228.9 1817.43   255.1 1813.55   268.1 1813.27  286.971810.977
   307.4 1810.43  318.171808.713     327 1806.86   343.4 1808.07   356.4 1808.31
     363 1807.57   369.5 1806.75     389 1807.56   424.8 1809.83     454 1807.28
   493.1 1807.86   538.6 1809.98   554.9 1813.22   574.4 1821.21   610.2 1831.46
   639.4 1837.34   658.9 1838.28   675.2 1844.31  715.251850.392   733.7 1853.65
#Mann= 9 ,-1 , 0
       0     .06       0    29.6     .12       0  123.81     .06       0
  189.04     .12       0  286.97    .016       0  318.17     .12       0
     363    .045       0     389     .12       0  715.25     .06       0
Bank Sta=363,389
XS Rating Curve= 0 ,0
Exp/Cntr=0.3,0.1

Type RM Length L Ch R = 1 ,9901.5  ,182.6,188,188
XS GIS Cut Line= 2
     2026486.731      153991.995     2025913.759      154441.653
#Sta/Elev= 30
       0 1844.07    35.9  1842.5   66.53 1839.76   104.5 1832.88     209  1817.5
   222.1 1813.63   261.3 1797.01   267.8 1795.94  276.611796.314   287.4 1797.51
   303.8  1797.4  317.641795.383   329.9 1795.44   333.2  1794.2   336.4 1792.95
   346.2 1792.39   357.3 1794.02   372.3 1794.58   378.9 1792.87   398.5 1792.57
   418.1 1798.12  466.321799.596  488.651799.523   545.4 1803.96     601 1820.65
   620.6 1821.19  636.931825.896     650 1831.66     7261846.955   728.4 1847.42
#Mann= 10 ,-1 , 0
       0     .06       0   66.53     .12       0  276.61    .016       0
  317.64     .12       0   333.2    .045       0   357.3     .12       0
  466.32    .016       0  488.65     .06       0  636.93     .12       0
     726     .06       0
#XS Ineff= 2 , 0
          299.38 1808.79
Permanent Ineff=
       F       F
Bank Sta=333.2,357.3
XS Rating Curve= 0 ,0
Exp/Cntr=0.3,0.1

Type RM Length L Ch R = 1 ,9713.5  ,183.9,181.1,178.1
XS GIS Cut Line= 2
     2026393.415      153857.446     2025820.443      154307.105
#Sta/Elev= 30
       0 1833.51   95.661830.085   104.5 1829.92   153.5 1823.26   176.4 1821.62
  207.79 1815.84  257.191809.942   280.9 1802.61  293.251794.755   303.8 1792.08
  335.211792.506   352.7 1790.76   372.3 1781.86   378.9 1779.92   385.4  1780.6
   389.9 1782.37     405 1788.44  434.98 1791.55   463.8 1792.98  514.11 1793.76
  520.221794.197  557.771795.807   568.3 1796.84   578.1 1800.56   584.6 1801.62
  603.021802.724   610.8 1804.62   630.4 1814.19  699.531831.081   728.4 1838.07
#Mann= 14 ,-1 , 0
       0     .06       0   95.66     .12       0  207.79     .06       0
  257.19     .12       0  293.25    .016       0  335.21     .12       0
   372.3    .045       0   389.9     .12       0  434.98    .016       0
  514.11     .12       0  520.22     .08       0  557.77     .06       0
  603.02     .12       0  699.53     .06       0
Bank Sta=372.3,389.9
XS Rating Curve= 0 ,0
Exp/Cntr=0.3,0.1

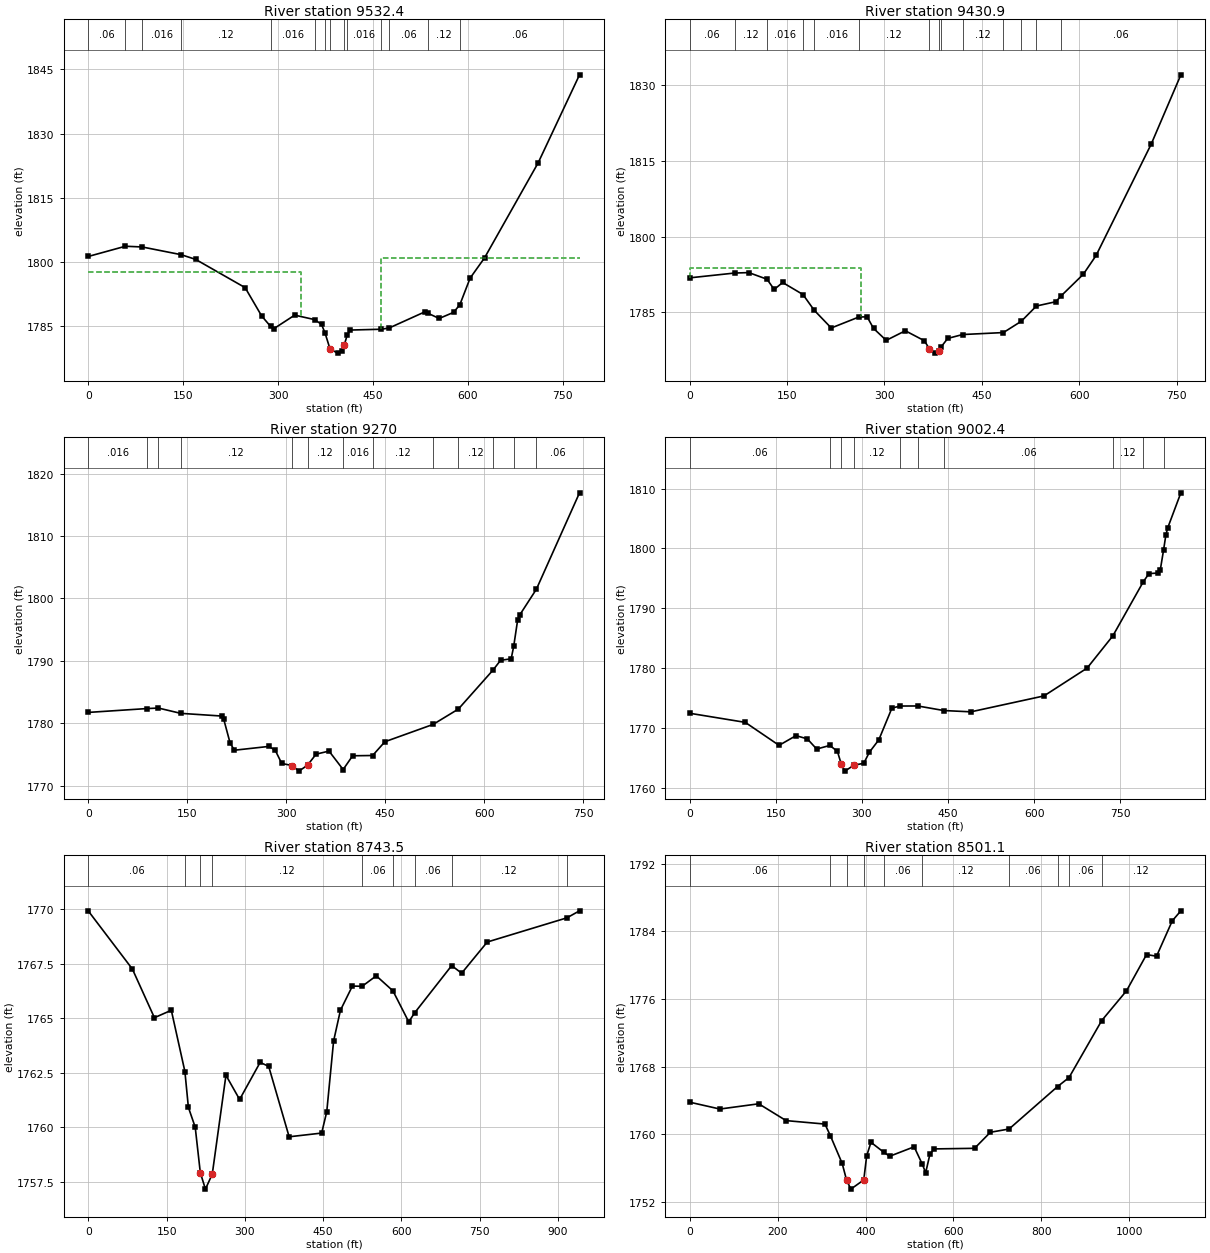
Type RM Length L Ch R = 1 ,9532.4  ,99.4,101.5,103.6
XS GIS Cut Line= 3
     2026220.653      153639.366     2026077.533      153853.559
       2025723.4      154232.554
#Sta/Elev= 30
       0 1801.26   58.581803.646   85.051803.478  146.641801.673   169.6 1800.57
   247.8 1793.96   273.9 1787.34  288.121784.875   293.5 1784.39   326.1 1787.53
   357.81786.474   368.5 1785.36  373.891783.437   382.2 1779.51   394.6 1778.64
   401.2 1779.21   404.4 1780.52  409.371782.975   414.2 1784.04  463.131784.231
  475.361784.517   531.6 1788.28  537.051787.943   554.5 1786.75   577.3 1788.18
  587.151789.967   603.4 1796.19   626.2 1800.93   711.1 1823.21   776.3 1843.75
#Mann= 14 ,-1 , 0
       0     .06       0   58.58     .12       0   85.05    .016       0
  146.64     .12       0  288.12    .016       0   357.8     .08       0
  373.89     .12       0   382.2    .045       0   404.4     .12       0
  409.37    .016       0  463.13     .12       0  475.36     .06       0
  537.05     .12       0  587.15     .06       0
#XS Ineff= 2 , 0
          336.46 1797.71  463.09         1800.86
Permanent Ineff=
       F       F
Bank Sta=382.2,404.4
XS Rating Curve= 0 ,0
Exp/Cntr=0.3,0.1

Type RM Length L Ch R = 1 ,9430.9  ,153,160.9,168.8
XS GIS Cut Line= 3
     2026169.872      153580.772     2026008.088      153797.135
     2025643.996      154119.848
#Sta/Elev= 30
       0 1791.82   69.141792.771    91.1 1792.86  119.161791.543   130.2 1789.52
   143.2  1790.9   174.51788.518  191.761785.415   218.1 1781.89  260.75 1784.07
   273.4 1784.09   283.2 1781.81   302.8 1779.44   332.2 1781.34   361.6 1779.36
   369.2 1777.77   377.9 1776.91   384.2 1777.43  386.771778.039   397.5 1779.82
  420.531780.592  483.311780.983  510.851783.218  534.181786.241     564 1787.09
  572.381788.265   606.5 1792.54   626.1 1796.25     711  1818.3   756.7 1832.03
#Mann= 14 ,-1 , 0
       0     .06       0   69.14     .12       0  119.16    .016       0
   174.5     .12       0  191.76    .016       0  260.75     .12       0
   369.2    .045       0   384.2     .12       0  386.77    .016       0
  420.53     .12       0  483.31    .016       0  510.85     .06       0
  534.18    .016       0  572.38     .06       0
#XS Ineff= 2 , 0
          264.56 1793.75
Permanent Ineff=
       F       F
Bank Sta=369.2,384.2
XS Rating Curve= 0 ,0
Exp/Cntr=0.3,0.1

Type RM Length L Ch R = 1 ,9270    ,266.1,267.6,266.8
XS GIS Cut Line= 4
     2026076.122      153544.314     2026031.851      153656.293
      2025656.46      153805.659     2025543.679      153994.618
#Sta/Elev= 30
       0 1781.74   89.35 1782.36  106.261782.437  139.921781.591   201.9 1781.16
   205.1 1780.69   214.9 1776.82   221.4 1775.68   273.6 1776.29   283.3 1775.67
   293.1 1773.56   308.7 1773.23   319.2 1772.33   332.2 1773.28   345.2 1775.05
   364.8 1775.54   386.21772.589   400.6 1774.79  430.881774.834   449.5 1777.04
  522.571779.817  560.861782.276   613.41788.525   624.8 1790.09   640.9 1790.33
  644.741792.332   650.6 1796.47   653.9 1797.36  679.141801.486   744.5 1816.93
#Mann= 13 ,-1 , 0
       0    .016       0   89.35     .12       0  106.26    .016       0
  139.92     .12       0   308.7    .045       0   332.2     .12       0
   386.2    .016       0  430.88     .12       0  522.57    .016       0
  560.86     .12       0   613.4    .016       0  644.74     .12       0
  679.14     .06       0
Bank Sta=308.7,332.2
XS Rating Curve= 0 ,0
Exp/Cntr=0.3,0.1

Type RM Length L Ch R = 1 ,9002.4  ,256.8,258.9,259.3
XS GIS Cut Line= 4
     2026024.907      153388.498     2025928.664      153425.933
     2025586.539      153549.522     2025434.629      153907.161
#Sta/Elev= 30
       0 1772.46    96.8 1770.94   155.7  1767.1   185.2 1768.72   204.9 1768.18
   221.2 1766.48   244.11767.083   257.3  1766.1   263.8 1764.04   270.4 1762.79
   286.3  1763.8   303.2 1764.09     313 1765.95   329.4 1768.01   352.3 1773.33
  367.011773.669  397.331773.679  442.731772.914   489.9  1772.7   617.2 1775.36
   692.3 1780.01  737.131785.398  790.381794.474   800.1  1795.8   816.4  1795.9
   819.7 1796.38  825.461799.731   829.5 1802.26   832.7 1803.44   855.6  1809.3
#Mann= 10 ,-1 , 0
       0     .06       0   244.1     .12       0   263.8    .045       0
   286.3     .12       0  367.01    .016       0  397.33     .12       0
  442.73     .06       0  737.13     .12       0  790.38    .016       0
  825.46     .06       0
Bank Sta=263.8,286.3
XS Rating Curve= 0 ,0
Exp/Cntr=0.3,0.1

Type RM Length L Ch R = 1 ,8743.5  ,236.4,242.4,250.7
XS GIS Cut Line= 4
     2026022.737      153306.033     2025871.903      153230.363
     2025543.136      153319.054     2025161.192      153520.877
#Sta/Elev= 30
       0 1769.91    84.4 1767.25   126.6 1765.02     159 1765.36  185.031762.553
   191.7 1760.91   204.8    1760   214.6 1757.91   224.4 1757.16   237.5 1757.85
   263.7 1762.38   289.9 1761.27   329.2 1762.97   345.6 1762.79   384.8 1759.56
   447.1 1759.73   456.9 1760.71     470 1763.95   483.1 1765.36     506 1766.47
  524.68 1766.46   551.8 1766.94  583.741766.251     614 1764.83  625.371765.244
  696.311767.408   715.4 1767.06   764.5 1768.49  917.061769.598   941.3 1769.92
#Mann= 9 ,-1 , 0
       0     .06       0  185.03     .12       0   214.6    .045       0
   237.5     .12       0  524.68     .06       0  583.74     .12       0
  625.37     .06       0  696.31     .12       0  917.06     .06       0
Bank Sta=214.6,237.5
XS Rating Curve= 0 ,0
Exp/Cntr=0.3,0.1

Type RM Length L Ch R = 1 ,8501.1  ,194.2,201.9,208.7
XS GIS Cut Line= 3
     2026158.118      153009.839     2025402.077      153013.064
     2025106.938      153221.397
#Sta/Elev= 30
       0 1763.79    68.7 1762.98   157.1  1763.6   219.3 1761.61   307.7  1761.2
  319.831759.846   346.9 1756.54   356.8 1754.58   366.6  1753.5     396 1754.59
   402.6 1757.44   412.4 1759.04  440.891757.889   454.9 1757.39   510.6 1758.51
  529.371756.421   536.8 1755.44   546.6 1757.66   556.4 1758.26     648 1758.33
     684 1760.23  726.531760.616  836.711765.635  862.881766.704   937.31773.453
   993.6 1776.97  1039.2 1781.26    1062 1781.07  1097.8 1785.26  1117.3 1786.44
#Mann= 10 ,-1 , 0
       0     .06       0  319.83     .12       0   356.8    .045       0
     396     .12       0  440.89     .06       0  529.37     .12       0
  726.53     .06       0  836.71     .12       0  862.88     .06       0
   937.3     .12       0
Bank Sta=356.8,396
XS Rating Curve= 0 ,0
Exp/Cntr=0.3,0.1