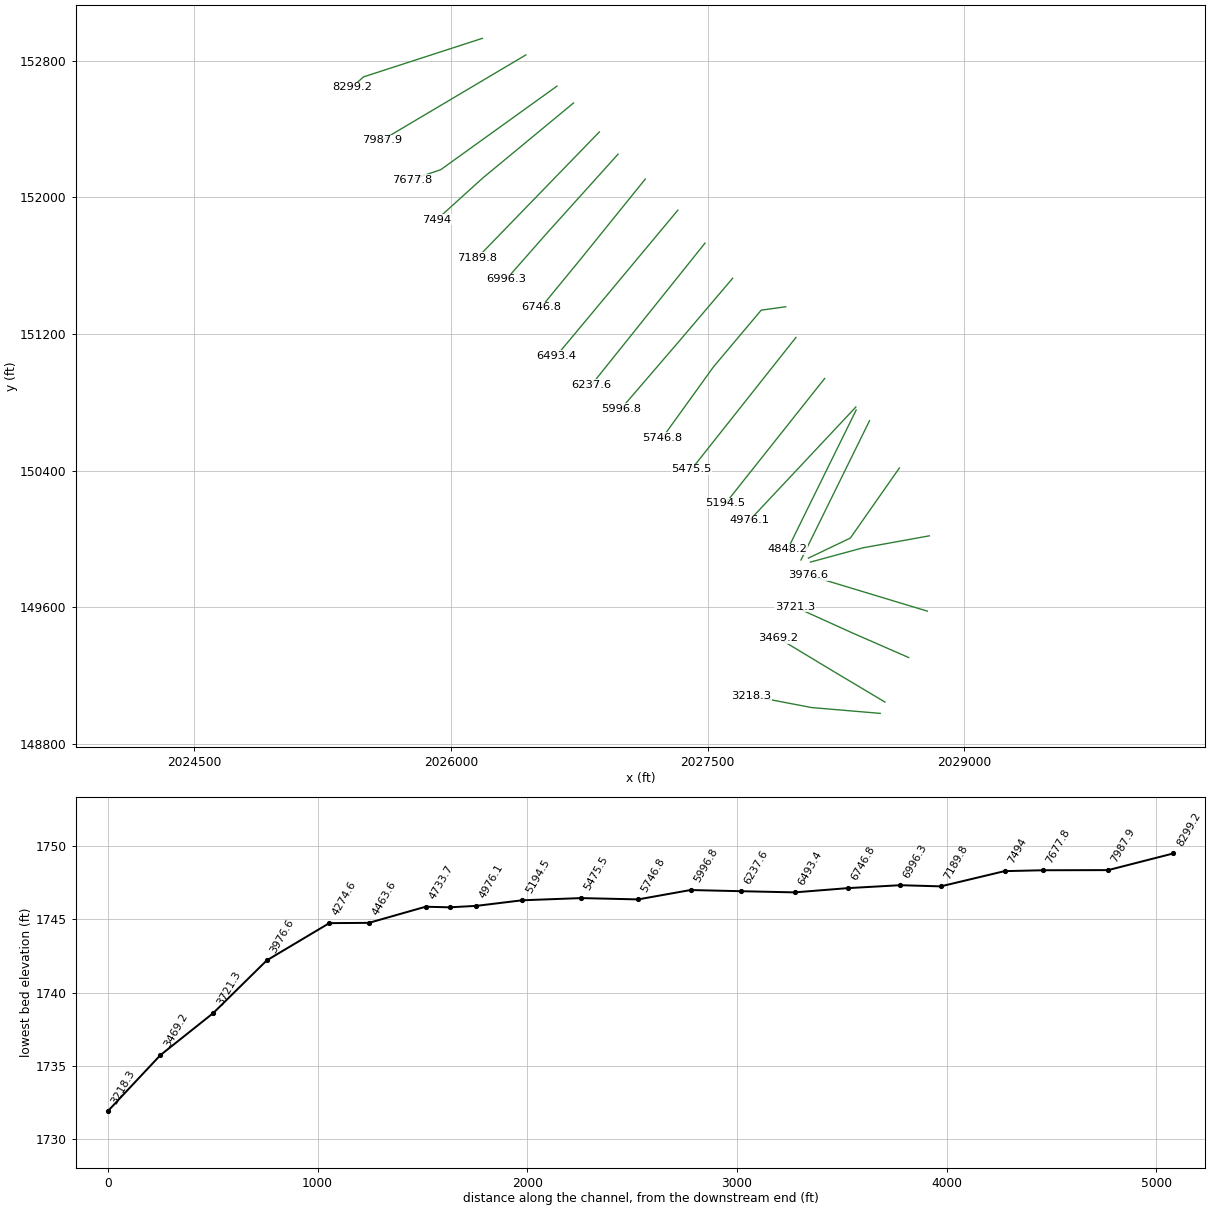
HEC-RAS study BRUSHCK.prj: BRUSHCK

--- BRUSHCK.g01 (geometry) --- (continued)

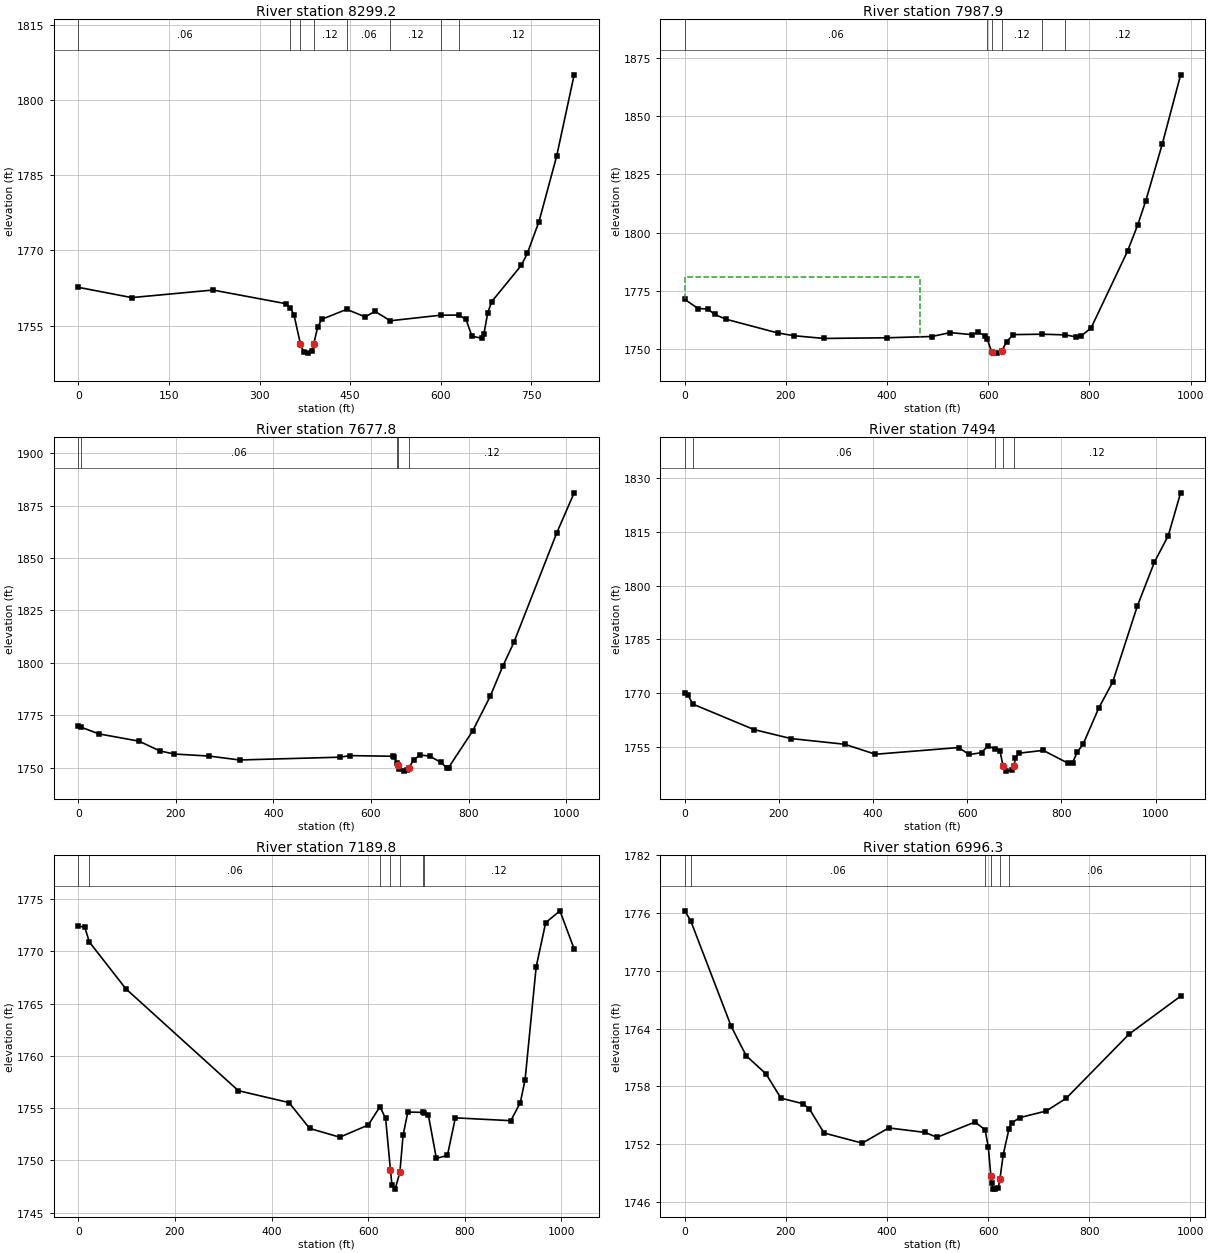
Type RM Length L Ch R = 1 ,8299.2  ,306.3,311.3,316.3
XS GIS Cut Line= 3
     2026183.327      152930.599     2025488.883      152704.904
     2025421.608       152644.14
#Sta/Elev= 30
       0 1762.63    88.4 1760.58   222.7 1762.09   343.8 1759.36  351.121758.467
   356.9  1757.2   367.7 1751.29   373.3 1749.64   379.8  1749.5   386.4 1749.96
   389.7 1751.37   396.2 1754.67   402.8 1756.24  444.171758.233   474.8 1756.74
   491.2 1757.83  516.321755.956  599.681757.069  629.621757.098   641.8 1756.24
   651.6 1752.85     668 1752.49   671.3 1753.28   677.8 1757.57   684.4 1759.79
   733.4 1767.03   743.2 1769.39   762.6 1775.76   791.7 1788.74   820.8 1805.03
#Mann= 8 ,-1 , 0
       0     .06       0  351.12     .12       0   367.7    .045       0
   389.7     .12       0  444.17     .06       0  516.32     .12       0
  599.68     .06       0  629.62     .12       0
Bank Sta=367.7,389.7
XS Rating Curve= 0 ,0
Exp/Cntr=0.3,0.1

Type RM Length L Ch R = 1 ,7987.9  ,308.1,310.1,312.1
XS GIS Cut Line= 2
     2026437.233      152833.377     2025594.603      152332.613
#Sta/Elev= 30
       0  1771.4    26.2  1767.5    45.9 1767.28      59 1764.94      82 1762.87
   183.6 1757.02   216.4 1755.81   275.4 1754.66     400 1754.95   488.5 1755.49
   524.5 1757.16   567.1  1756.3   580.2 1757.22   593.4 1755.82   597.71754.543
   606.5 1748.99   616.3 1748.36   626.2 1749.18     636  1753.2   649.1  1756.3
  706.741756.479  752.481756.176   773.7 1755.32   783.5 1755.71   803.2 1759.15
   875.3 1792.14     895 1803.13   911.4 1813.74   944.1 1838.22   980.2 1867.74
#Mann= 6 ,-1 , 0
       0     .06       0   597.7     .12       0   606.5    .045       0
   626.2     .12       0  706.74     .06       0  752.48     .12       0
#XS Ineff= 2 , 0
          464.67 1780.83
Permanent Ineff=
       F       F
Bank Sta=606.5,626.2
XS Rating Curve= 0 ,0
Exp/Cntr=0.3,0.1

Type RM Length L Ch R = 1 ,7677.8  ,182.3,183.8,186.3
XS GIS Cut Line= 3
     2026619.525      152651.085     2025939.837      152161.502
     2025770.567       152104.21
#Sta/Elev= 30
       0 1769.96    5.931769.287    42.5  1766.1   124.3 1762.66   166.9 1758.01
   196.3 1756.52   268.3 1755.53   330.5 1753.67   536.6 1755.01   556.3 1755.75
   644.6 1755.45   647.9  1754.9  652.931752.291   654.4 1751.23   657.7 1749.16
   667.5 1748.35   673.8 1748.78   677.3 1749.86   687.1 1753.58   700.2 1756.06
   719.9 1755.52   742.8 1752.61   755.8 1749.87   759.1 1750.08   808.2 1767.46
   844.2    1784   870.2 1798.48   892.9 1809.82   980.6 1861.95  1016.4 1881.14
#Mann= 5 ,-1 , 0
       0    .016       0    5.93     .06       0  652.93     .12       0
   654.4    .045       0   677.3     .12       0
Bank Sta=654.4,677.3
XS Rating Curve= 0 ,0
Exp/Cntr=0.3,0.1

Type RM Length L Ch R = 1 ,7494    ,301.6,304.2,305.6
XS GIS Cut Line= 3
     2026715.879      152552.127     2026185.283      152112.548
     2025915.719      151867.943
#Sta/Elev= 30
       0 1769.93     6.5 1769.48   17.531766.948     147 1759.87   225.3 1757.37
   339.6 1755.78   404.9 1752.99   581.3 1754.86   604.1 1752.93   630.2 1753.42
   643.3 1755.29  659.391754.489   669.4 1753.91     676 1749.64   682.5 1748.29
   695.6  1748.5   698.9  1749.7   702.2 1751.91   708.7 1753.28   761.2 1754.07
   813.6 1750.52   823.5 1750.66   833.3 1753.53   846.4 1755.95   879.2  1765.9
   908.7 1773.11   961.2 1794.35   997.3 1806.52  1026.8 1813.95    1053 1825.86
#Mann= 5 ,-1 , 0
       0    .016       0   17.53     .06       0  659.39     .12       0
     676    .045       0   698.9     .12       0
Bank Sta=676,698.9
XS Rating Curve= 0 ,0
Exp/Cntr=0.3,0.1

Type RM Length L Ch R = 1 ,7189.8  ,192.6,193.5,194.6
XS GIS Cut Line= 2
     2026866.921      152382.856     2026152.931      151645.155
#Sta/Elev= 30
       0 1772.39    13.1 1772.35   22.681770.903    98.4 1766.42   331.3 1756.67
   436.2 1755.53   478.9 1753.06   541.2 1752.22   600.2 1753.38  624.521755.136
   636.3 1754.01   646.2 1749.08   649.4 1747.61     656 1747.25   665.8 1748.88
   672.4 1752.41   682.2 1754.62  713.411754.595  715.431754.582   724.9  1754.3
   741.3 1750.19   764.2 1750.48   780.6 1754.07   895.4  1753.8   915.1 1755.52
     925 1757.73   947.9  1768.5   967.6 1772.74   997.1 1773.88  1026.6 1770.23
#Mann= 7 ,-1 , 0
       0    .016       0   22.68     .06       0  624.52     .12       0
   646.2    .045       0   665.8     .12       0  713.41     .06       0
  715.43     .12       0
Bank Sta=646.2,665.8
XS Rating Curve= 0 ,0
Exp/Cntr=0.3,0.1

Type RM Length L Ch R = 1 ,6996.3  ,248.2,249.5,250.2
XS GIS Cut Line= 3
     2026976.296      152252.647     2026563.968      151794.109
     2026323.686      151520.684
#Sta/Elev= 30
       0 1776.25   11.731775.207    91.8 1764.24   121.4 1761.19   160.7  1759.3
   190.2 1756.78   232.9 1756.22     246  1755.7   275.5 1753.16     351 1752.11
   403.4 1753.69   475.6 1753.22   498.6 1752.71     574  1754.3  593.92  1753.5
   600.3  1751.7  605.43 1748.67   606.8 1747.92   610.1 1747.35   613.4 1747.33
   619.9 1747.44   623.4 1748.41   629.8 1750.91  641.271753.605   646.2  1754.2
   662.6 1754.76     715 1755.45   754.4 1756.77     879 1763.45   980.7 1767.38
#Mann= 6 ,-1 , 0
       0    .016       0   11.73     .06       0  593.92     .12       0
  605.43    .045       0   623.4     .12       0  641.27     .06       0
Bank Sta=605.43,623.4
XS Rating Curve= 0 ,0
Exp/Cntr=0.3,0.1

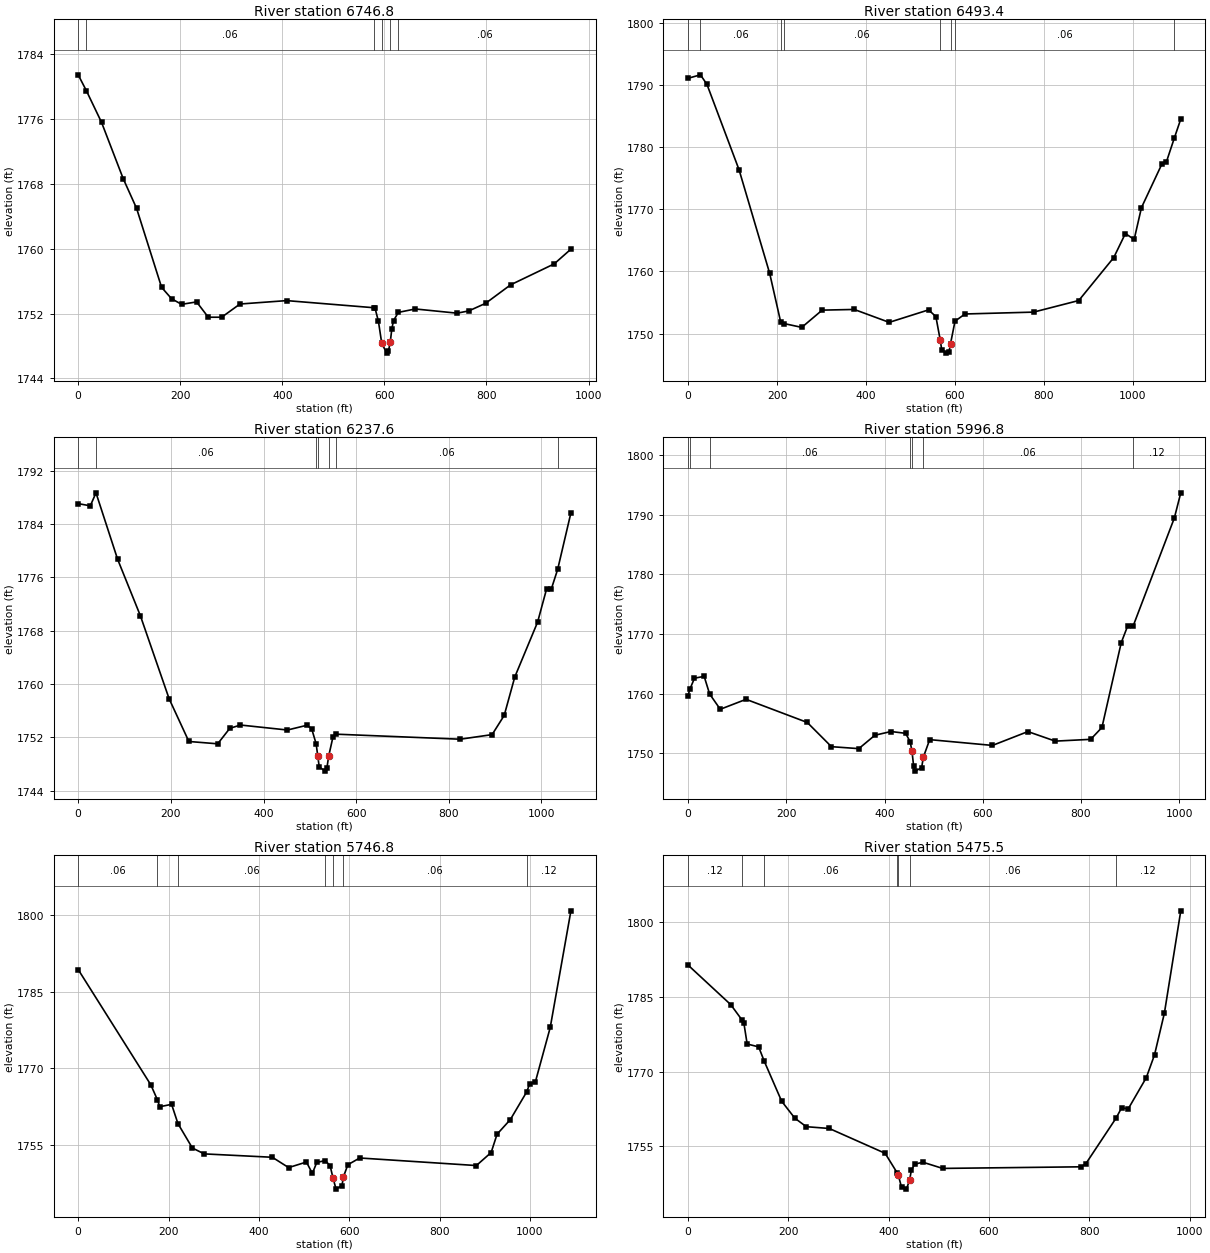
Type RM Length L Ch R = 1 ,6746.8  ,253.7,253.4,253.2
XS GIS Cut Line= 3
      2027135.15      152106.814     2026757.793      151638.572
     2026527.152      151356.968
#Sta/Elev= 30
       0 1781.47   16.021779.516    45.8  1775.6    88.2 1768.66   114.4    1765
   163.4 1755.25     183 1753.84   202.6 1753.15     232 1753.45   254.9 1751.56
   281.1 1751.56     317 1753.19   408.5 1753.61  579.281752.732   581.8 1752.64
   588.3 1751.04   594.8 1748.32   604.6 1747.13   607.9  1747.4   611.5 1748.51
   614.5 1750.11   617.8 1751.14  627.291752.156   660.4 1752.58   742.4 1752.06
   765.3 1752.34   798.1 1753.27   847.3 1755.56   932.6 1758.14   965.4 1759.96
#Mann= 6 ,-1 , 0
       0    .016       0   16.02     .06       0  579.28     .12       0
   594.8    .045       0   611.5     .12       0  627.29     .06       0
Bank Sta=594.8,611.5
XS Rating Curve= 0 ,0
Exp/Cntr=0.3,0.1

Type RM Length L Ch R = 1 ,6493.4  ,255.3,255.8,256.2
XS GIS Cut Line= 2
     2027325.254      151924.522     2026616.921       151072.96
#Sta/Elev= 30
       0 1791.14   27.921791.697    42.6 1790.14   114.7 1776.39   183.5  1759.7
  208.221751.865  215.561751.609   255.6 1750.99   301.5 1753.77   373.6 1753.88
   452.2  1751.8   540.7 1753.81   557.1 1752.73   566.9 1748.94   570.2 1747.41
     580 1746.84   586.6 1747.05     590 1748.35  600.111751.993   622.6 1753.15
   776.7 1753.45   878.3 1755.32   956.9 1762.24   983.1 1766.12  1002.8 1765.16
  1019.2 1770.29    1065  1777.3  1074.9 1777.58 1093.131781.515  1107.6 1784.57
#Mann= 8 ,-1 , 0
       0    .016       0   27.92     .06       0  208.22     .12       0
  215.56     .06       0   566.9    .045       0     590     .12       0
  600.11     .06       0 1093.13     .12       0
Bank Sta=566.9,590
XS Rating Curve= 0 ,0
Exp/Cntr=0.3,0.1

Type RM Length L Ch R = 1 ,6237.6  ,241.5,240.9,240.1
XS GIS Cut Line= 2
     2027484.108      151731.814     2026820.046      150901.085
#Sta/Elev= 30
       0 1787.07    26.2 1786.74   38.421788.691    85.1 1778.72   134.2 1770.25
   196.3 1757.78   238.9 1751.37   301.1 1751.02   327.2 1753.34   350.2 1753.84
   451.6 1753.09   494.1 1753.81     504 1753.27   513.61751.022     517 1749.24
   520.3 1747.54   533.4 1746.92   536.7 1747.32   540.6 1749.15   549.8 1752.01
  555.47 1752.47   824.6 1751.71   893.4  1752.4   919.5 1755.28   942.4 1761.06
   991.5 1769.27  1011.2 1774.32    1021 1774.21 1034.921777.211  1063.5 1785.69
#Mann= 7 ,-1 , 0
       0    .016       0   38.42     .06       0   513.6     .12       0
     517    .045       0   540.6     .12       0  555.47     .06       0
 1034.92     .12       0
Bank Sta=517,540.6
XS Rating Curve= 0 ,0
Exp/Cntr=0.3,0.1

Type RM Length L Ch R = 1 ,5996.8  ,249.9,250,251.9
XS GIS Cut Line= 3
     2027645.567      151526.085     2027338.021       151163.35
     2026994.525      150763.064
#Sta/Elev= 30
       0 1759.65    3.561760.695    13.1 1762.58    32.8 1762.89   43.921759.936
    65.6 1757.37   118.1 1759.04   242.7 1755.16   291.9  1751.1   347.6 1750.77
   380.4 1753.02   413.2 1753.64   442.8 1753.34  452.121751.941   455.9  1750.3
   459.2 1747.86   462.4    1747   475.6 1747.59   478.8  1749.3   491.9 1752.28
   619.7 1751.31   691.8 1753.63   747.5 1752.03   819.6 1752.33   842.5 1754.32
   881.8 1768.54   894.9 1771.34  905.941771.311   989.9 1789.44    1003 1793.66
#Mann= 7 ,-1 , 0
       0     .06       0    3.56    .016       0   43.92     .06       0
  452.12     .12       0   455.9    .045       0   478.8     .06       0
  905.94     .12       0
Bank Sta=455.9,478.8
XS Rating Curve= 0 ,0
Exp/Cntr=0.3,0.1

Type RM Length L Ch R = 1 ,5746.8  ,270.5,271.2,270.2
XS GIS Cut Line= 4
     2027955.462      151359.418     2027812.334      151339.331
     2027533.828      151007.931     2027234.108      150591.189
#Sta/Elev= 30
       0  1789.3   160.9 1766.74  175.461763.811   180.6 1762.47   206.8 1762.94
   220.91759.162   252.8  1754.4     279 1753.25   429.8 1752.59   465.9 1750.57
   505.3 1751.66   518.4 1749.43   528.2 1751.58  546.85 1751.94   557.7 1750.95
   564.3 1748.47   570.9 1746.36     584 1747.06   587.2 1748.77     597 1751.13
   623.2 1752.45   881.5 1750.97   914.2 1753.52   927.3  1757.1   956.7 1759.96
  992.811765.359   999.2 1766.86  1012.3 1767.39    1045 1777.97  1090.8 1800.78
#Mann= 7 ,-1 , 0
       0     .06       0  175.46    .016       0   220.9     .06       0
  546.85     .12       0   564.3    .045       0   587.2     .06       0
  992.81     .12       0
Bank Sta=564.3,587.2
XS Rating Curve= 0 ,0
Exp/Cntr=0.3,0.1

Type RM Length L Ch R = 1 ,5475.5  ,281.1,281.1,281.1
XS GIS Cut Line= 2
     2028015.358      151179.731     2027405.983      150408.897
#Sta/Elev= 30
       0 1791.34    85.2 1783.41  107.281780.387   111.4 1779.68   117.9 1775.53
   140.8 1774.95  152.121772.042   186.7 1764.06   212.9 1760.67   235.8 1758.96
   281.7  1758.6     393 1753.63  417.131749.697   419.2 1749.27   425.8 1746.82
   435.6 1746.45   441.9 1748.32   445.4 1750.26     452 1751.45   468.4 1751.84
   507.7  1750.6   782.8 1750.92   792.6 1751.44  853.211760.625   864.7 1762.75
   877.8 1762.53   913.8 1768.78   930.2 1773.34   949.9 1781.71   982.6 1802.21
#Mann= 7 ,-1 , 0
       0     .12       0  107.28    .016       0  152.12     .06       0
  417.13     .12       0   419.2    .045       0   441.9     .06       0
  853.21     .12       0
Bank Sta=419.2,441.9
XS Rating Curve= 0 ,0
Exp/Cntr=0.3,0.1

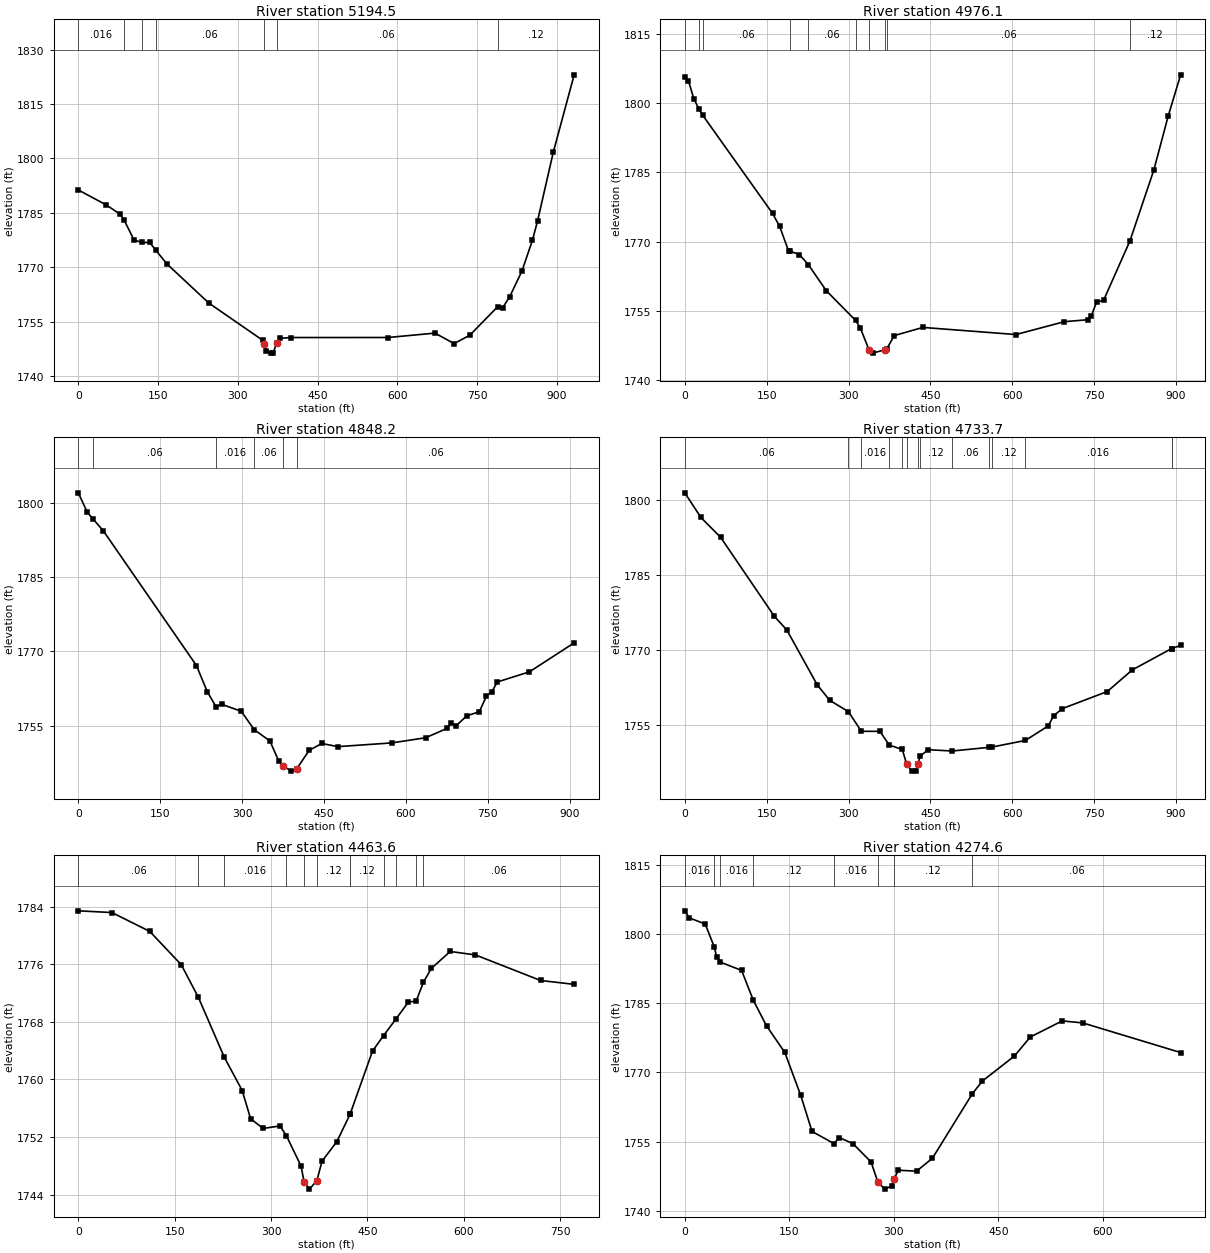
Type RM Length L Ch R = 1 ,5194.5  ,220.2,218.4,216.5
XS GIS Cut Line= 2
       2028183.1      150939.521       2027603.9      150208.377
#Sta/Elev= 30
       0  1791.3    52.4 1787.19    78.6 1784.62   86.171782.999   104.7 1777.52
  119.481776.826   134.2 1776.82  145.431774.738   166.9 1770.87   245.5 1760.11
   346.9 1749.84   350.2 1748.76   353.5 1746.86   363.3  1746.3   366.6 1746.31
   373.1 1749.14   379.6 1750.38   399.3  1750.6   582.6 1750.61   670.9 1751.82
   706.9 1748.94   736.4 1751.22   788.71759.074   798.6 1758.88   811.7  1761.9
   834.6 1768.96   854.2 1777.38     864  1782.8   893.5  1801.7   932.8 1823.06
#Mann= 7 ,-1 , 0
       0    .016       0   86.17     .08       0  119.48    .016       0
  145.43     .06       0   350.2    .045       0   373.1     .06       0
   788.7     .12       0
Bank Sta=350.2,373.1
XS Rating Curve= 0 ,0
Exp/Cntr=0.3,0.1

Type RM Length L Ch R = 1 ,4976.1  ,118.4,127.9,138.8
XS GIS Cut Line= 2
     2028365.358      150772.434     2027744.525      150109.418
#Sta/Elev= 30
       0 1805.64     6.6 1804.88    16.4 1800.98   26.171798.666   33.021797.351
   160.7 1776.15   173.8 1773.32   190.2 1767.98  193.341767.951   209.9 1767.24
  226.461765.038     259 1759.45  312.87 1752.99   321.4 1751.41   337.8 1746.53
   344.3 1745.92   367.3 1746.67  370.54 1746.92   383.6 1749.71   436.1 1751.48
   606.6 1749.94   695.2 1752.72   737.8 1753.14   744.4 1753.89   754.2 1756.94
   767.3 1757.38   815.4 1770.18   859.1 1785.48   885.4 1797.15   908.3 1806.12
#Mann= 10 ,-1 , 0
       0     .12       0   26.17    .016       0   33.02     .06       0
  193.34    .016       0  226.46     .06       0  312.87     .12       0
   337.8    .045       0   367.3     .12       0  370.54     .06       0
   815.4     .12       0
Bank Sta=337.8,367.3
XS Rating Curve= 0 ,0
Exp/Cntr=0.3,0.1

Type RM Length L Ch R = 1 ,4848.2  ,116.4,114.5,111.3
XS GIS Cut Line= 2
     2028367.134      150754.817     2027966.708      149939.536
#Sta/Elev= 30
       0 1801.97    16.4 1798.04    26.81796.708    45.9 1794.28   216.4 1767.12
   236.1 1761.87  252.121758.839   262.3 1759.31   298.4  1757.9  322.351754.166
   350.9 1751.92   367.3 1747.82   375.1 1746.86   390.1 1745.82     400 1746.28
     423 1750.02     446  1751.4   475.5 1750.76   573.8 1751.51   636.1 1752.55
   675.5 1754.45     682  1755.5   691.9 1754.96   711.6 1756.98   734.5  1757.8
   747.6 1760.94   757.5  1761.8   767.3  1763.8   826.3 1765.85   908.3  1771.7
#Mann= 6 ,-1 , 0
       0     .12       0    26.8     .06       0  252.12    .016       0
  322.35     .06       0   375.1    .045       0     400     .06       0
Bank Sta=375.1,400
XS Rating Curve= 0 ,0
Exp/Cntr=0.3,0.1

Type RM Length L Ch R = 1 ,4733.7  ,271.3,270.1,261.2
XS GIS Cut Line= 2
     2028445.259      150692.317     2028044.833      149877.036
#Sta/Elev= 30
       0  1801.5    29.5 1796.57    65.6 1792.61     164 1776.82   186.9 1774.08
   242.6 1763.11   265.6    1760  299.611757.766  323.371753.827   357.4 1753.81
  374.641751.066  398.341750.192   406.7 1747.19   416.4 1745.86     423 1745.98
  426.79 1747.25  431.251748.889     446 1750.14   489.81749.883  556.81 1750.61
  562.891750.676  623.811751.992   665.7 1754.89   675.5 1756.92   691.9 1758.37
   773.9 1761.77   819.8  1766.1  891.811770.365     8921770.373   908.3 1770.98
#Mann= 14 ,-1 , 0
       0     .06       0  299.61     .12       0  323.37    .016       0
  374.64     .06       0  398.34     .12       0   406.7    .045       0
  426.79    .016       0  431.25     .12       0   489.8     .06       0
  556.81    .016       0  562.89     .12       0  623.81    .016       0
  891.81     .12       0     892    .016       0
Bank Sta=406.7,426.79
XS Rating Curve= 0 ,0
Exp/Cntr=0.3,0.1

Type RM Length L Ch R = 1 ,4463.6  ,206.5,189,171.2
XS GIS Cut Line= 3
     2028619.582      150415.552     2028333.067      150005.252
     2028088.275      149888.064
#Sta/Elev= 30
       0 1783.44    52.3  1783.2   111.2 1780.58   160.3 1775.94  186.76 1771.43
  227.221763.091   255.1 1758.46   268.2 1754.53   287.8  1753.2     314 1753.54
  323.941752.172   346.7 1747.96  351.38 1745.77   359.8 1744.76  371.28 1745.95
   379.4 1748.65   402.3 1751.35  422.921755.157  423.391755.271   457.9 1763.95
  475.231766.111  494.841768.458   513.5 1770.73  525.941770.912  537.13 1773.51
   549.5 1775.44   578.9 1777.79   618.2 1777.31   719.5 1773.76   771.8 1773.22
#Mann= 12 ,-1 , 0
       0     .06       0  186.76     .12       0  227.22    .016       0
  323.94     .12       0  351.38    .045       0  371.28     .12       0
  422.92     .06       0  423.39     .12       0  475.23     .08       0
  494.84     .06       0  525.94    .016       0  537.13     .06       0
Bank Sta=351.38,371.28
XS Rating Curve= 0 ,0
Exp/Cntr=0.3,0.1

Type RM Length L Ch R = 1 ,4274.6  ,308.3,297.9,286.6
XS GIS Cut Line= 3
     2028794.004      150018.272     2028405.983       149947.96
     2028100.129      149864.717
#Sta/Elev= 30
       0 1805.01     6.5 1803.48    29.3 1802.15   42.171797.232    45.6 1795.11
   51.04  1793.9    81.5  1792.1   98.331785.623   117.3 1780.09   143.4 1774.36
   166.2  1765.1   182.5 1757.24  213.961754.602   221.6 1755.91   241.2 1754.59
   267.2 1750.62     277 1746.26   286.8 1744.74   296.6 1745.41   299.8 1746.85
   306.4 1748.84   332.4 1748.62   355.2 1751.42  412.53 1765.41     427 1768.16
   472.8 1773.55   495.6 1777.68   541.4 1781.17   570.8 1780.74   711.3 1774.32
#Mann= 8 ,-1 , 0
       0    .016       0   42.17     .12       0   51.04    .016       0
   98.33     .12       0  213.96    .016       0     277    .045       0
   299.8     .12       0  412.53     .06       0
Bank Sta=277,299.8
XS Rating Curve= 0 ,0
Exp/Cntr=0.3,0.1

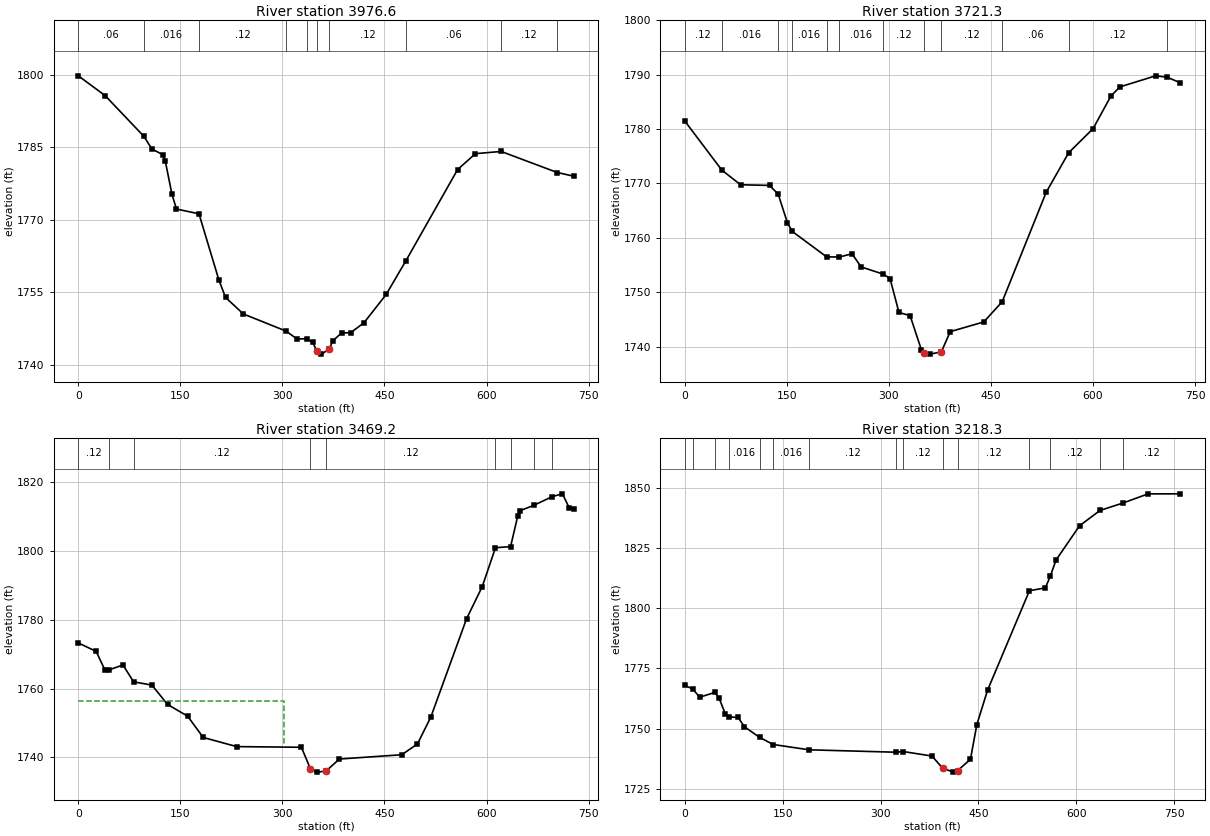
Type RM Length L Ch R = 1 ,3976.6  ,257.7,255.4,252.3
XS GIS Cut Line= 3
     2028782.879      149577.564     2028434.522      149683.126
     2028086.165      149788.689
#Sta/Elev= 30
       0 1799.77    39.4 1795.68   96.421787.244   108.2 1784.63   124.6 1783.42
   127.9 1782.08   137.7 1775.24   144.3 1772.21  177.361771.229   206.6 1757.54
   216.4 1753.92   242.7  1750.5  305.191746.974   321.4 1745.34  335.451745.377
   344.3 1744.65   350.9 1742.82   357.4  1742.2     369 1743.25   373.8 1744.91
     387  1746.6   400.1 1746.61   419.8 1748.68   452.5 1754.54  481.581761.539
   557.5 1780.39   583.7 1783.67  621.451784.125  703.921779.771     728 1779.01
#Mann= 10 ,-1 , 0
       0     .06       0   96.42    .016       0  177.36     .12       0
  305.19    .016       0  335.45     .12       0   350.9    .045       0
     369     .12       0  481.58     .06       0  621.45     .12       0
  703.92     .06       0
Bank Sta=350.9,369
XS Rating Curve= 0 ,0
Exp/Cntr=0.3,0.1

Type RM Length L Ch R = 1 ,3721.3  ,254.9,252,249.4
XS GIS Cut Line= 3
     2028673.886      149305.867     2028340.484      149451.929
     2028009.029      149602.472
#Sta/Elev= 30
       0 1781.49   54.321772.472      82 1769.76   124.6 1769.64  137.271768.045
   150.8 1762.78  158.061761.166  208.451756.493  227.311756.471   245.9 1757.06
   259.1 1754.65  291.81 1753.31   301.7  1752.5   314.8 1746.26   331.2 1745.68
   347.6 1739.44     352 1738.88   360.7  1738.6   377.1 1739.02   390.2 1742.74
   439.4 1744.52  466.49 1748.23   531.2 1768.38  564.221775.651   600.1 1780.08
   626.4  1786.1   639.5 1787.76     692  1789.8  708.611789.559     728 1788.54
#Mann= 12 ,-1 , 0
       0     .12       0   54.32    .016       0  137.27     .08       0
  158.06    .016       0  208.45     .08       0  227.31    .016       0
  291.81     .12       0     352    .045       0   377.1     .12       0
  466.49     .06       0  564.22     .12       0  708.61    .016       0
Bank Sta=352,377.1
XS Rating Curve= 0 ,0
Exp/Cntr=0.3,0.1

Type RM Length L Ch R = 1 ,3469.2  ,240.5,250.9,258.8
XS GIS Cut Line= 3
     2028535.503      149045.283      2028223.01      149231.962
     2027911.564      149420.367
#Sta/Elev= 30
       0  1773.3    26.2 1770.84    39.4 1765.32   45.05 1765.46    65.6 1766.89
   81.321761.979   108.2 1761.04   131.2 1755.41   160.7    1752   183.6 1745.81
   232.8 1743.15   327.9 1742.96     341 1736.75   350.9 1735.73     364 1736.02
   383.7 1739.54   475.5 1740.79   498.5 1743.94   518.1 1751.74   570.6 1780.32
   593.6 1789.64  613.141800.989  635.341801.309     646 1810.33   649.3 1811.76
  669.321813.304  696.761815.866   711.6 1816.66   721.4 1812.63     728  1812.2
#Mann= 9 ,-1 , 0
       0     .12       0   45.05    .016       0   81.32     .12       0
     341    .045       0     364     .12       0  613.14    .016       0
  635.34     .12       0  669.32    .016       0  696.76     .12       0
#XS Ineff= 2 , 0
          302.54 1756.31
Permanent Ineff=
       F       F
Bank Sta=341,364
XS Rating Curve= 0 ,0
Exp/Cntr=0.3,0.1

Type RM Length L Ch R = 1 ,3218.3  ,242,251.5,258.6
XS GIS Cut Line= 3
     2028507.349       148979.05     2028107.038      149013.062
     2027756.078      149080.269
#Sta/Elev= 30
       0 1767.92   12.161766.484    22.9 1763.03    45.91765.013    52.3 1762.87
    62.1  1756.1    67.5 1754.85    81.7 1754.63    91.5 1750.74  114.871746.307
  135.591743.378  190.491741.177   324.11740.166  334.581740.456   378.9 1738.58
   395.2 1733.52   411.6  1731.9   418.1 1732.51   437.8 1737.23   447.6 1751.64
     464 1765.94   528.21807.288   552.6 1808.48  560.171813.342     569 1820.06
     605 1834.28   636.41840.658  671.771843.758   709.9 1847.54   759.1 1847.56
#Mann= 15 ,-1 , 0
       0     .12       0   12.16    .016       0    45.9     .08       0
    67.5    .016       0  114.87     .12       0  135.59    .016       0
  190.49     .12       0   324.1     .06       0  334.58     .12       0
   395.2    .045       0   418.1     .12       0   528.2    .016       0
  560.17     .12       0   636.4    .016       0  671.77     .12       0
Bank Sta=395.2,418.1
XS Rating Curve= 0 ,0
Exp/Cntr=0.3,0.1