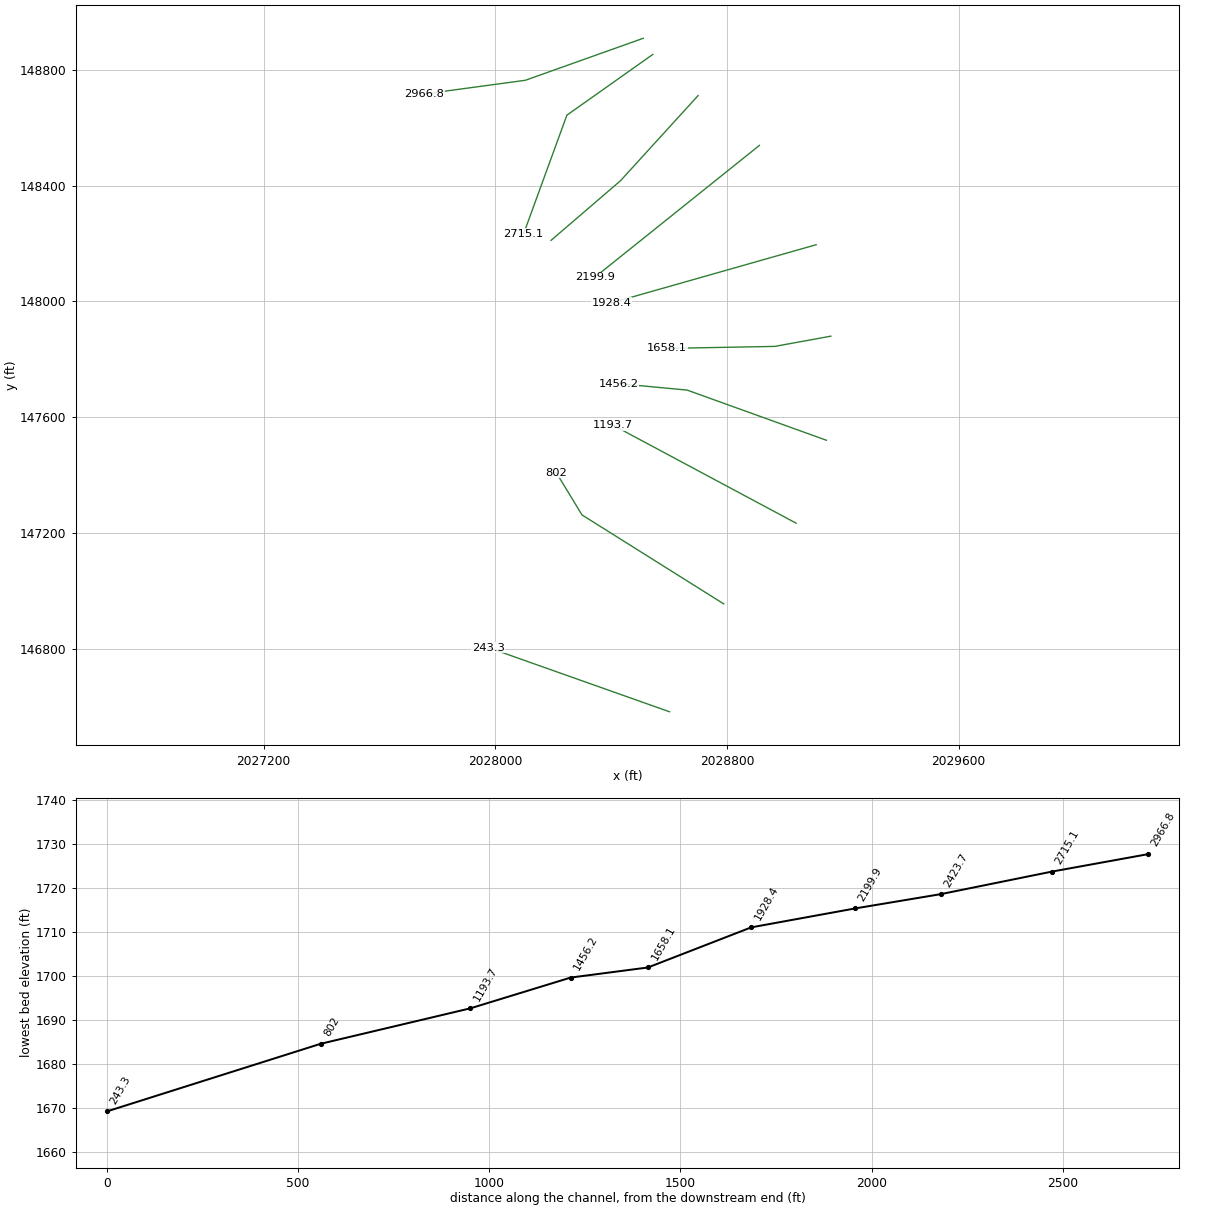
HEC-RAS study BRUSHCK.prj: BRUSHCK

--- BRUSHCK.g01 (geometry) --- (continued)

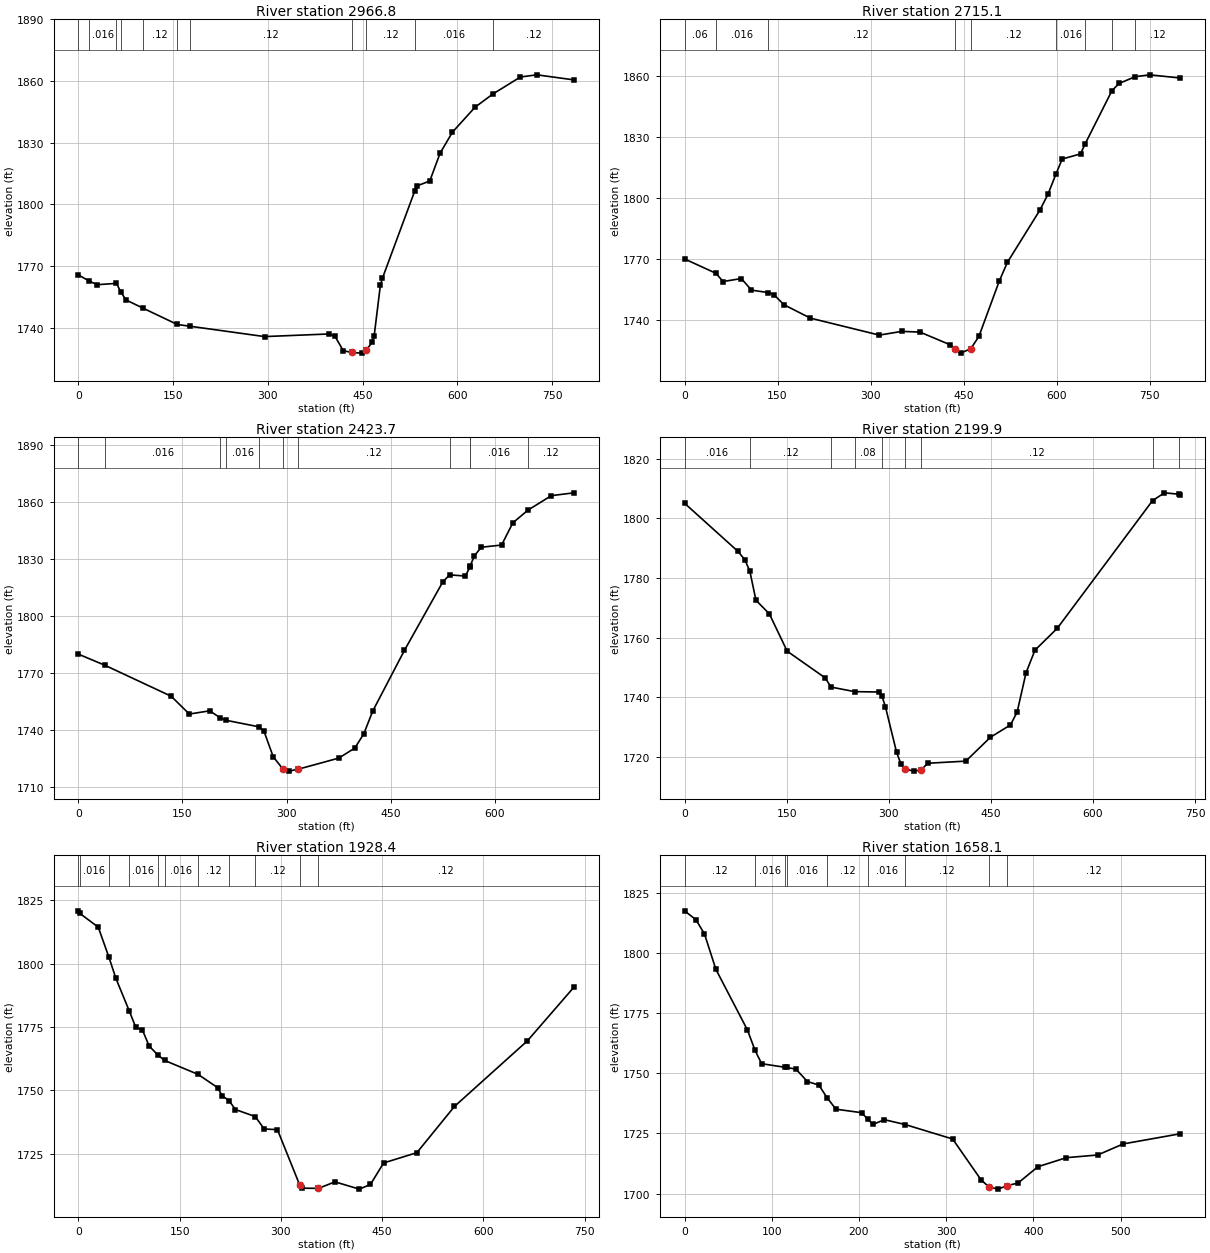
Type RM Length L Ch R = 1 ,2966.8  ,231.2,251.7,276.2
XS GIS Cut Line= 3
     2028511.103       148908.88     2028103.783      148763.782
     2027755.036      148716.555
#Sta/Elev= 30
       0 1765.71   16.841762.806    29.5 1760.95   60.371761.591    67.21757.452
    75.3 1753.57  102.331749.552  156.651741.603  176.051740.779   294.8 1735.72
   396.4 1736.99   406.2 1735.82   419.3 1728.89   432.4 1727.99   448.7 1727.68
   455.2 1728.96     465 1732.89   468.2  1736.1     478 1760.64   481.3 1764.12
  532.511806.575   536.7 1809.07   556.2 1811.37   572.5 1824.88   592.1 1835.13
   627.9 1847.26   656.31853.715   699.6 1861.93   725.7 1862.99   784.3 1860.53
#Mann= 11 ,-1 , 0
       0     .12       0   16.84    .016       0   60.37     .08       0
    67.2    .016       0  102.33     .12       0  156.65    .016       0
  176.05     .12       0   432.4    .045       0   455.2     .12       0
  532.51    .016       0   656.3     .12       0
Bank Sta=432.4,455.2
XS Rating Curve= 0 ,0
Exp/Cntr=0.3,0.1

Type RM Length L Ch R = 1 ,2715.1  ,300.2,291.4,282.3
XS GIS Cut Line= 3
     2028543.786      148853.053     2028247.129      148643.272
     2028097.692      148233.807
#Sta/Elev= 30
       0  1770.1   50.611763.036    62.2 1758.96    91.6 1760.44     108 1754.74
  134.861753.532     144 1752.53   160.4 1747.54   202.9 1740.95   314.2 1732.58
   350.2 1734.42   379.7 1734.07   428.9 1727.76   435.4 1725.74   445.3 1723.71
   461.7 1725.88   474.8 1732.01   507.5 1759.13   520.6 1768.38   573.1 1794.15
   586.2 1801.99  599.021811.933   609.1 1819.31   638.6 1821.82   645.91826.672
  689.341852.989   700.9 1856.53  726.75 1859.84   750.1 1860.76   799.2  1859.2
#Mann= 9 ,-1 , 0
       0     .06       0   50.61    .016       0  134.86     .12       0
   435.4    .045       0   461.7     .12       0  599.02    .016       0
   645.9     .12       0  689.34    .016       0  726.75     .12       0
Bank Sta=435.4,461.7
XS Rating Curve= 0 ,0
Exp/Cntr=0.3,0.1

Type RM Length L Ch R = 1 ,2423.7  ,227.4,223.9,220.5
XS GIS Cut Line= 3
     2028700.254      148710.981     2028432.025       148416.71
     2028192.442      148210.981
#Sta/Elev= 30
       0 1780.02   38.451774.143   133.8  1757.9   159.9 1748.55   189.3 1750.24
  204.211746.627  212.951745.262  260.461741.826   267.6 1739.43   280.7 1726.19
   295.2 1719.44   303.5 1718.57   316.6 1719.56   375.3 1725.42   398.2 1730.64
   411.2 1738.08   424.2 1750.14   469.8 1781.97   525.1 1817.95  534.941821.654
   557.7 1821.01  563.921825.639   564.81826.509   570.7 1831.69   580.5 1836.15
   609.8  1837.3   626.1    1849     6481855.685   681.4 1863.24     714 1864.73
#Mann= 11 ,-1 , 0
       0     .12       0   38.45    .016       0  204.21     .12       0
  212.95    .016       0  260.46     .12       0   295.2    .045       0
   316.6     .12       0  534.94    .016       0  563.92     .12       0
   564.8    .016       0     648     .12       0
Bank Sta=295.2,316.6
XS Rating Curve= 0 ,0
Exp/Cntr=0.3,0.1

Type RM Length L Ch R = 1 ,2199.9  ,280.4,271.4,262.3
XS GIS Cut Line= 3
      2028911.96      148539.009     2028627.901      148311.398
     2028343.843      148083.787
#Sta/Elev= 30
       0 1805.06    78.7 1788.89    88.5 1786.14   95.931782.328   104.9 1772.57
   124.6    1768   150.8 1755.49   206.6 1746.56   215.21743.476   249.8 1741.95
   285.3 1741.82  289.891740.531   295.1  1736.9   311.5 1721.64   318.1 1717.56
   324.1 1715.94   337.8 1715.32   347.6 1715.74   357.4 1717.96   413.2 1718.67
   449.3 1726.65   478.8  1730.8   488.6 1735.11   501.7 1748.29   514.8 1755.84
   547.6 1763.17  687.491805.925     705 1808.54  725.831808.084     728 1807.92
#Mann= 9 ,-1 , 0
       0    .016       0   95.93     .12       0   215.2    .016       0
   249.8     .08       0  289.89     .12       0   324.1    .045       0
   347.6     .12       0  687.49    .016       0  725.83     .12       0
Bank Sta=324.1,347.6
XS Rating Curve= 0 ,0
Exp/Cntr=0.3,0.1

Type RM Length L Ch R = 1 ,1928.4  ,276,270.4,264.1
XS GIS Cut Line= 2
     2029107.856       148195.99     2028401.759      147995.391
#Sta/Elev= 30
       0 1820.88    1.971819.913    29.5 1814.44   45.24 1802.64    55.7 1794.18
   75.19 1781.53    85.2 1774.83      95 1773.81   104.9  1767.5  117.811763.959
  127.941761.807   177.21756.336   206.4 1751.08     213 1747.88  223.17 1745.98
   232.7 1742.44  262.071739.664   275.3 1734.77   294.9  1734.5   327.7 1712.76
     331  1711.4   355.7 1711.32   380.1 1713.89   416.2 1711.02   432.6 1712.85
   452.2 1721.35   501.4 1725.41   557.1 1743.66   665.2 1769.58     734 1790.73
#Mann= 11 ,-1 , 0
       0     .12       0    1.97    .016       0   45.24     .12       0
   75.19    .016       0  117.81     .12       0  127.94    .016       0
   177.2     .12       0  223.17    .016       0  262.07     .12       0
   327.7    .045       0   355.7     .12       0
Bank Sta=327.7,355.7
XS Rating Curve= 0 ,0
Exp/Cntr=0.3,0.1

Type RM Length L Ch R = 1 ,1658.1  ,209.8,201.8,193
XS GIS Cut Line= 3
     2029158.587      147880.252     2028965.227       147844.91
     2028593.613      147837.957
#Sta/Elev= 30
       0 1817.44    13.1 1813.75    22.9 1807.81      36 1793.11    72.1 1767.99
   80.911759.463    88.4 1753.97  115.411752.461     1171752.396   127.8 1751.71
   140.9 1746.55     154 1745.11   163.31739.914   173.6 1735.08   203.1 1733.63
  210.231730.847   216.1 1728.78   229.2 1730.72  252.971728.705   307.4  1722.7
     340 1705.74     349 1702.79   359.6 1701.89   369.4  1703.3   382.4 1704.42
   405.2  1711.2   437.8 1714.95   473.7 1716.06     503 1720.66   568.2 1724.87
#Mann= 9 ,-1 , 0
       0     .12       0   80.91    .016       0  115.41     .12       0
     117    .016       0   163.3     .12       0  210.23    .016       0
  252.97     .12       0     349    .045       0   369.4     .12       0
Bank Sta=349,369.4
XS Rating Curve= 0 ,0
Exp/Cntr=0.3,0.1

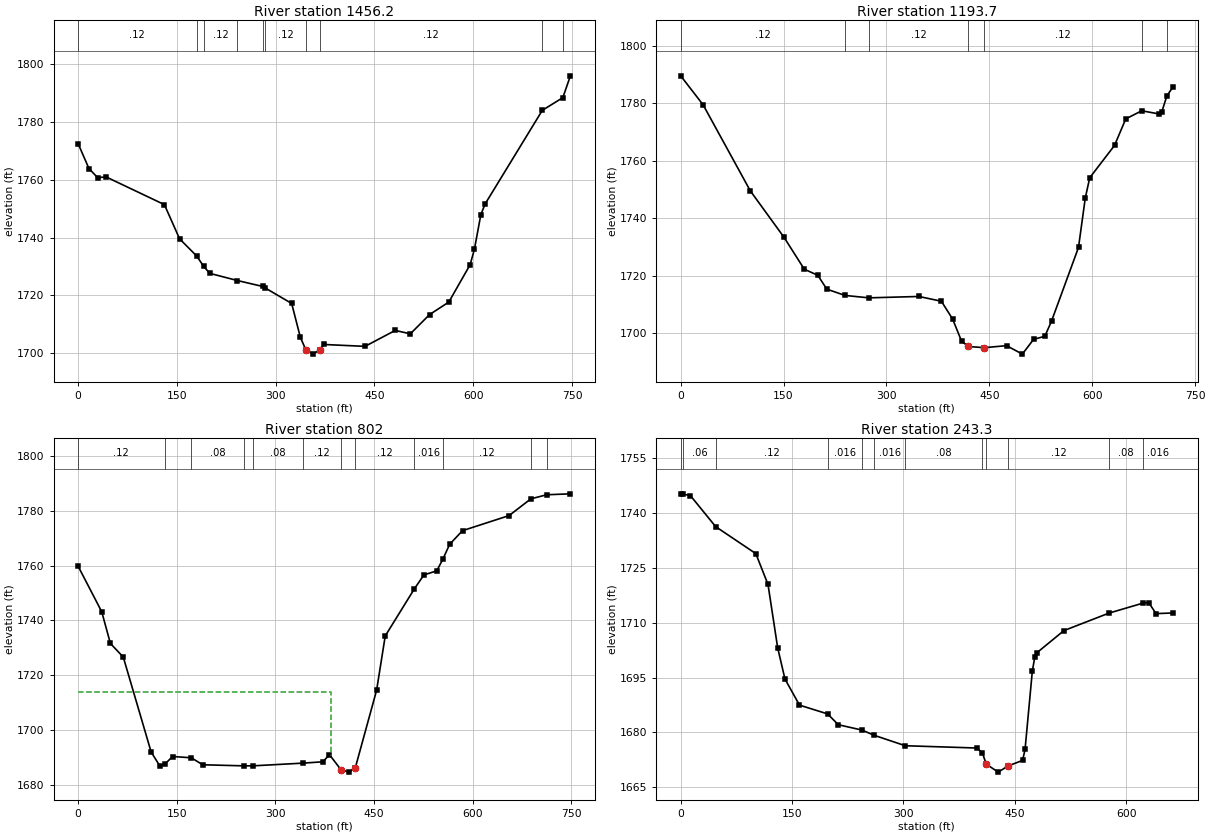
Type RM Length L Ch R = 1 ,1456.2  ,263.6,262.5,271.7
XS GIS Cut Line= 3
     2029143.153      147520.832     2028662.373      147694.011
     2028426.817      147716.189
#Sta/Elev= 30
       0  1772.5    16.4 1763.89    29.5 1760.77    42.6 1760.98     131 1751.39
     154 1739.56  179.851733.631  190.571730.037   199.8 1727.59  241.951725.091
  280.441723.038  284.211722.509   324.3 1717.15   337.4 1705.46   345.6 1701.18
   357.1  1699.6   366.9 1701.18   373.4 1702.94   435.7 1702.29   481.5 1707.81
   504.5 1706.63   533.7  1713.3   562.9 1717.63   595.3 1730.59   601.8 1735.92
   611.5 1747.84     618 1751.61  704.921784.062   736.1 1788.47   747.6 1796.02
#Mann= 10 ,-1 , 0
       0     .12       0  179.85     .08       0  190.57     .12       0
  241.95    .016       0  280.44     .06       0  284.21     .12       0
   345.6    .045       0   366.9     .12       0  704.92    .016       0
   736.1     .12       0
Bank Sta=345.6,366.9
XS Rating Curve= 0 ,0
Exp/Cntr=0.3,0.1

Type RM Length L Ch R = 1 ,1193.7  ,395.1,391.7,377.5
XS GIS Cut Line= 2
     2029038.796      147234.418     2028405.983       147572.96
#Sta/Elev= 30
       0 1789.61    32.8 1779.46   101.6 1749.48   150.8 1733.27   180.2  1722.2
   199.9 1720.08     213 1715.26  239.521713.063  274.341712.218   347.4  1712.7
   380.1 1711.03   396.5 1704.81   409.6 1697.06   419.5 1695.26   442.4 1694.85
   475.2 1695.55   498.1  1692.6   514.5 1697.75   530.9 1698.82   540.7 1704.12
     580  1729.8   589.9 1747.06   596.4 1754.09   632.5 1765.34   648.9 1774.59
  672.191777.429     698  1776.3   701.3 1776.93  708.811782.583   717.7 1785.73
#Mann= 7 ,-1 , 0
       0     .12       0  239.52    .016       0  274.34     .12       0
   419.5    .045       0   442.4     .12       0  672.19    .016       0
  708.81     .12       0
Bank Sta=419.5,442.4
XS Rating Curve= 0 ,0
Exp/Cntr=0.3,0.1

Type RM Length L Ch R = 1 ,802     ,552.3,558.7,563
XS GIS Cut Line= 3
     2028788.796      146955.772     2028299.212      147263.064
     2028210.671      147408.897
#Sta/Elev= 30
       0 1759.82    35.9 1743.17      49  1731.6    68.6 1726.62     111 1691.88
   124.1 1686.83  131.431687.375   143.7 1690.24  172.121689.779   189.4 1687.22
  252.611686.822   265.41686.825  342.291687.826   372.3 1688.31   382.1 1690.92
   399.5 1685.48   411.5 1684.53   421.3 1685.96   453.9 1714.51     467 1734.34
  511.391751.605   525.8 1756.65   545.4 1758.16  554.571762.398     565 1767.87
   584.5 1772.84   655.3 1778.36  688.491784.485  712.471785.977   748.6 1786.32
#Mann= 12 ,-1 , 0
       0     .12       0  131.43    .016       0  172.12     .08       0
  252.61     .06       0   265.4     .08       0  342.29     .12       0
   399.5    .045       0   421.3     .12       0  511.39    .016       0
  554.57     .12       0  688.49     .06       0  712.47     .08       0
#XS Ineff= 2 , 0
          383.95    1714
Permanent Ineff=
       F       F
Bank Sta=399.5,421.3
XS Rating Curve= 0 ,0
Exp/Cntr=0.3,0.1

Type RM Length L Ch R = 1 ,243.3   ,233.4,243.3,253
XS GIS Cut Line= 2
     2028601.296      146583.377     2027976.296      146804.731
#Sta/Elev= 30
       0 1745.21    3.511745.124    13.1 1744.72    47.11736.243   101.2 1728.87
   117.6 1720.44   130.6 1703.15   140.4 1694.62     160 1687.47  197.921685.064
   212.3 1682.11   244.11680.656  260.741679.214  302.481676.372   398.5 1675.75
  406.331674.464   411.5 1671.34   427.7 1669.16   440.9 1670.84   460.5 1672.37
   463.8 1675.35   473.6 1696.76   476.9 1700.59   480.1 1701.84   516.1 1707.83
   576.71712.602  623.251715.381   630.4 1715.47   640.2 1712.48     663 1712.65
#Mann= 12 ,-1 , 0
       0    .016       0    3.51     .06       0    47.1     .12       0
  197.92    .016       0   244.1     .12       0  260.74    .016       0
  302.48     .08       0  406.33     .12       0   411.5    .045       0
   440.9     .12       0   576.7     .08       0  623.25    .016       0
Bank Sta=411.5,440.9
XS Rating Curve= 0 ,0
Exp/Cntr=0.3,0.1

Chan Stop Cuts=-1
Use User Specified Reach Order=0
Composite Channel Slope=5